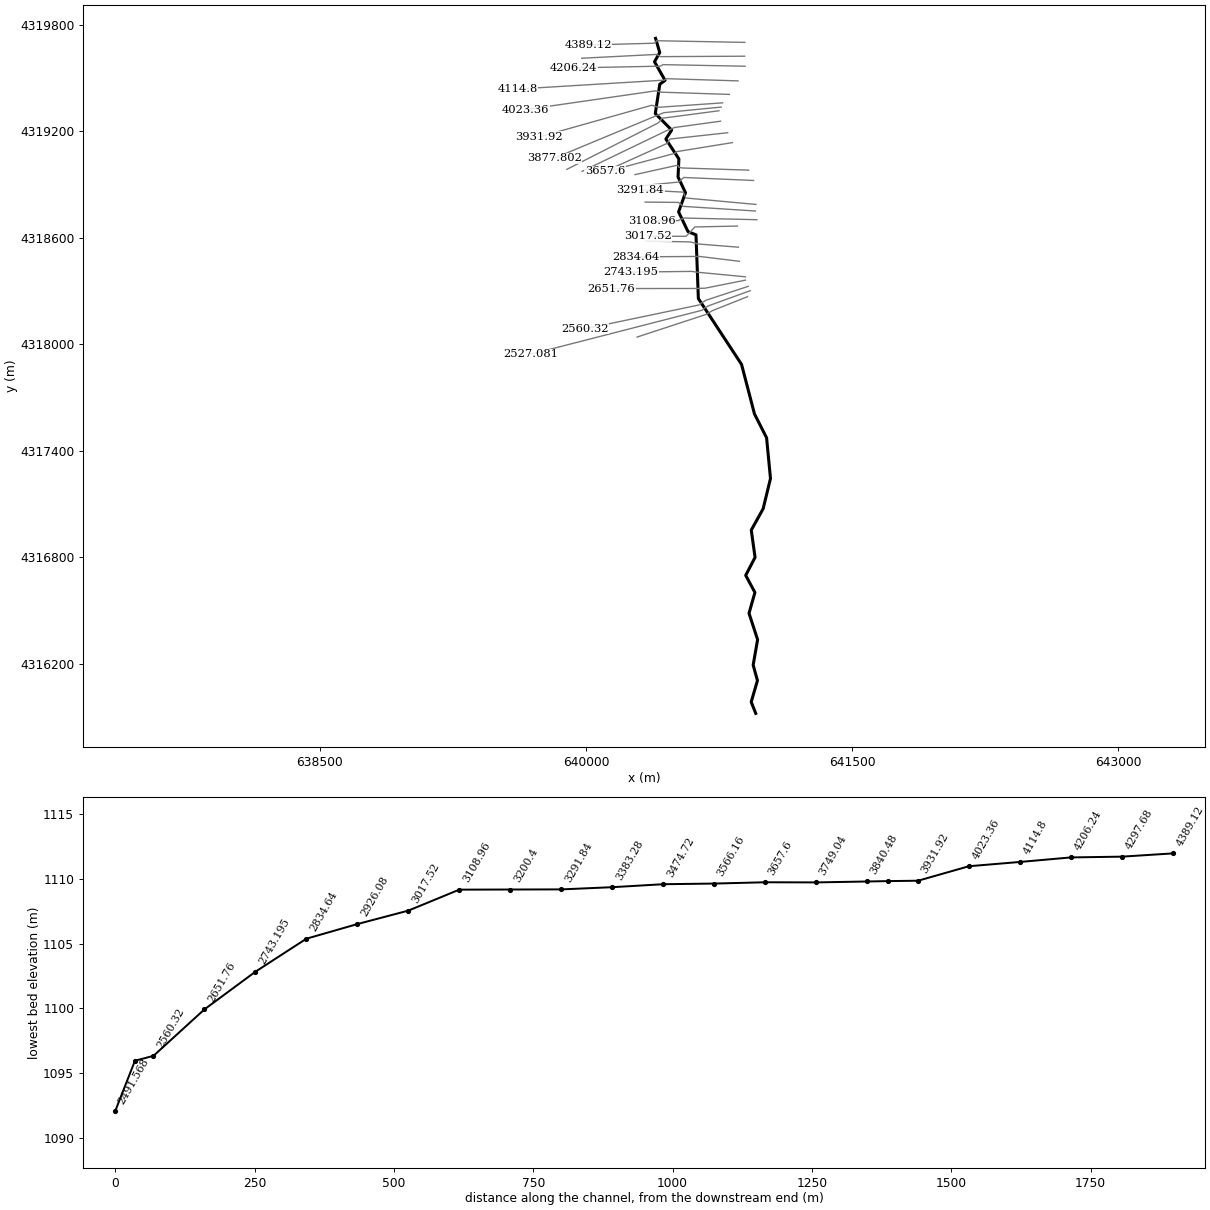
--- RedCreek.prj (project) ---

Proj Title=RedCreek
Current Plan=p01
Default Exp/Contr=0.3,0.1
SI Units
Geom File=g01
Flow File=f01
Plan File=p01
Background Map Layer=Tucker_RedCreekjpg
Y Axis Title=Elevation
X Axis Title(PF)=Main Channel Distance
X Axis Title(XS)=Station
BEGIN DESCRIPTION:
September 2018
Tucker County ABFE Study
US Army Corps of Engineers, Pittsburgh District
NAD 1983 UTM 17N (meters)
END DESCRIPTION:
DSS Export Rating Curves= 0
DSS Export Rating Curve Sorted= 0
DSS Export Volume Flow Curves= 0
DXF OffsetX= 0
DXF OffsetY= 0
DXF ScaleX= 1
DXF ScaleY= 10

--- RedCreek.p01 (plan) ---

Plan Title=RedCreek_plan
Program Version=5.05
Short Identifier=Plan1_subcritical
Geom File=g01
Flow File=f01
Subcritical Flow
K Sum by GR= 0
Std Step Tol= 0.003
Critical Tol= 0.003
Num of Std Step Trials= 20
Max Error Tol= 0.1
Flow Tol Ratio= 0.001
Split Flow NTrial= 30
Split Flow Tol= 0.006
Split Flow Ratio= 0.02
Log Output Level= 0
Friction Slope Method= 1
Unsteady Friction Slope Method= 2
Unsteady Bridges Friction Slope Method= 1
Parabolic Critical Depth
Global Vel Dist= 0 , 0 , 0
Global Log Level= 0
CheckData=True
Encroach Param=-1 ,0,0, 0
Computation Interval=1MIN
Output Interval=1HOUR
Instantaneous Interval=1HOUR
Mapping Interval=1HOUR
Computation Time Step Use Courant=        0
Computation Time Step Use Time Series=    0
Computation Time Step Count To Double=0
Computation Time Step Max Doubling=0
Computation Time Step Max Halving=0
Computation Time Step Residence Courant=0
Run HTab= 0
Run UNet= 0
Run Sediment= 0
Run PostProcess= 0
Run WQNet= 0
Run RASMapper=-1
UNET Theta= 1
UNET Theta Warmup= 1
UNET ZTol= 0.006
UNET ZSATol= 0.006
UNET MxIter= 20
UNET Max Iter WO Improvement= 0
UNET MaxInSteps= 0
UNET DtIC= 0
UNET DtMin= 0
UNET MaxCRTS= 20
UNET WFStab= 2
UNET SFStab= 1
UNET WFX= 1
UNET SFX= 1
UNET 1D Methodology=Finite Difference
UNET DSS MLevel= 4
UNET Pardiso=0
UNET DZMax Abort= 30
UNET Use Existing IB Tables=-1
UNET Froude Reduction=False
UNET Froude Limit= 0.8
UNET Froude Power= 4
UNET D1 Cores= 0
UNET D2 Coriolis=0
UNET D2 Cores= 0
UNET D2 Theta= 1
UNET D2 Theta Warmup= 1
UNET D2 Z Tol= 0.003
UNET D2 Volume Tol= 0.003
UNET D2 Max Iterations= 20
UNET D2 Equation= 0
UNET D2 RampUpFraction=0.1
UNET D2 TimeSlices= 1
UNET D2 BCVolumeCheck=0
UNET D1D2 MaxIter= 0
UNET D1D2 ZTol=0.003
UNET D1D2 QTol=0.1
UNET D1D2 MinQTol=0.03
Write IC File= 0
Write IC File at Fixed DateTime=0
Write IC File at Sim End=0
Echo Input=False
Echo Parameters=False
Echo Output=False
Write Detailed= 0
HDF Write Warmup=0
HDF Write Time Slices=0
HDF Flush=0
HDF Face Node Velocities=0
HDF Compression= 1
HDF Chunk Size= 1
HDF Spatial Parts= 1
HDF Use Max Rows=0
HDF Fixed Rows= 1
Calibration Method= 0
Calibration Iterations= 20
Calibration Max Change=0.05
Calibration Tolerance=0.2
Calibration Maximum=1.5
Calibration Minimum=0.5
Calibration Optimization Method= 1
WQ AD Non Conservative
WQ ULTIMATE=-1
WQ Max Comp Step=1HOUR
WQ Output Interval=15MIN
WQ Output Selected Increments= 0
WQ Output face flow=0
WQ Output face velocity=0
WQ Output face area=0
WQ Output face dispersion=0
WQ Output cell volume=0
WQ Output cell surface area=0
WQ Output cell continuity=0
WQ Output cumulative cell continuity=0
WQ Output face conc=0
WQ Output face dconc_dx=0
WQ Output face courant=0
WQ Output face peclet=0
WQ Output face adv mass=0
WQ Output face disp mass=0
WQ Output cell mass=0
WQ Output cell source sink temp=0
WQ Output nsm pathways=0
WQ Output nsm derived pathways=0
WQ Output MaxMinRange=-1
WQ Daily Max Min Mean=-1
WQ Daily Range=0
WQ Daily Time=0
WQ Create Restart=0
WQ Fixed Restart=0
WQ System Summary=0
WQ Write To DSS=0
WQ Use Fixed Temperature=0
Sorting and Armoring Iterations= 10
XS Update Threshold= 0.02
Bed Roughness Predictor= 0
Hydraulics Update Threshold= 0.02
Energy Slope Method= 1
Volume Change Method= 1
Sediment Retention Method= 0
XS Weighting Method= 0
Number of US Weighted Cross Sections= 1
Number of DS Weighted Cross Sections= 1
Upstream XS Weight=0
Main XS Weight=1
Downstream XS Weight=0
Number of DS XS's Weighted with US Boundary= 1
Upstream Boundary Weight= 1
Weight of XSs Associated with US Boundary= 0
Number of US XS's Weighted with DS Boundary= 1
Downstream Boundary Weight= 0.5
Weight of XSs Associated with DS Boundary= 0.5
Percentile Method= 0
Sediment Output Level= 4
Mass or Volume Output= 0
Output Increment Type= 1
Profile and TS Output Increment= 1
XS Output Flag= 0
XS Output Increment= 10
Write Gradation File= 0
Read Gradation Hotstart= 0
Write HDF5 File= 1
Write Binary Output= 1
Write DSS Sediment File= 0
SV Curve= 0
Specific Gage Flag= 0

--- RedCreek.f01 (steady flow) ---

Flow Title=RedCreek_flow
Program Version=5.05
Number of Profiles= 1
Profile Names=PF 1
River Rch & RM=Big Run (Dry),1               ,2926.172
   13.31
River Rch & RM=Big Run (Dry),1               ,2468.88
   15.06
River Rch & RM=Big Run (Dry),1               ,1737.216
   24.27
River Rch & RM=Big Run (Dry),1               ,822.96
   25.94
River Rch & RM=Big Run (Dry),1               ,457.2
   26.33
River Rch & RM=Big Run (Dry),1               ,91.43999
   26.76
River Rch & RM=Dry Fork,10              ,23081.12
  307.89
River Rch & RM=Dry Fork,10              ,22806.8
  307.91
River Rch & RM=Dry Fork,10              ,22623.92
  310.69
River Rch & RM=Dry Fork,9               ,22532.48
     934
River Rch & RM=Dry Fork,9               ,16406
   952.8
River Rch & RM=Dry Fork,8               ,16314.56
 1195.91
River Rch & RM=Dry Fork,8               ,14220.07
 1199.83
River Rch & RM=Dry Fork,7               ,14120
 1216.15
River Rch & RM=Dry Fork,7               ,9958.127
 1220.39
River Rch & RM=Dry Fork,6               ,9822.317
 1454.32
River Rch & RM=Dry Fork,6               ,7719.197
 1457.09
River Rch & RM=Dry Fork,5               ,7627.757
 1467.04
River Rch & RM=Dry Fork,5               ,6164.717
 1468.44
River Rch & RM=Dry Fork,4               ,6073.277
  1480.6
River Rch & RM=Elklick Run(Dry),1               ,1061.417
   13.79
River Rch & RM=Elklick Run(Dry),1               ,731.5878
   15.97
River Rch & RM=Elklick Run(Dry),1               ,16.16594
    19.2
River Rch & RM=Fisher Spring Rn,1               ,1096.86
   13.82
River Rch & RM=Fisher Spring Rn,1               ,456.813
   19.37
River Rch & RM=Fisher Spring Rn,1               ,91.05302
    20.1
River Rch & RM=Gandy Run,1               ,1371.6
   11.72
River Rch & RM=Gandy Run,1               ,457.2
   15.12
River Rch & RM=Gandy Run,1               ,91.4392
   15.63
River Rch & RM=Glady Fork,1               ,8138.16
  222.74
River Rch & RM=Glady Fork,1               ,1005.833
  232.28
River Rch & RM=Glady Fork,1               ,91.43997
  233.07
River Rch & RM=Laurel Fork,1               ,1554.48
  220.76
River Rch & RM=Laurel Fork,1               ,91.44006
  222.65
River Rch & RM=LeftForkRedCreek,1               ,3840.692
   13.25
River Rch & RM=LeftForkRedCreek,1               ,2926.292
   16.14
River Rch & RM=LeftForkRedCreek,1               ,2560.532
   21.58
River Rch & RM=LeftForkRedCreek,1               ,1737.572
   23.28
River Rch & RM=LeftForkRedCreek,1               ,457.2889
   25.94
River Rch & RM=LeftForkRedCreek,1               ,365.9717
   25.99
River Rch & RM=LeftForkRedCreek,1               ,91.65176
   29.08
River Rch & RM=Mill Run (Dry),1               ,2926.112
   12.97
River Rch & RM=Mill Run (Dry),1               ,2285.832
   16.76
River Rch & RM=Mill Run (Dry),1               ,1920.397
   17.73
River Rch & RM=Mill Run (Dry),1               ,1645.92
   19.09
River Rch & RM=Mill Run (Dry),1               ,1005.84
   21.46
River Rch & RM=Mill Run (Dry),1               ,91.43994
   22.57
River Rch & RM=Red Creek,6               ,29076.84
   42.62
River Rch & RM=Red Creek,6               ,27523.44
   52.02
River Rch & RM=Red Creek,6               ,27066.17
   69.55
River Rch & RM=Red Creek,6               ,26791.92
   72.89
River Rch & RM=Red Creek,6               ,26243.28
   76.43
River Rch & RM=Red Creek,6               ,24871.68
    86.2
River Rch & RM=Red Creek,6               ,24597.36
   87.27
River Rch & RM=Red Creek,6               ,22037.04
  106.13
River Rch & RM=Red Creek,6               ,20665.44
  130.99
River Rch & RM=Red Creek,6               ,19933.92
  135.55
River Rch & RM=Red Creek,5               ,19842.48
  179.16
River Rch & RM=Red Creek,5               ,19659.6
  179.36
River Rch & RM=Red Creek,5               ,17007.84
  193.94
River Rch & RM=Red Creek,4               ,16915.24
  218.44
River Rch & RM=Red Creek,4               ,15727.68
  222.37
River Rch & RM=Red Creek,4               ,13990.32
  243.52
River Rch & RM=Red Creek,3               ,13948.17
  283.25
River Rch & RM=Red Creek,3               ,13898.88
  283.25
River Rch & RM=Red Creek,3               ,10972.8
  304.86
River Rch & RM=Red Creek,3               ,9349.354
   374.8
River Rch & RM=Red Creek,2               ,9303.427
  388.48
River Rch & RM=Red Creek,2               ,9235.439
  388.48
River Rch & RM=Red Creek,2               ,6858
     419
River Rch & RM=Red Creek,2               ,4846.32
  437.41
River Rch & RM=Red Creek,1               ,4738.798
  457.83
River Rch & RM=Red Creek,1               ,4663.459
  457.86
River Rch & RM=Red Creek,1               ,2834.64
  465.61
River Rch & RM=Red Creek,1               ,106.0858
  494.07
River Rch & RM=Stonecoal Run,1               ,4389.12
   12.94
River Rch & RM=Stonecoal Run,1               ,3877.802
   14.89
River Rch & RM=Stonecoal Run,1               ,3840.48
    17.7
River Rch & RM=Stonecoal Run,1               ,2834.64
   19.45
River Rch & RM=Stonecoal Run,1               ,1920.24
   21.29
River Rch & RM=Stonecoal Run,1               ,822.96
   31.32
River Rch & RM=Stonecoal Run,1               ,91.43998
   32.31
River Rch & RM=UnnamedTrib(Red),1               ,1737.381
   14.55
River Rch & RM=UnnamedTrib(Red),1               ,1005.84
   16.11
River Rch & RM=UnnamedTrib(Red),1               ,365.76
   17.73
River Rch & RM=UnnamedTrib(Red),1               ,91.44002
   17.92
Boundary for River Rch & Prof#=Big Run (Dry),1               , 1
Up Type= 2
Dn Type= 0
Boundary for River Rch & Prof#=Dry Fork,10              , 1
Up Type= 2
Dn Type= 0
Boundary for River Rch & Prof#=Dry Fork,9               , 1
Up Type= 0
Dn Type= 0
Boundary for River Rch & Prof#=Dry Fork,8               , 1
Up Type= 0
Dn Type= 0
Boundary for River Rch & Prof#=Dry Fork,7               , 1
Up Type= 0
Dn Type= 0
Boundary for River Rch & Prof#=Dry Fork,6               , 1
Up Type= 0
Dn Type= 0
Boundary for River Rch & Prof#=Dry Fork,5               , 1
Up Type= 0
Dn Type= 0
Boundary for River Rch & Prof#=Dry Fork,4               , 1
Up Type= 0
Dn Type= 1
Dn Known WS=562
Boundary for River Rch & Prof#=Elklick Run(Dry),1               , 1
Up Type= 2
Dn Type= 0
Boundary for River Rch & Prof#=Fisher Spring Rn,1               , 1
Up Type= 2
Dn Type= 0
Boundary for River Rch & Prof#=Gandy Run,1               , 1
Up Type= 2
Dn Type= 0
Boundary for River Rch & Prof#=Glady Fork,1               , 1
Up Type= 2
Dn Type= 0
Boundary for River Rch & Prof#=Laurel Fork,1               , 1
Up Type= 2
Dn Type= 0
Boundary for River Rch & Prof#=LeftForkRedCreek,1               , 1
Up Type= 2
Dn Type= 0
Boundary for River Rch & Prof#=Mill Run (Dry),1               , 1
Up Type= 2
Dn Type= 0
Boundary for River Rch & Prof#=Red Creek,6               , 1
Up Type= 2
Dn Type= 0
Boundary for River Rch & Prof#=Red Creek,5               , 1
Up Type= 0
Dn Type= 0
Boundary for River Rch & Prof#=Red Creek,4               , 1
Up Type= 0
Dn Type= 0
Boundary for River Rch & Prof#=Red Creek,3               , 1
Up Type= 0
Dn Type= 0
Boundary for River Rch & Prof#=Red Creek,2               , 1
Up Type= 0
Dn Type= 0
Boundary for River Rch & Prof#=Red Creek,1               , 1
Up Type= 0
Dn Type= 0
Boundary for River Rch & Prof#=Stonecoal Run,1               , 1
Up Type= 2
Dn Type= 0
Boundary for River Rch & Prof#=UnnamedTrib(Red),1               , 1
Up Type= 2
Dn Type= 0
DSS Import GetInterval= 0
DSS Import GetPeak= 0
DSS Import FillOption= 0

--- RedCreek.g01 (geometry) ---

Geom Title=RedCreek_geometry
Program Version=5.05

Junct Name=20
Junct Desc=, 0 , 0 , 0 ,0
Up River,Reach=Stonecoal Run   ,1
Up River,Reach=Red Creek       ,4
Dn River,Reach=Red Creek       ,3
Junc L&A=68,
Junc L&A=43,

Junct Name=22
Junct Desc=, 0 , 0 , 0 ,0
Up River,Reach=UnnamedTrib(Red),1
Up River,Reach=Red Creek       ,2
Dn River,Reach=Red Creek       ,1
Junc L&A=95,
Junc L&A=16,

Junct Name=6
Junct Desc=, 0 , 0 , 0 ,0
Up River,Reach=Elklick Run(Dry),1
Up River,Reach=Dry Fork        ,6
Dn River,Reach=Dry Fork        ,5
Junc L&A=38,
Junc L&A=92,

Junct Name=8
Junct Desc=, 0 , 0 , 0 ,0
Up River,Reach=Fisher Spring Rn,1
Up River,Reach=Red Creek       ,5
Dn River,Reach=Red Creek       ,4
Junc L&A=61,
Junc L&A=91,

Junct Name=10
Junct Desc=, 0 , 0 , 0 ,0
Up River,Reach=Gandy Run       ,1
Up River,Reach=Red Creek       ,3
Dn River,Reach=Red Creek       ,2
Junc L&A=119,
Junc L&A=50,

Junct Name=12
Junct Desc=, 0 , 0 , 0 ,0
Up River,Reach=Glady Fork      ,1
Up River,Reach=Dry Fork        ,7
Dn River,Reach=Dry Fork        ,6
Junc L&A=178,
Junc L&A=135,

Junct Name=4
Junct Desc=, 0 , 0 , 0 ,0
Up River,Reach=Laurel Fork     ,1
Up River,Reach=Dry Fork        ,9
Dn River,Reach=Dry Fork        ,8
Junc L&A=117,
Junc L&A=91,

Junct Name=15
Junct Desc=, 0 , 0 , 0 ,0
Up River,Reach=LeftForkRedCreek,1
Up River,Reach=Red Creek       ,6
Dn River,Reach=Red Creek       ,5
Junc L&A=110,
Junc L&A=108,

Junct Name=3
Junct Desc=, 0 , 0 , 0 ,0
Up River,Reach=Red Creek       ,1
Up River,Reach=Dry Fork        ,10
Dn River,Reach=Dry Fork        ,9
Junc L&A=190,
Junc L&A=91,

Junct Name=2
Junct Desc=, 0 , 0 , 0 ,0
Up River,Reach=Big Run (Dry)   ,1
Up River,Reach=Dry Fork        ,8
Dn River,Reach=Dry Fork        ,7
Junc L&A=173,
Junc L&A=100,

Junct Name=17
Junct Desc=, 0 , 0 , 0 ,0
Up River,Reach=Dry Fork        ,5
Up River,Reach=Mill Run (Dry)  ,1
Dn River,Reach=Dry Fork        ,4
Junc L&A=92,
Junc L&A=163,

River Reach=Stonecoal Run   ,1
Reach XY= 30
     640391.8715     4319723.991     640415.3026    4319644.3294
     640385.9184    4319591.8313     640445.4497    4319487.0561
      640415.656    4319465.7993      640390.284    4319300.5245
     640482.6128    4319207.2369     640449.8154    4319156.8555
     640523.2374    4319044.9365     640518.5962     4318943.288
     640560.5437    4318854.4361     640521.6499    4318746.4859
     640574.8312    4318634.9638     640619.6782    4318617.1044
     640633.0463    4318258.3365     640876.5481    4317887.4247
     640949.3733    4317608.4548     641017.6887    4317473.9485
     641039.6321    4317244.9452     640998.2547    4317074.4396
      640931.317    4316953.9729     640952.6953    4316800.4374
     640899.9638    4316699.1786     640951.9545    4316602.7378
      640918.617    4316485.6594     640967.0358    4316337.2279
     640942.0327    4316193.9557     640966.2008    4316106.9416
     640930.9201    4315985.9928     640956.5386    4315921.8056

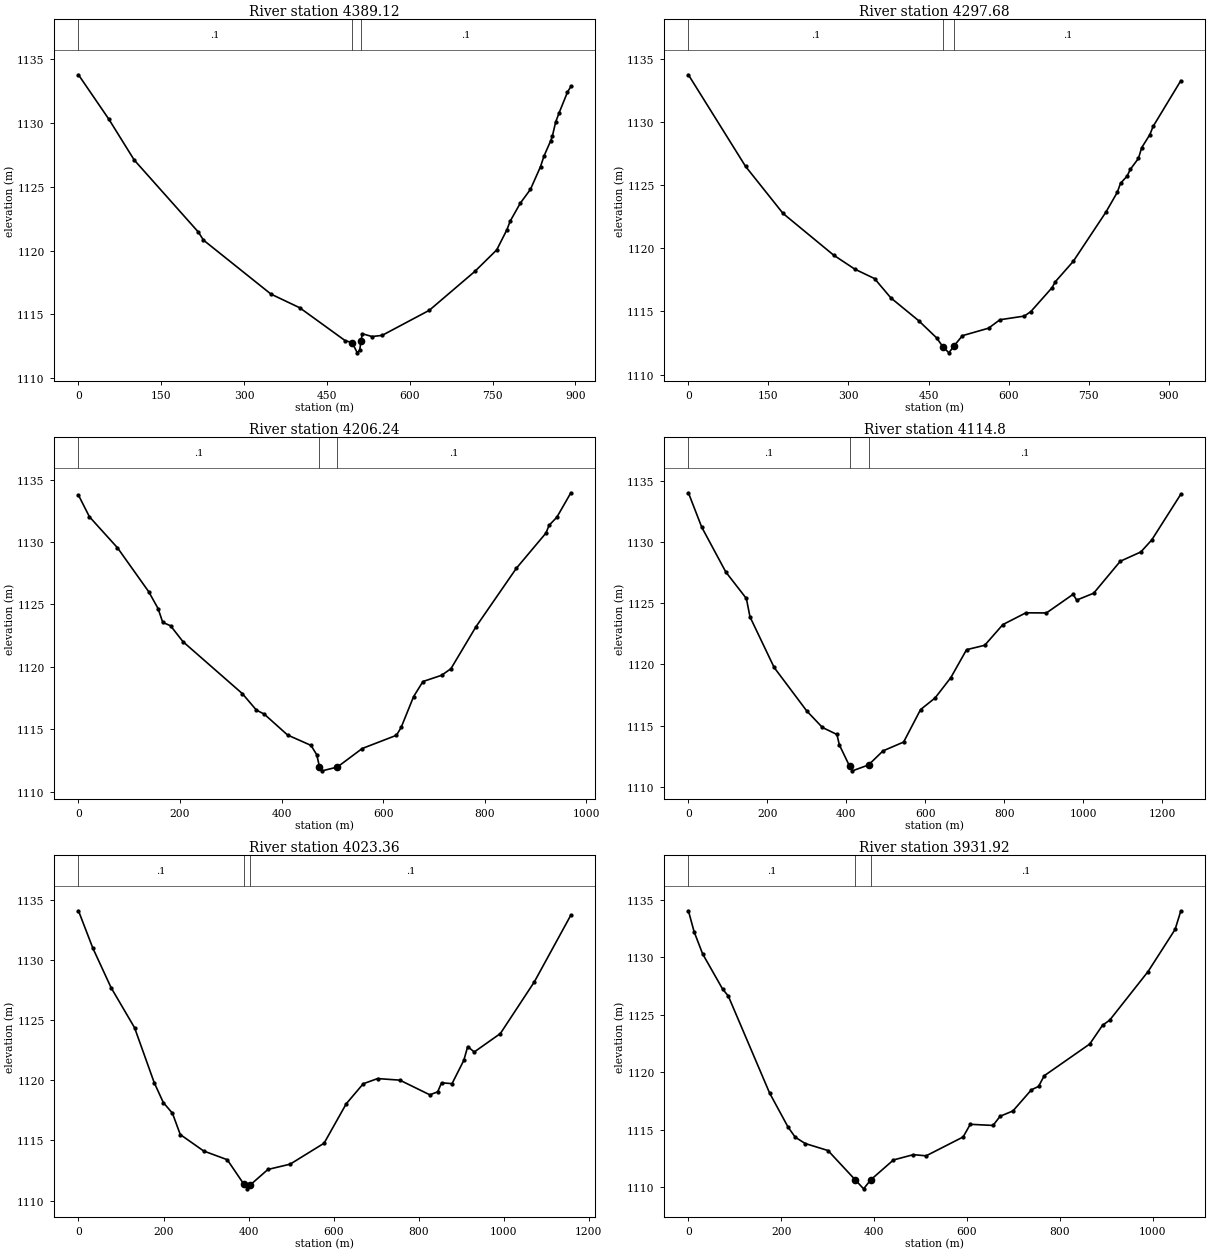
Type RM Length L Ch R = 1 ,4389.12 ,99.97,91.44,77.27
XS GIS Cut Line= 6
     640895.4228    4319701.1655     640396.9152    4319710.5274
      640391.517    4319701.2144     640384.8502    4319698.9916
     640383.1569    4319696.4516     640010.8784    4319686.3759
#Sta/Elev= 30
       0  1133.8   55.06 1130.31  100.94 1127.11  217.18 1121.45  226.36 1120.82
  348.71 1116.58  400.71 1115.51   483.3 1112.92  495.54 1112.78  505.07 1111.97
  509.37 1112.18  511.72 1112.88  514.06 1113.47  531.66 1113.25  549.98 1113.34
  635.45 1115.31  717.87 1118.36  757.55 1120.05  775.87 1121.62  781.97 1122.31
  800.29 1123.72  818.61  1124.8  836.92 1126.59  843.03  1127.4  855.24 1128.61
  858.29 1128.97  864.39  1130.1   870.5  1130.8  885.76 1132.44  891.87 1132.88
#Mann= 3 , 0 , 0
       0      .1       0  495.54      .1       0  511.72      .1       0
Bank Sta=495.54,511.72
XS Rating Curve= 0 ,0
Exp/Cntr=0.3,0.1

Type RM Length L Ch R = 1 ,4297.68 ,70.52,91.44,89.68
XS GIS Cut Line= 6
     640893.8353    4319623.3778      640419.643     4319620.904
     640413.1826     4319625.312     640405.0346    4319629.5264
     640399.1377    4319633.4718     639975.2474    4319611.8741
#Sta/Elev= 30
       0 1133.73  107.08 1126.48  177.44 1122.75  272.28 1119.45  312.05 1118.34
  348.77  1117.6  379.36 1116.07  431.37 1114.27  465.02 1112.91  476.81 1112.21
  488.14 1111.72  498.29  1112.3  513.56 1113.08  562.41 1113.67  583.79 1114.34
  629.59 1114.63   641.8 1114.99   681.5 1116.88  687.61 1117.35  721.19 1118.96
  782.26 1122.85  803.64 1124.42  809.75 1125.14  821.96  1125.7  828.07 1126.24
  843.34 1127.11  849.44 1127.96  864.71 1128.99  870.82 1129.64  922.73 1133.26
#Mann= 3 , 0 , 0
       0      .1       0  476.81      .1       0  498.29      .1       0
Bank Sta=476.81,498.29
XS Rating Curve= 0 ,0
Exp/Cntr=0.3,0.1

Type RM Length L Ch R = 1 ,4206.24 ,81.98,91.44,86.78
XS GIS Cut Line= 6
     640896.5803    4319566.9223     640432.5018    4319575.8454
     640423.9161    4319569.8539     640409.3875    4319564.8248
     640392.8032     4319566.781     639929.7909    4319557.3972
#Sta/Elev= 30
       0 1133.76   21.52 1132.03   76.85 1129.54  138.33 1126.02  156.77 1124.67
  165.99 1123.56  181.36 1123.29  205.95 1122.01  322.76 1117.85  350.43 1116.53
   365.8 1116.21  411.91 1114.53  458.02  1113.7   469.4 1112.94  474.63 1111.99
  479.76 1111.66  509.78 1111.96  558.85 1113.45  626.32 1114.51  635.52 1115.14
  660.06 1117.61  678.46 1118.82  715.26 1119.32  733.66 1119.85  782.73  1123.2
  862.48  1127.9  920.75 1130.72  926.88 1131.34  942.22 1131.99  969.82 1133.95
#Mann= 3 , 0 , 0
       0      .1       0  474.63      .1       0  509.78      .1       0
Bank Sta=474.63,509.78
XS Rating Curve= 0 ,0
Exp/Cntr=0.3,0.1

Type RM Length L Ch R = 1 ,4114.8  ,93.33,91.44,77.21
XS GIS Cut Line= 6
     640856.8927    4319484.3721     640453.2054    4319496.6687
     640447.0117    4319493.7303      640440.622    4319487.8205
     640425.1596    4319487.6728     639613.8777    4319438.3345
#Sta/Elev= 30
       0 1134.01   33.66 1131.21   94.85 1127.54  146.86 1125.38  156.04 1123.88
  217.24 1119.75  299.85  1116.2  339.62 1114.85  376.34 1114.28  382.46 1113.43
  408.45 1111.69   415.6 1111.31  456.38 1111.79  493.18 1112.94  545.32 1113.66
  588.26 1116.31  625.07 1117.26  664.94 1118.92  704.81  1121.2  750.82 1121.56
  796.82 1123.25   855.1 1124.21  907.24  1124.2  974.72 1125.72  983.92 1125.25
 1026.86 1125.81 1094.33 1128.42 1146.47 1129.18 1174.08 1130.16 1247.68 1133.89
#Mann= 3 , 0 , 0
       0      .1       0  408.45      .1       0  456.38      .1       0
Bank Sta=408.45,456.38
XS Rating Curve= 0 ,0
Exp/Cntr=0.3,0.1

Type RM Length L Ch R = 1 ,4023.36 ,94.93,91.44,88.02
XS GIS Cut Line= 6
     640807.6801    4319408.1719     640427.2762     4319420.581
     640416.5606    4319421.9039     640404.2826    4319425.3586
     640390.8298    4319428.1216     639658.3278    4319322.4468
#Sta/Elev= 30
       0 1134.08   33.76 1130.98   76.74 1127.69  131.98 1124.36  178.03 1119.81
  199.51 1118.15     221 1117.26  239.41 1115.49  294.66 1114.12  349.91  1113.4
   388.7 1111.38  397.42 1110.98  404.19 1111.31  445.56 1112.59  497.76 1113.03
  577.61 1114.77  629.81 1118.05  669.73 1119.71  703.51 1120.14  755.72 1120.01
  826.35 1118.79  844.77 1119.04  853.99 1119.79  878.55 1119.72  906.19 1121.65
   915.4  1122.8  930.76 1122.35  992.18 1123.88 1072.02 1128.17 1158.01 1133.72
#Mann= 3 , 0 , 0
       0      .1       0   388.7      .1       0  404.19      .1       0
Bank Sta=388.7,404.19
XS Rating Curve= 0 ,0
Exp/Cntr=0.3,0.1

Type RM Length L Ch R = 1 ,3931.92 ,46.27,54.12,60.68
XS GIS Cut Line= 6
     640769.5801    4319360.5469     640411.4603    4319335.6941
     640397.8078    4319338.2341     640393.6824    4319340.2523
     640370.2921    4319347.1318     639736.1155     4319168.459
#Sta/Elev= 30
       0 1134.03   12.27 1132.21   30.68 1130.28   73.64 1127.23   85.91 1126.62
  174.89 1118.19  214.78 1115.22  230.12 1114.35  251.59  1113.8  300.69 1113.19
  358.98 1110.66  377.46 1109.86   392.7 1110.64  441.68 1112.37  484.58 1112.83
  512.16 1112.73  591.84 1114.37  607.16 1115.47  656.19 1115.37  671.52 1116.17
   699.1 1116.63  738.94 1118.47  754.26 1118.76  766.52 1119.69  864.58 1122.45
  892.16 1124.08  907.48 1124.52  990.23 1128.75 1048.45 1132.41 1060.71 1134.01
#Mann= 3 , 0 , 0
       0      .1       0  358.98      .1       0   392.7      .1       0
Bank Sta=358.98,392.7
XS Rating Curve= 0 ,0
Exp/Cntr=0.3,0.1

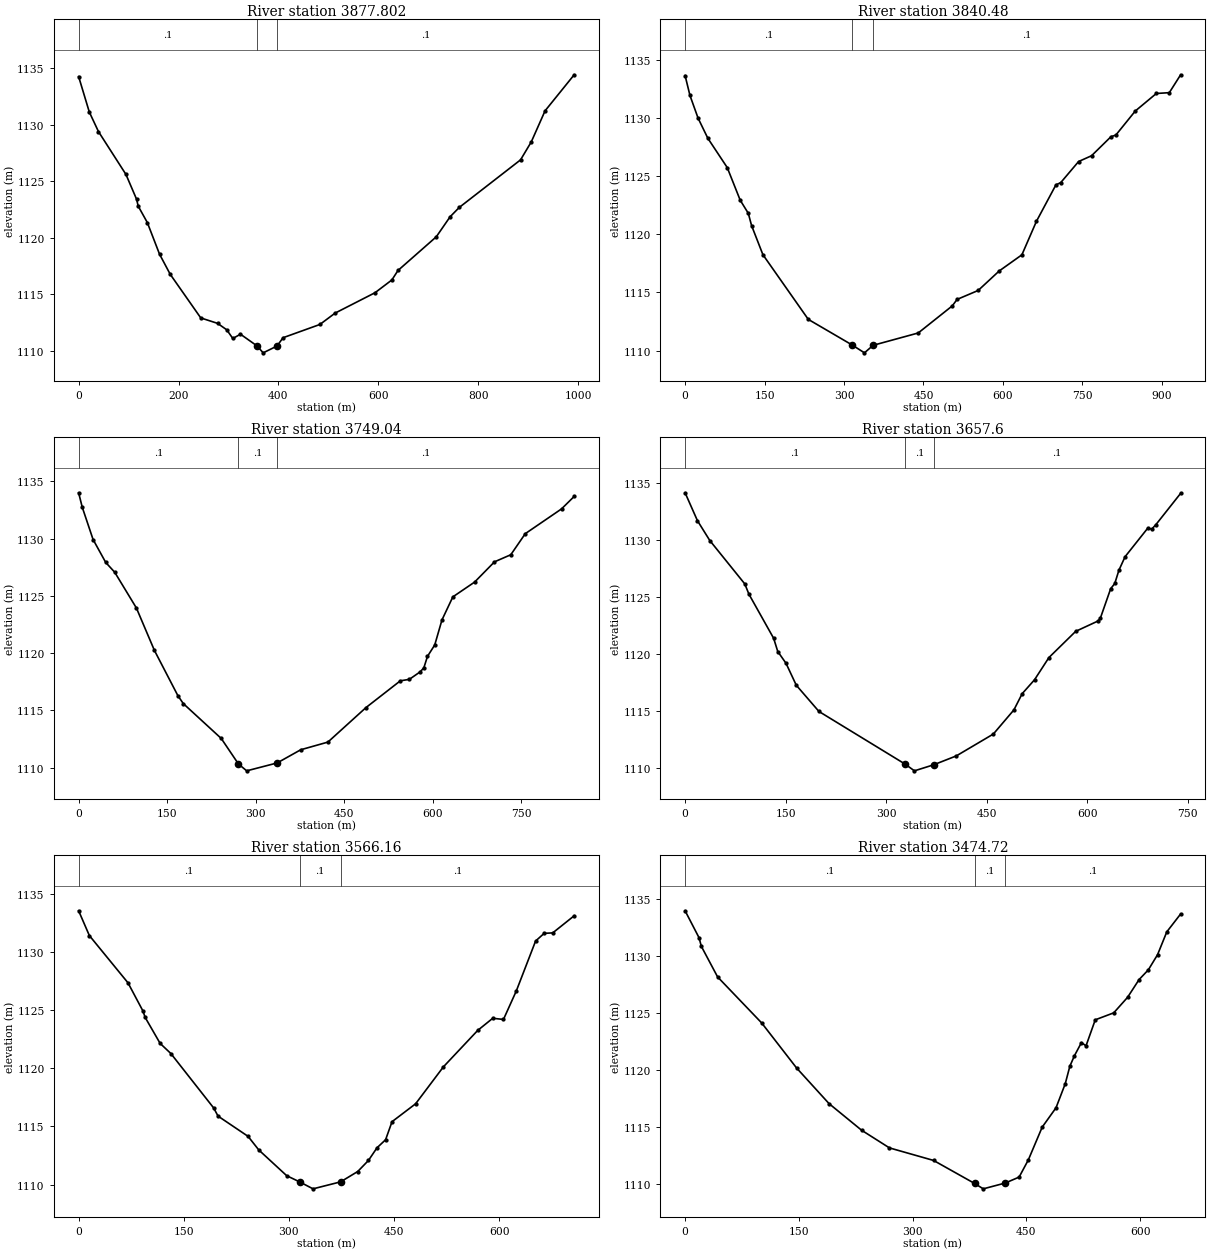
Type RM Length L Ch R = 1 ,3877.802,30.59,37.32,41.5
XS GIS Cut Line= 4
     640761.6425    4319336.7343     640439.0927    4319305.4362
     640402.5802    4319290.7518     639821.8407    4319049.3962
#Sta/Elev= 30
       0 1134.28    21.4 1131.14   39.74 1129.41   94.77 1125.62  116.17 1123.41
  119.23 1122.82  137.57 1121.36  162.03 1118.56  183.43 1116.78  244.58 1112.92
  278.21 1112.44  296.55 1111.87  308.78  1111.1  324.06 1111.48  357.36 1110.44
  369.55 1109.83  397.16 1110.43  409.44 1111.17  483.06 1112.34  513.74 1113.35
   593.5 1115.15  627.25 1116.28  639.52 1117.12  716.21  1120.1  743.82 1121.87
  762.23  1122.7  884.94 1126.91  906.42  1128.5  934.03 1131.25  992.32 1134.44
#Mann= 3 , 0 , 0
       0      .1       0  357.36      .1       0  397.16      .1       0
Bank Sta=357.36,397.16
XS Rating Curve= 0 ,0
Exp/Cntr=0.3,0.1

Type RM Length L Ch R = 1 ,3840.48 ,89.2,91.44,86.61
XS GIS Cut Line= 6
     640748.9425    4319316.0968     640427.3177    4319273.6404
     640420.4914    4319263.6391     640418.7397    4319259.8374
     640406.9407    4319247.8199     639891.6908    4318985.8961
#Sta/Elev= 30
       0 1133.67    9.18 1131.96   24.48 1130.01   42.85 1128.28   79.57 1125.75
  104.06 1122.94  119.36 1121.81  125.48 1120.76   146.9 1118.25   232.6 1112.68
  315.23 1110.48  338.62  1109.8  355.04 1110.45  440.13 1111.51  504.36 1113.84
  513.53  1114.4  553.29 1115.17  593.04 1116.85  635.86 1118.24  663.38 1121.13
  700.08 1124.26  709.26 1124.46   742.9 1126.27  767.36 1126.77  804.06 1128.41
  813.24 1128.55  849.93 1130.62  889.69 1132.13  914.16  1132.2  935.56 1133.74
#Mann= 3 , 0 , 0
       0      .1       0  315.23      .1       0  355.04      .1       0
Bank Sta=315.23,355.04
XS Rating Curve= 0 ,0
Exp/Cntr=0.3,0.1

Type RM Length L Ch R = 1 ,3749.04 ,74.85,91.44,91.44
XS GIS Cut Line= 6
     640758.4675    4319257.3591     640497.9236    4319221.5809
     640483.8408    4319215.0778     640474.3594      4319209.89
     640461.3052    4319207.3992      639977.416    4318974.7836
#Sta/Elev= 30
       0 1134.01    6.12 1132.75   24.46 1129.93   45.87 1127.93   61.16 1127.07
   97.86 1123.95  128.44 1120.24  168.19 1116.29  177.36  1115.6  241.58 1112.56
  270.74 1110.33  284.72 1109.73  336.38 1110.42  376.27 1111.57  422.29 1112.24
  486.72 1115.25  545.01 1117.59  560.35 1117.72  578.76 1118.38  584.89 1118.73
  591.03 1119.73   603.3 1120.72  615.57 1122.91  633.98 1124.92   670.8 1126.21
  704.54 1127.98  732.16  1128.6   756.7 1130.44  818.06  1132.6  839.53 1133.69
#Mann= 3 , 0 , 0
       0      .1       0  270.74      .1       0  336.38      .1       0
Bank Sta=270.74,336.38
XS Rating Curve= 0 ,0
Exp/Cntr=0.3,0.1

Type RM Length L Ch R = 1 ,3657.6  ,91.71,91.44,83.76
XS GIS Cut Line= 6
     640798.1551    4319192.2715     640474.2804     4319156.921
     640466.9779    4319149.4597       640463.62    4319141.3768
     640457.6116    4319132.6322     640107.5912    4318974.7836
#Sta/Elev= 30
       0 1134.14   18.44 1131.69   36.88 1129.95   89.13 1126.14   95.28 1125.24
  132.16 1121.37  138.31 1120.21   150.6 1119.18  165.97 1117.25  199.78 1114.95
  328.41 1110.33  342.26 1109.74  370.99 1110.27  404.77 1111.05  460.07 1112.97
  490.78 1115.09  503.07 1116.51   521.5 1117.73     543 1119.68  582.94 1121.98
  616.72  1122.9   619.8 1123.14  635.15 1125.72   641.3 1126.18  647.44 1127.34
  656.66 1128.53  690.45 1131.03  696.59 1130.96  702.73 1131.35  739.59 1134.09
#Mann= 3 , 0 , 0
       0      .1       0  328.41      .1       0  370.99      .1       0
Bank Sta=328.41,370.99
XS Rating Curve= 0 ,0
Exp/Cntr=0.3,0.1

Type RM Length L Ch R = 1 ,3566.16 ,96.6,91.44,84.06
XS GIS Cut Line= 6
     640825.1427    4319136.7089     640507.9785    4319085.3477
     640503.3218    4319078.4685     640500.6403    4319077.0446
      640493.691    4319074.5527     640139.3413    4318979.5461
#Sta/Elev= 30
       0 1133.54    15.3 1131.41   70.38 1127.35    91.8 1124.92   94.86 1124.38
  116.28 1122.14  131.58 1121.27  192.78 1116.58   198.9 1115.89  241.74 1114.15
  257.04 1112.98  296.82 1110.77  315.18 1110.24  334.41 1109.64  373.71 1110.24
  398.17 1111.13  413.45 1112.08  425.68 1113.17  437.91 1113.86  447.08 1115.41
  480.71 1116.95  520.45 1120.13  569.37 1123.26  590.77  1124.3  606.06  1124.2
   624.4 1126.65  651.91 1130.94  664.14  1131.6  676.37 1131.64  706.94 1133.11
#Mann= 3 , 0 , 0
       0      .1       0  315.18      .1       0  373.71      .1       0
Bank Sta=315.18,373.71
XS Rating Curve= 0 ,0
Exp/Cntr=0.3,0.1

Type RM Length L Ch R = 1 ,3474.72 ,71.01,91.44,97.17
XS GIS Cut Line= 6
     640916.6005    4318981.5746     640540.2127    4318993.8324
     640521.5605    4318998.8619     640520.5012    4319005.7386
     640510.9762    4319008.3845     640276.3075    4318956.4391
#Sta/Elev= 30
       0 1133.97   18.37 1131.61   21.43 1130.85   42.86 1128.17  101.04 1124.13
  146.96 1120.19  189.82 1117.06  232.69 1114.73  269.43 1113.18   327.6 1112.08
  381.77 1110.06  393.16 1109.59  422.15  1110.1  440.41 1110.62  452.58 1112.13
  470.83    1115  489.09  1116.7  501.26 1118.81  507.34 1120.35  513.43 1121.27
  522.55 1122.41  528.64 1122.13  540.81 1124.41  565.15 1125.02   583.4 1126.38
  598.61 1127.94  610.78 1128.79  622.95 1130.12  635.12 1132.12  653.38 1133.69
#Mann= 3 , 0 , 0
       0      .1       0  381.77      .1       0  422.15      .1       0
Bank Sta=381.77,422.15
XS Rating Curve= 0 ,0
Exp/Cntr=0.3,0.1

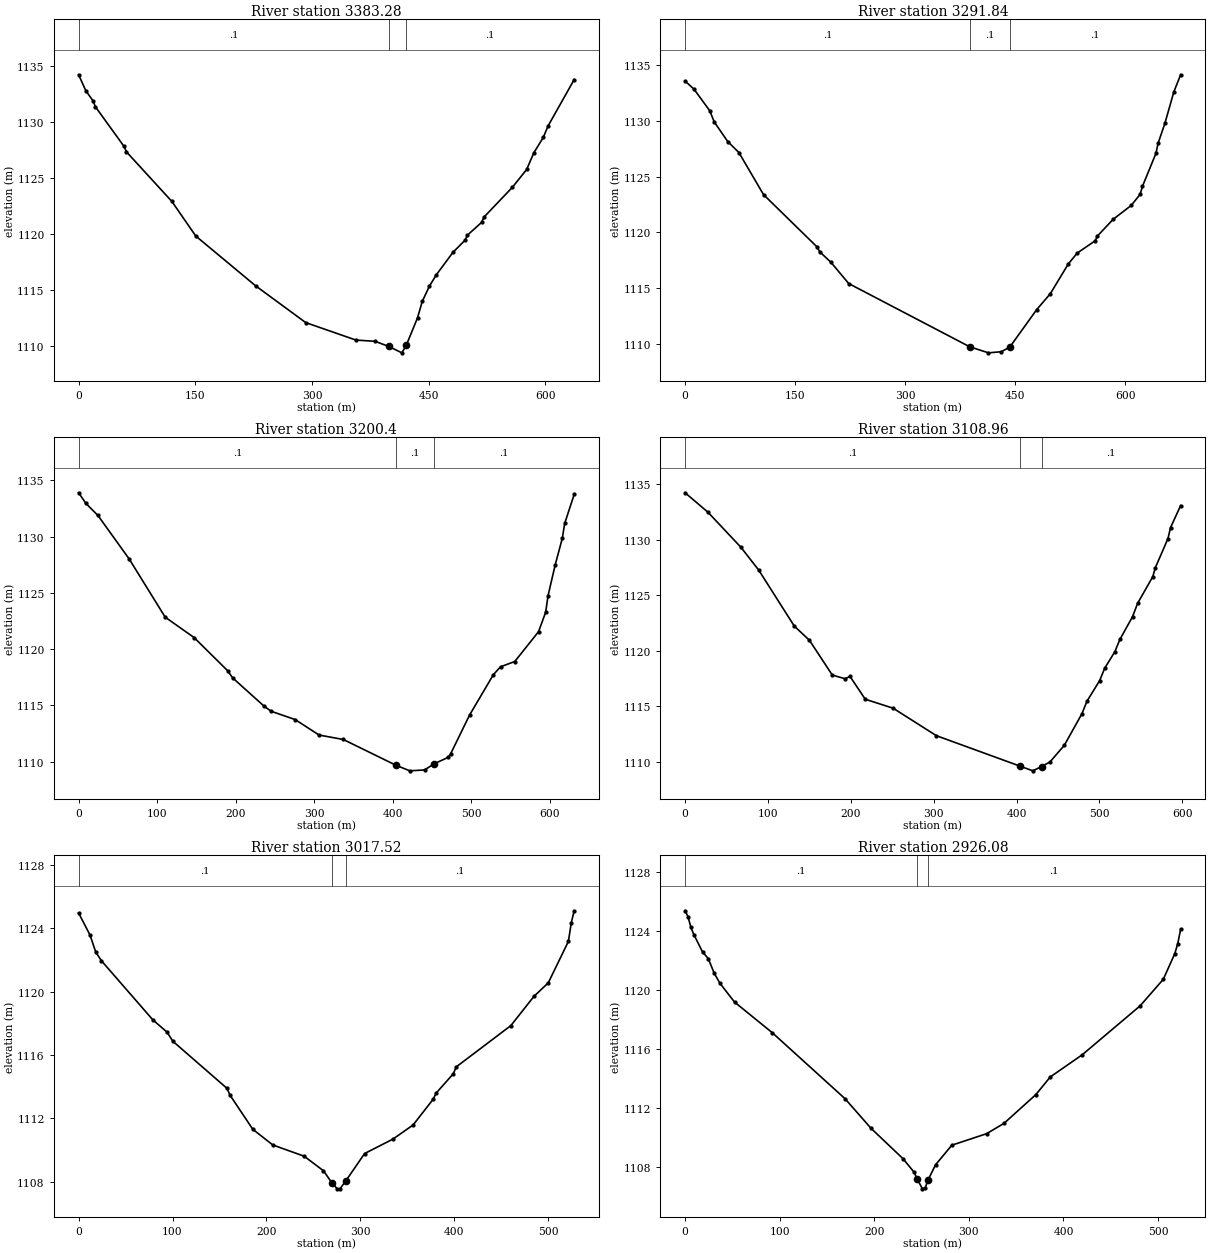
Type RM Length L Ch R = 1 ,3383.28 ,110.72,91.44,69.64
XS GIS Cut Line= 6
     640944.3818    4318923.3661     640551.2691    4318940.3186
     640536.7687    4318928.3787     640527.5612    4318918.2187
      640522.138    4318914.5456      640318.641    4318894.2619
#Sta/Elev= 30
       0 1134.19    9.22 1132.77   18.44 1131.87   21.52 1131.34   58.41 1127.79
   61.48 1127.31  119.89 1122.88  150.63 1119.79  227.48 1115.35  292.03 1112.06
  356.59  1110.5  381.18 1110.39  398.85 1109.93  415.64 1109.36  421.25 1110.03
  435.74 1112.48  441.84 1113.95     451 1115.31  460.16 1116.35  481.52 1118.35
  496.79 1119.41  499.84 1119.86  518.15 1121.01   521.2 1121.48  557.83 1124.15
  576.15 1125.74   585.3 1127.22  597.51  1128.6  603.62 1129.62  637.19 1133.76
#Mann= 3 , 0 , 0
       0      .1       0  398.85      .1       0  421.25      .1       0
Bank Sta=398.85,421.25
XS Rating Curve= 0 ,0
Exp/Cntr=0.3,0.1

Type RM Length L Ch R = 1 ,3291.84 ,69.67,91.44,77.79
XS GIS Cut Line= 6
      640957.611    4318788.4283     640561.9845    4318824.7597
     640557.2679    4318837.6808       640551.67    4318849.5003
     640547.1678    4318857.7004     640305.4118    4318870.4493
#Sta/Elev= 30
       0 1133.59   12.22 1132.85   33.62 1130.92   39.73 1129.92   58.07 1128.16
   73.35 1127.17  106.96 1123.39  180.31 1118.67  183.37 1118.27  198.65 1117.33
  223.09 1115.41  388.12 1109.73  413.59 1109.19  431.14 1109.29  442.68 1109.71
  479.45 1113.08  497.84 1114.49  522.35 1117.16  534.61 1118.15  559.12 1119.25
  562.19 1119.68  583.64 1121.18  608.16 1122.42  620.41 1123.42  623.48 1124.13
  641.86 1127.09  644.93 1128.02  654.12 1129.79  666.38 1132.63  675.57 1134.15
#Mann= 3 , 0 , 0
       0      .1       0  388.12      .1       0  442.68      .1       0
Bank Sta=388.12,442.68
XS Rating Curve= 0 ,0
Exp/Cntr=0.3,0.1

Type RM Length L Ch R = 1 ,3200.4  ,84.07,91.44,102.22
XS GIS Cut Line= 6
     640954.9651    4318751.3866     640545.1966    4318777.7564
     640540.5085    4318783.2937     640535.2033     4318788.095
     640520.8648    4318799.7725     640333.1931    4318801.6575
#Sta/Elev= 30
       0  1133.9    9.19 1132.96   24.51 1131.89   64.35 1128.02  110.31 1122.84
  147.09 1121.03  189.99 1118.07  196.12 1117.45  235.95 1114.95  245.14 1114.48
  275.79 1113.74  306.43 1112.36  337.07 1111.97  404.49 1109.67  421.97 1109.18
  440.71 1109.26  452.73  1109.8   470.9 1110.38  473.92 1110.69  498.14 1114.15
  528.41 1117.73  537.49 1118.43  555.66  1118.9  585.93 1121.55  595.01 1123.28
  598.04 1124.75  607.12 1127.48   616.2 1129.85  619.23 1131.17  631.33 1133.75
#Mann= 3 , 0 , 0
       0      .1       0  404.49      .1       0  452.73      .1       0
Bank Sta=404.49,452.73
XS Rating Curve= 0 ,0
Exp/Cntr=0.3,0.1

Type RM Length L Ch R = 1 ,3108.96 ,89.97,91.44,95.48
XS GIS Cut Line= 6
     640962.9027    4318702.4386     640549.5305     4318711.842
      640544.768    4318707.8203     640532.0799      4318704.48
     640521.5905    4318697.6603     640368.9119    4318694.5011
#Sta/Elev= 30
       0 1134.22   27.57 1132.47   67.38 1129.31   88.82 1127.26   131.7 1122.22
  150.08 1120.93  177.64  1117.8  192.96 1117.47  199.08 1117.67  217.46 1115.62
  251.15 1114.81  303.22 1112.34  404.29 1109.59  419.71 1109.17  430.22 1109.56
  440.38 1109.97   457.6 1111.46  478.98 1114.32  485.09 1115.45  500.36  1117.3
  506.47 1118.42  518.68  1119.9  524.79 1121.01  540.06 1123.06  546.17 1124.26
   564.5 1126.67  567.55 1127.47  582.82  1130.1  585.88 1131.08  598.09 1133.07
#Mann= 3 , 0 , 0
       0      .1       0  404.29      .1       0  430.22      .1       0
Bank Sta=404.29,430.22
XS Rating Curve= 0 ,0
Exp/Cntr=0.3,0.1

Type RM Length L Ch R = 1 ,3017.52 ,99.52,91.44,61.67
XS GIS Cut Line= 5
     640853.4311    4318666.6095        640613.2    4318661.6555
     640579.6902    4318624.6789     640562.6307    4318609.0401
      640348.093    4318608.8541
#Sta/Elev= 30
       0 1124.97   12.17 1123.57   18.25  1122.5   24.33 1121.95   79.08 1118.22
   94.29 1117.44  100.37 1116.87  158.16 1113.89   161.2 1113.47  185.53 1111.31
  206.83 1110.32  240.28 1109.61  260.83 1108.69  269.64 1107.94  275.51 1107.55
  278.44 1107.56  284.33 1108.03  304.65 1109.78  334.78 1110.69  356.23 1111.58
  377.69 1113.21  380.75 1113.59  399.14 1114.82  402.21 1115.25  460.44 1117.86
  484.96  1119.7  500.28 1120.56  521.73 1123.18   524.8 1124.36  527.86 1125.11
#Mann= 3 , 0 , 0
       0      .1       0  269.64      .1       0  284.33      .1       0
Bank Sta=269.64,284.33
XS Rating Curve= 0 ,0
Exp/Cntr=0.3,0.1

Type RM Length L Ch R = 1 ,2926.08 ,87.71,91.44,94.33
XS GIS Cut Line= 6
     640858.7228    4318547.5468     640625.9683    4318566.1705
     640615.4443    4318570.9461     640603.9659    4318573.0048
     640588.5033    4318577.3888     640337.4926    4318581.9427
#Sta/Elev= 30
       0 1125.37    3.07 1124.97    6.14 1124.24    9.22 1123.76   18.43 1122.58
   24.58 1122.12   30.72 1121.14   36.87 1120.45   52.23 1119.18   92.17  1117.1
  168.98 1112.63  196.63 1110.61  230.43 1108.55  242.17 1107.63  245.06 1107.21
  250.89 1106.51   253.8 1106.57  256.72  1107.1  264.75 1108.14  281.97 1109.47
  318.71 1110.25  337.08 1110.95  370.76  1112.9  386.07  1114.1  419.75  1115.6
  480.98 1118.92  505.47 1120.72  517.72 1122.47  520.78 1123.14  523.84 1124.11
#Mann= 3 , 0 , 0
       0      .1       0  245.06      .1       0  256.72      .1       0
Bank Sta=245.06,256.72
XS Rating Curve= 0 ,0
Exp/Cntr=0.3,0.1

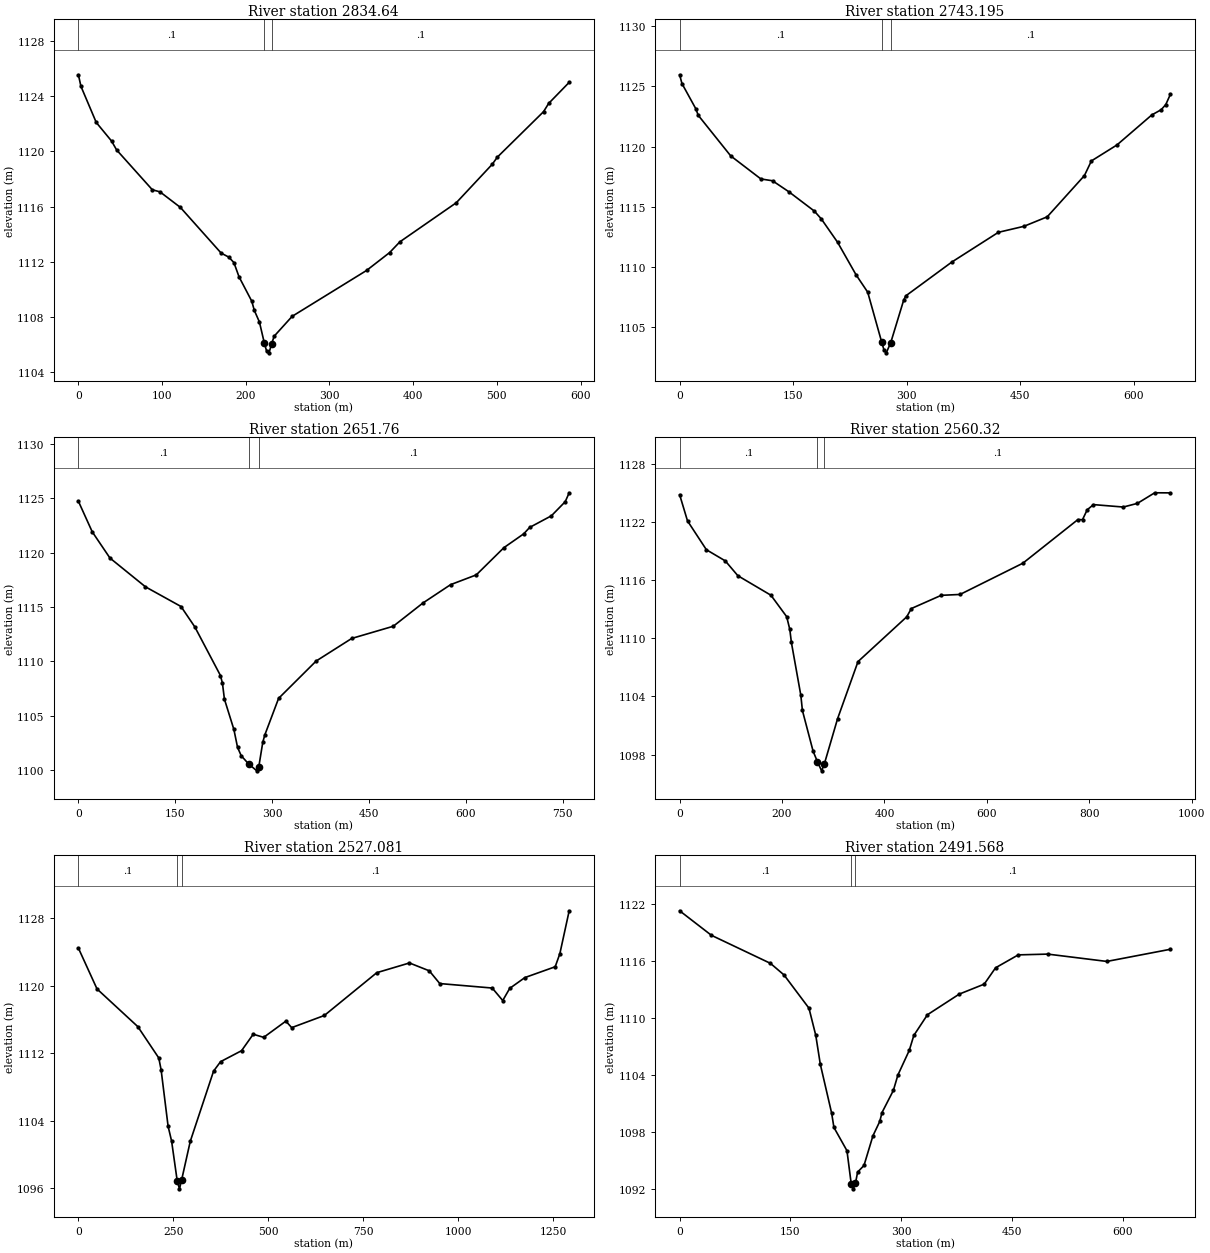
Type RM Length L Ch R = 1 ,2834.64 ,90.59,91.44,90.6
XS GIS Cut Line= 4
     640864.0144    4318468.1716     640646.2926    4318494.7452
     640637.8606    4318495.4924     640279.2841    4318493.3071
#Sta/Elev= 30
       0 1125.57    3.05 1124.73   21.32 1122.11    39.6 1120.76    45.7 1120.11
   88.34 1117.22   97.48 1117.07  121.85 1115.94   170.6 1112.62  179.73 1112.33
  185.83 1111.93  191.92  1110.9  207.15 1109.13   210.2 1108.46  216.29 1107.62
  222.04 1106.12  224.98 1105.48   227.8 1105.38  230.87 1106.04  233.93 1106.59
  255.39 1108.03  344.27 1111.36  371.85 1112.66  384.11 1113.44  451.53 1116.28
  494.44 1119.07  500.57 1119.59  555.74 1122.89  561.87 1123.49  586.39 1125.02
#Mann= 3 , 0 , 0
       0      .1       0  222.04      .1       0  230.87      .1       0
Bank Sta=222.04,230.87
XS Rating Curve= 0 ,0
Exp/Cntr=0.3,0.1

Type RM Length L Ch R = 1 ,2743.195,90.5,91.44,92.71
XS GIS Cut Line= 4
     640898.4103     4318380.859     640623.5486     4318406.998
     640595.5059    4318411.2654     640251.5028    4318407.3173
#Sta/Elev= 30
       0 1125.97    3.07 1125.24   21.47 1123.13   24.54  1122.6   67.49 1119.22
  107.37  1117.3  122.71 1117.15  144.19 1116.24  177.93 1114.63  187.14 1113.98
  208.61 1112.04  233.15 1109.32  248.49 1107.88   266.9 1103.74  269.97 1103.08
  273.03 1102.83  278.94 1103.68  295.96  1107.2  298.79 1107.57  359.76 1110.39
  421.19 1112.86  454.98 1113.36   485.7 1114.15  534.84 1117.58  544.06  1118.8
  577.85 1120.13  623.92 1122.63  636.21 1123.06  642.35 1123.49  648.49 1124.35
#Mann= 3 , 0 , 0
       0      .1       0   266.9      .1       0  278.94      .1       0
Bank Sta=266.9,278.94
XS Rating Curve= 0 ,0
Exp/Cntr=0.3,0.1

Type RM Length L Ch R = 1 ,2651.76 ,84.33,91.44,93.4
XS GIS Cut Line= 5
     640898.4103    4318361.8089     640670.6477    4318316.6349
     640636.5382     4318315.644     640626.5938    4318314.9995
     640143.0234     4318314.713
#Sta/Elev= 30
       0 1124.74   21.39 1121.93   48.88 1119.51  103.88 1116.86  158.87 1115.05
  180.26 1113.17  219.98 1108.69  223.03 1107.98  226.09 1106.52  240.73 1103.73
  246.42 1102.08   252.1 1101.31  263.48 1100.56  276.29 1099.92  279.35 1100.31
  285.47 1102.55  288.53 1103.21  309.95 1106.59  368.11 1110.03   423.2 1112.11
  487.47 1113.23  533.38 1115.37  576.22 1117.06  616.01 1117.96  658.86 1120.47
  689.47 1121.74  698.65 1122.33  732.31  1123.4  753.74  1124.7  759.86 1125.52
#Mann= 3 , 0 , 0
       0      .1       0  263.48      .1       0  279.35      .1       0
Bank Sta=263.48,279.35
XS Rating Curve= 0 ,0
Exp/Cntr=0.3,0.1

Type RM Length L Ch R = 1 ,2560.32 ,34.08,33.24,34.49
XS GIS Cut Line= 6
     640913.9679    4318327.0426     640674.4715    4318248.3766
     640667.6688    4318243.0935     640648.1617    4318232.7564
     640643.1977    4318223.6115      639991.946    4318087.4355
#Sta/Elev= 30
       0 1124.79   15.37 1122.09   52.26 1119.12   89.15 1117.97  113.75 1116.44
   178.3 1114.43  209.05 1112.22  215.19  1110.9  218.27 1109.56  236.71 1104.11
  239.79 1102.55   260.7 1098.35  268.98 1097.29  277.26 1096.33  282.77 1097.07
  308.51 1101.71  348.37 1107.59  443.42  1112.2  452.62 1113.06  510.87 1114.42
  547.66 1114.51  670.31 1117.73  777.62 1122.22  786.82 1122.22  796.01 1123.24
  808.28 1123.77  866.53 1123.52  894.13  1123.9  927.86 1124.99  958.52 1124.98
#Mann= 3 , 0 , 0
       0      .1       0  268.98      .1       0  282.77      .1       0
Bank Sta=268.98,282.77
XS Rating Curve= 0 ,0
Exp/Cntr=0.3,0.1

Type RM Length L Ch R = 1 ,2527.081,34.58,35.51,35.63
XS GIS Cut Line= 5
     640925.6375      4318302.69     640694.9204    4318219.0815
     640673.4891    4318208.7627     640654.0422    4318192.4908
     639687.5703    4317944.6022
#Sta/Elev= 30
       0 1124.46   49.08 1119.62  156.44 1115.16  211.66 1111.45  217.79 1110.05
   236.2 1103.36   245.4 1101.61  260.27 1096.87  266.21 1095.95     272 1097.04
  294.54 1101.57  355.94 1109.89  374.36 1111.01  429.62 1112.31  460.32 1114.26
  487.95 1113.89  546.28 1115.81  561.63 1115.04  647.59 1116.48  785.74 1121.55
   871.7  1122.7   923.9 1121.77  951.53 1120.26 1089.68 1119.73 1117.31 1118.25
 1135.73 1119.69 1175.64 1120.97 1255.46 1122.25 1267.74  1123.8  1292.3 1128.88
#Mann= 3 , 0 , 0
       0      .1       0  260.27      .1       0     272      .1       0
Bank Sta=260.27,272
XS Rating Curve= 0 ,0
Exp/Cntr=0.3,0.1

Type RM Length L Ch R = 1 ,2491.568,26.81,22.69,18.33
XS GIS Cut Line= 4
     640910.2917    4318268.8674     640710.5308    4318189.4922
     640678.7808    4318169.6484     640287.4612    4318041.2812
#Sta/Elev= 30
       0 1121.31   42.99 1118.73  122.83 1115.78  141.25 1114.56  175.03 1111.06
  184.25  1108.2  190.39 1105.16  205.74 1100.01  208.81 1098.51  226.47 1096.06
  232.23 1092.57  235.11 1092.05  237.99 1092.65  240.87 1093.81  249.51 1094.51
  261.61 1097.63  270.83 1099.14  273.91 1100.08  289.28 1102.41  295.42 1104.03
  310.79 1106.62  316.94 1108.19  335.38 1110.37   378.4 1112.54  412.21 1113.59
  427.58 1115.31  458.31 1116.67  498.27 1116.75  578.18 1115.98  664.23 1117.26
#Mann= 3 , 0 , 0
       0      .1       0  232.23      .1       0  237.99      .1       0
Bank Sta=232.23,237.99
XS Rating Curve= 0 ,0
Exp/Cntr=0.3,0.1