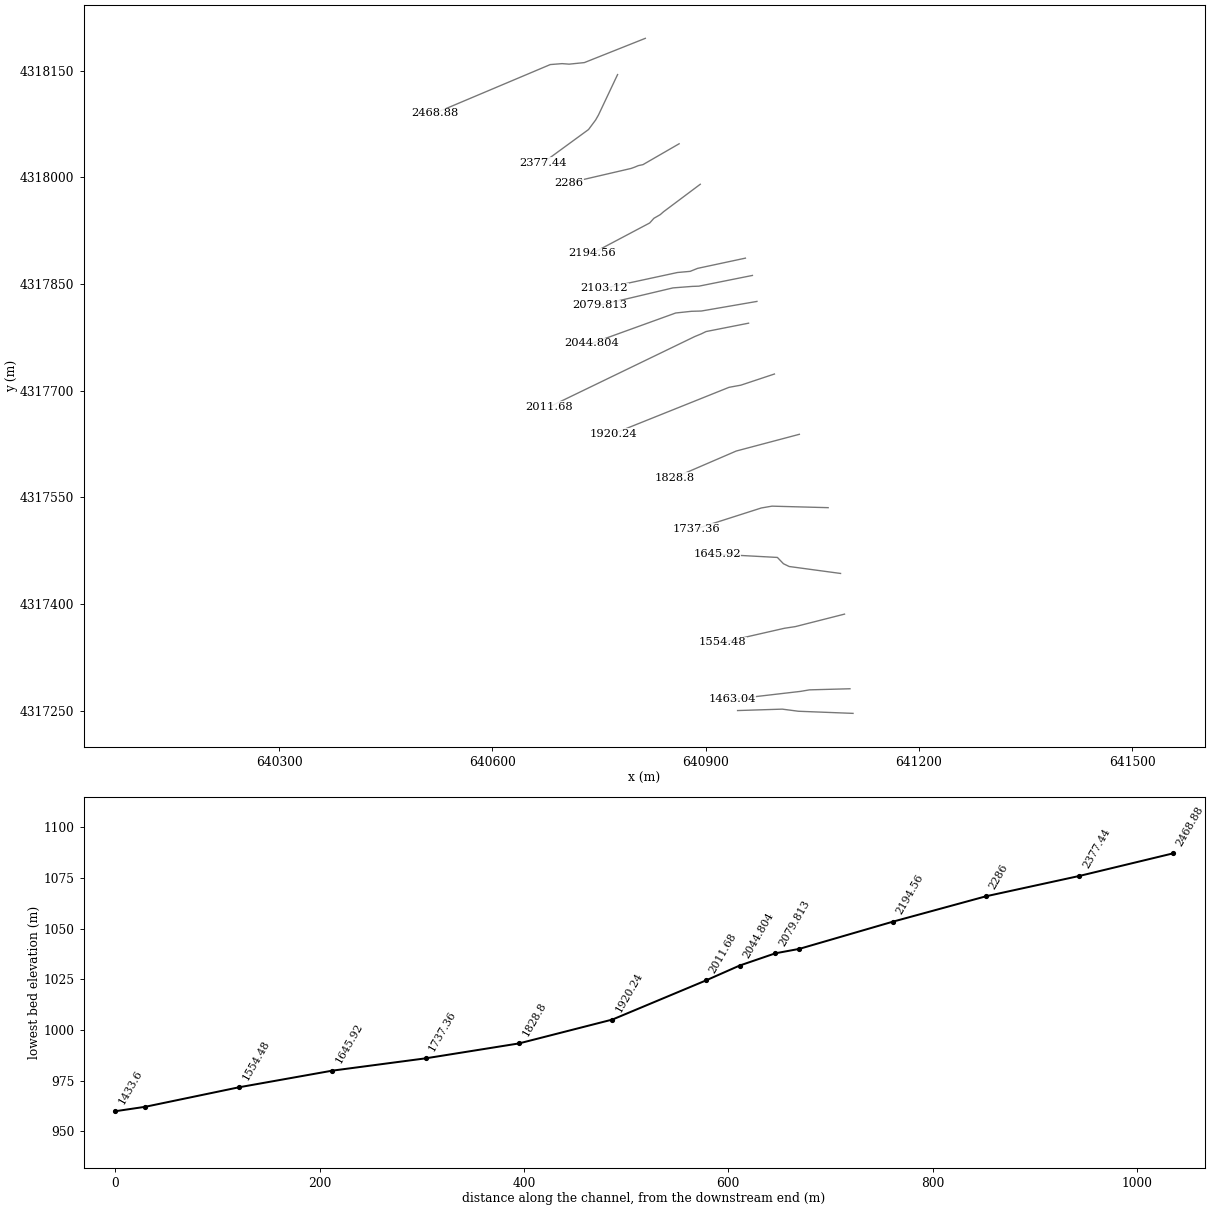
HEC-RAS study RedCreek.prj: RedCreek

--- RedCreek.g01 (geometry) --- (continued)

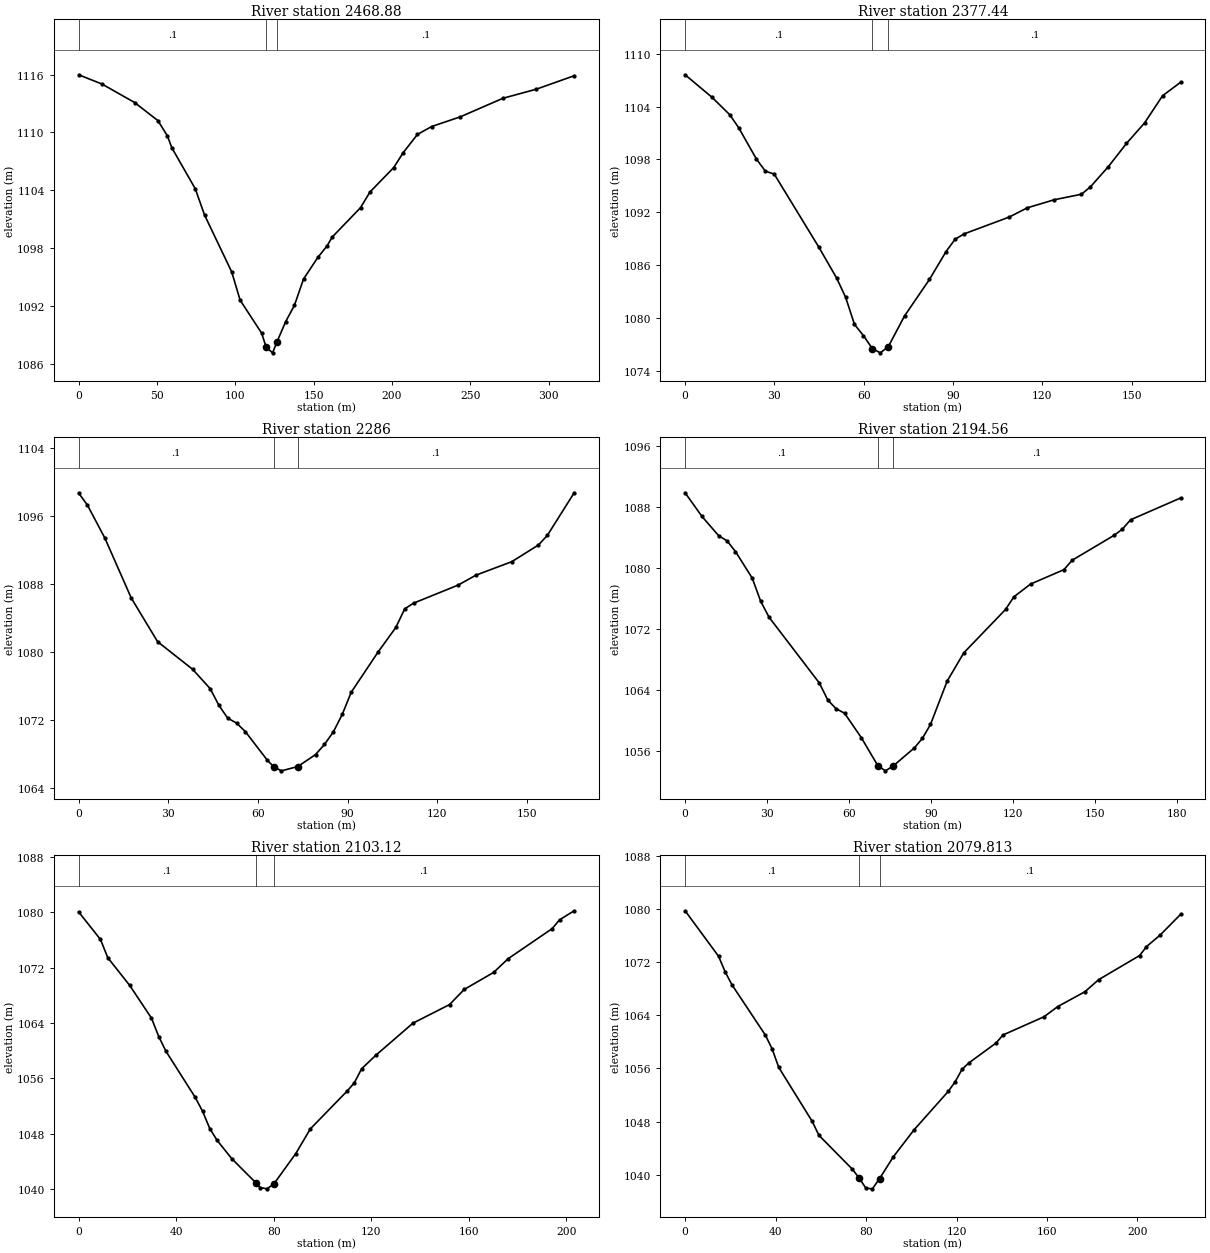
Type RM Length L Ch R = 1 ,2468.88 ,79.63,91.44,101.6
XS GIS Cut Line= 6
     640814.9738    4318195.2931     640729.2051    4318161.1962
     640707.7755    4318159.0057     640697.9181     4318159.741
     640681.2581    4318158.4165     640519.3014     4318090.121
#Sta/Elev= 30
       0 1115.99   14.89 1115.03   35.73 1113.11   50.61 1111.23   56.57 1109.67
   59.55 1108.39   74.43 1104.16   80.39 1101.42   97.68 1095.53  103.07 1092.59
  116.78 1089.17  119.72 1087.69  123.79 1087.12  126.58 1088.26  132.15 1090.36
  137.72 1092.05  143.53 1094.78  152.63 1097.02  158.69 1098.25  161.72 1099.12
   179.9 1102.19  185.96 1103.82  201.11 1106.36  207.17 1107.91  216.27  1109.8
  225.36 1110.62  243.54 1111.62  270.81 1113.55  292.03 1114.49  316.27 1115.89
#Mann= 3 , 0 , 0
       0      .1       0  119.72      .1       0  126.58      .1       0
Bank Sta=119.72,126.58
XS Rating Curve= 0 ,0
Exp/Cntr=0.3,0.1

Type RM Length L Ch R = 1 ,2377.44 ,101.81,91.44,83.97
XS GIS Cut Line= 5
     640775.9477    4318144.3607     640749.0532    4318087.5121
     640745.0731    4318080.5255     640735.0811    4318067.1102
     640671.4371    4318020.6677
#Sta/Elev= 30
       0 1107.62    8.98 1105.08   14.97 1103.09   17.97 1101.62   23.96 1098.04
   26.95 1096.67   29.95 1096.33   44.92 1088.03   50.91 1084.51   53.91 1082.34
    56.9 1079.25   59.89 1077.98   62.89 1076.51   65.57 1076.02   68.25 1076.72
   73.72 1080.22   82.08 1084.36   87.66 1087.53   90.69 1088.93   93.72 1089.54
  108.87 1091.45  114.93  1092.5  124.02 1093.42  133.11 1094.04  136.14 1094.88
   142.2 1097.19  148.26 1099.82  154.32 1102.14  160.38 1105.24  166.45 1106.77
#Mann= 3 , 0 , 0
       0      .1       0   62.89      .1       0   68.25      .1       0
Bank Sta=62.89,68.25
XS Rating Curve= 0 ,0
Exp/Cntr=0.3,0.1

Type RM Length L Ch R = 1 ,2286    ,77.32,91.44,82.46
XS GIS Cut Line= 6
     640862.5195    4318047.0864     640811.6516    4318017.7671
     640805.1365    4318016.3875     640800.5051    4318014.4227
     640794.9513    4318012.4162      640707.738    4317992.1853
#Sta/Elev= 30
       0 1098.72    2.94  1097.3    8.81 1093.39   17.61 1086.35   26.42 1081.21
   38.16 1077.95   44.03 1075.67   46.97 1073.69   49.91 1072.19   52.84 1071.62
   55.78 1070.62   63.15 1067.24   65.37 1066.44   67.89 1065.99   73.36  1066.5
   79.29 1067.91   82.28  1069.1   85.26 1070.59   88.25 1072.66   91.23 1075.25
  100.18 1079.97  106.15 1082.88  109.14 1085.08  112.12 1085.75  127.04 1087.88
  133.01 1089.05  144.95 1090.63   153.9  1092.6  156.88 1093.74  165.84 1098.75
#Mann= 3 , 0 , 0
       0      .1       0   65.37      .1       0   73.36      .1       0
Bank Sta=65.37,73.36
XS Rating Curve= 0 ,0
Exp/Cntr=0.3,0.1

Type RM Length L Ch R = 1 ,2194.56 ,96.33,91.44,89.69
XS GIS Cut Line= 6
     640892.2852    4317990.2009     640840.6068    4317951.5561
     640836.0602    4317947.5476      640827.054    4317942.3474
     640821.1273    4317935.7857     640740.1495    4317892.9663
#Sta/Elev= 30
       0 1089.89    6.15  1086.8   12.29 1084.26   15.36 1083.59   18.44 1082.19
   24.58  1078.7   27.66 1075.68   30.73 1073.58   49.17 1064.94   52.24 1062.72
   55.31 1061.57   58.38 1060.99   64.53 1057.78   70.59  1054.1   73.35 1053.43
    76.1 1054.04   83.97 1056.44   86.91  1057.7   89.86 1059.51   95.97  1065.2
  102.07 1068.91  117.34 1074.59   120.4 1076.25   126.5 1077.92  138.72 1079.81
  141.77 1081.05  157.04  1084.3  160.09 1085.11  163.14 1086.35  181.46 1089.21
#Mann= 3 , 0 , 0
       0      .1       0   70.59      .1       0    76.1      .1       0
Bank Sta=70.59,76.1
XS Rating Curve= 0 ,0
Exp/Cntr=0.3,0.1

Type RM Length L Ch R = 1 ,2103.12 ,24.91,23.31,21.34
XS GIS Cut Line= 5
     640955.7854    4317886.3517     640888.5741    4317871.9874
     640878.0394    4317867.7635     640860.1869    4317866.1587
     640757.3475    4317844.0183
#Sta/Elev= 30
       0 1080.08    8.96 1076.09   11.95 1073.46   20.92 1069.46   29.88 1064.72
   32.87 1062.04   35.86  1059.9   47.81 1053.26    50.8 1051.27   53.79 1048.75
   56.78 1047.05   62.75 1044.42   72.65 1040.92    74.4 1040.23   77.24 1040.04
   80.08 1040.76   89.04 1045.14   95.02 1048.71  110.03 1054.15  113.03 1055.35
  116.04  1057.4  122.05 1059.41  137.08 1063.99   152.1 1066.68  158.12 1068.87
  170.14 1071.32  176.15 1073.32  194.18 1077.66  197.19 1078.93   203.2 1080.24
#Mann= 3 , 0 , 0
       0      .1       0   72.65      .1       0   80.08      .1       0
Bank Sta=72.65,80.08
XS Rating Curve= 0 ,0
Exp/Cntr=0.3,0.1

Type RM Length L Ch R = 1 ,2079.813,35.45,35.01,38.02
XS GIS Cut Line= 5
      640965.632    4317862.0309     640890.2256    4317846.9496
     640881.1504    4317846.6427     640853.8453     4317844.526
     640750.9751    4317820.1843
#Sta/Elev= 30
       0 1079.76   14.79 1072.91   17.75 1070.53    20.7 1068.62   35.49 1061.03
   38.45 1058.97   41.41 1056.16    56.2 1048.03   59.15 1045.94   73.94 1040.83
    76.9 1039.52   79.93 1037.97   82.81 1037.87   85.98 1039.42   92.07  1042.7
   101.2 1046.75  116.39 1052.57  119.41 1054.01  122.43 1055.87  125.45 1056.84
  137.53 1059.85  140.55 1061.05  158.67 1063.79  164.71 1065.32  176.79 1067.57
  182.83 1069.38  200.96 1073.02  203.98 1074.36  210.02  1076.1  219.08 1079.23
#Mann= 3 , 0 , 0
       0      .1       0    76.9      .1       0   85.98      .1       0
Bank Sta=76.9,85.98
XS Rating Curve= 0 ,0
Exp/Cntr=0.3,0.1

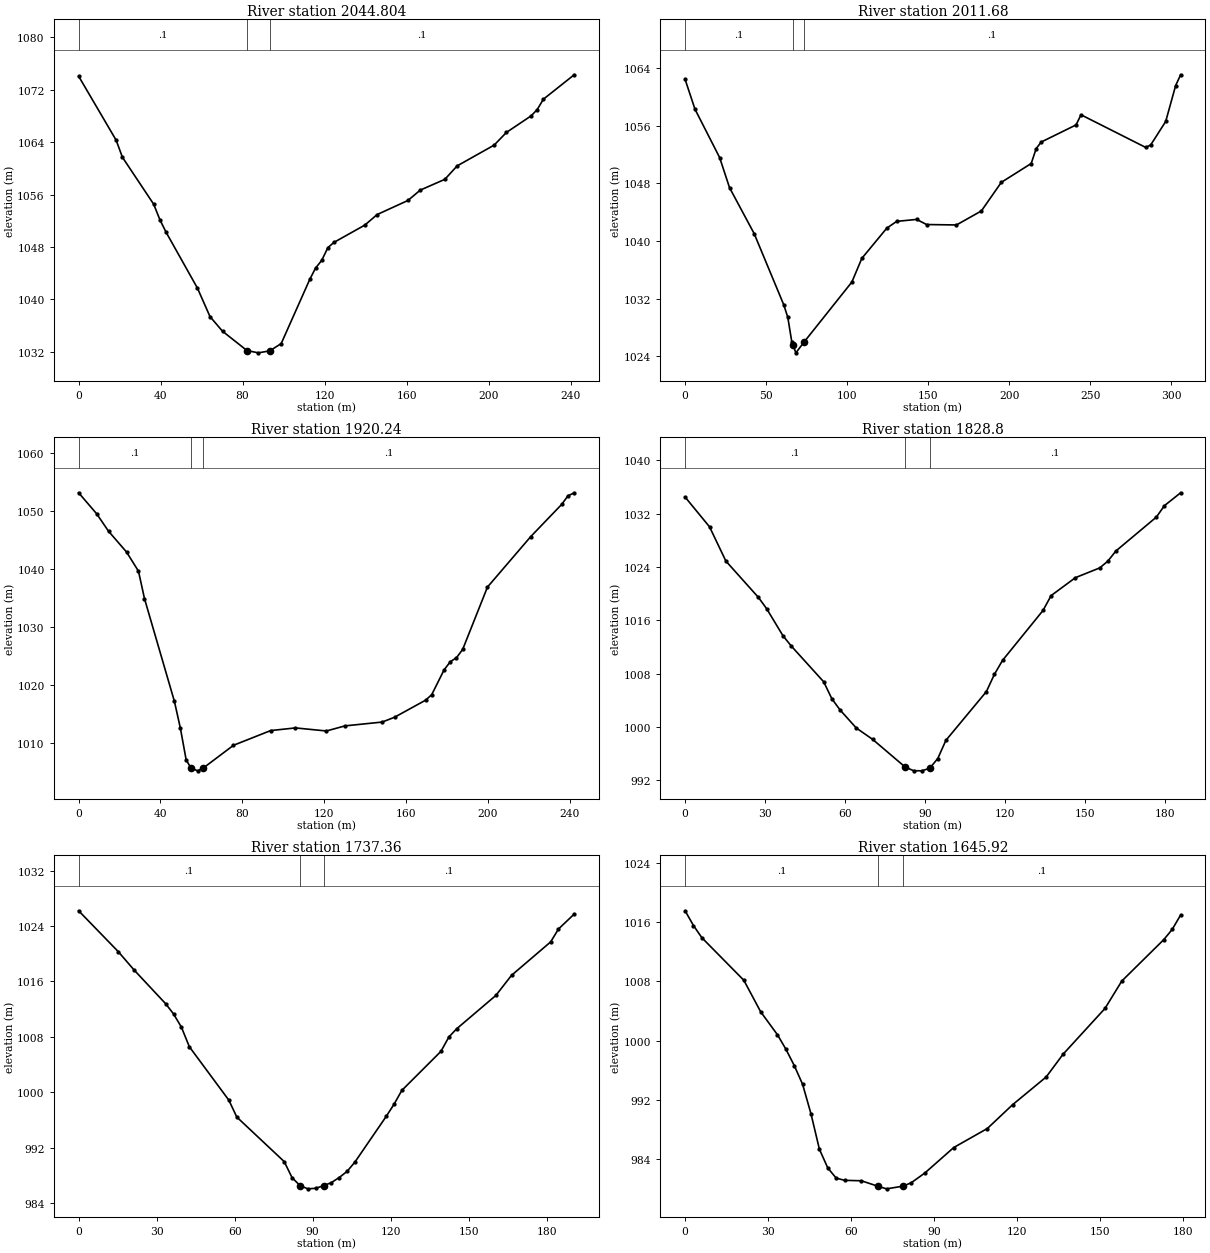
Type RM Length L Ch R = 1 ,2044.804,29.5,33.12,37.03
XS GIS Cut Line= 5
      640971.982    4317825.5183     640893.7975    4317812.0245
     640879.9068    4317811.6277     640857.6818    4317809.2464
     640739.0159    4317766.3838
#Sta/Elev= 30
       0 1074.06   18.31 1064.29   21.36 1061.69   36.62 1054.52   39.67 1052.13
   42.72 1050.21   57.98  1041.7   64.08 1037.37   70.19 1035.13   82.12 1032.18
   87.68 1031.83   93.24 1032.13   98.82 1033.24  112.79 1043.06  115.59 1044.77
  118.59 1045.94   121.6 1047.89   124.6  1048.7  139.62 1051.33  145.63 1052.94
  160.65 1055.09  166.66 1056.67  178.67 1058.32  184.68 1060.37  202.71 1063.54
  208.71 1065.48  220.73    1068  223.73 1068.97  226.74 1070.55  241.76 1074.28
#Mann= 3 , 0 , 0
       0      .1       0   82.12      .1       0   93.24      .1       0
Bank Sta=82.12,93.24
XS Rating Curve= 0 ,0
Exp/Cntr=0.3,0.1

Type RM Length L Ch R = 1 ,2011.68 ,92.47,91.44,88.77
XS GIS Cut Line= 5
     640960.2061     4317794.927     640900.4567    4317783.1689
     640893.7445    4317779.9277      640884.527     4317776.142
     640679.7472    4317677.1872
#Sta/Elev= 30
       0 1062.46    6.09 1058.32   21.31  1051.6    27.4 1047.42   42.63 1041.02
    60.9 1031.12   63.38 1029.38   65.86 1025.94   66.63 1025.49   68.35 1024.46
   73.33 1025.94   102.9  1034.3  109.05 1037.59  124.42 1041.78  130.56 1042.73
  142.86    1043     149 1042.29  167.44 1042.23  182.81 1044.18   195.1 1048.15
  213.55 1050.77  216.62 1052.84  219.69 1053.75  241.21 1056.13  244.28 1057.54
  284.23    1053  287.31 1053.36  296.53 1056.61  302.68 1061.61  305.75  1063.1
#Mann= 3 , 0 , 0
       0      .1       0   66.63      .1       0   73.33      .1       0
Bank Sta=66.63,73.33
XS Rating Curve= 0 ,0
Exp/Cntr=0.3,0.1

Type RM Length L Ch R = 1 ,1920.24 ,92.06,91.44,92.77
XS GIS Cut Line= 4
     640996.5864    4317723.4893     640949.3692    4317707.8046
     640932.7682    4317704.7862     640769.7057     4317639.484
#Sta/Elev= 30
       0  1053.2    8.78 1049.59   14.63 1046.56   23.41 1042.98   29.27 1039.66
   32.19 1034.94   46.83 1017.19   49.75 1012.56   52.57  1007.1    54.9 1005.69
   58.19  1005.2      61  1005.7   75.71 1009.61   93.88 1012.15     106 1012.61
  121.14 1012.08  130.23 1012.96   148.4 1013.62  154.45 1014.45   169.6 1017.39
  172.62 1018.34  178.68 1022.63  181.71 1024.03  184.74 1024.73  187.77 1026.16
  199.88 1036.92  221.08 1045.65  236.22 1051.21  239.25 1052.68  242.28 1053.18
#Mann= 3 , 0 , 0
       0      .1       0    54.9      .1       0      61      .1       0
Bank Sta=54.9,61
XS Rating Curve= 0 ,0
Exp/Cntr=0.3,0.1

Type RM Length L Ch R = 1 ,1828.8  ,93.04,91.44,90.56
XS GIS Cut Line= 3
     641031.6646     4317638.744      640942.889    4317615.2408
     640856.3569    4317577.9682
#Sta/Elev= 30
       0 1034.49    9.18 1030.02   15.31 1024.89   27.55 1019.43   30.61 1017.75
   36.73  1013.7   39.79 1012.18   52.04 1006.78    55.1 1004.24   58.16 1002.57
   64.28  999.85   70.41  998.15   82.65  993.99    85.8  993.45   88.77  993.43
   91.83  993.81   94.87  995.28   97.91     998  113.11 1005.31  116.15 1007.92
  119.19    1010  134.38 1017.48  137.42 1019.71  146.54  1022.4  155.66 1023.86
   158.7 1024.87  161.74  1026.4  176.93 1031.48  179.97  1033.2  186.05 1035.13
#Mann= 3 , 0 , 0
       0      .1       0   82.65      .1       0   91.83      .1       0
Bank Sta=82.65,91.83
XS Rating Curve= 0 ,0
Exp/Cntr=0.3,0.1

Type RM Length L Ch R = 1 ,1737.36 ,96.35,91.44,82.35
XS GIS Cut Line= 4
     641072.1582    4317535.6348     640993.1254    4317537.7533
      640978.226    4317535.2136     640886.4203    4317505.8691
#Sta/Elev= 30
       0  1026.2    15.2 1020.32   21.29 1017.67   33.45 1012.79   36.49 1011.32
   39.53  1009.4   42.57 1006.58   57.78  998.86   60.82  996.43   79.06     990
   82.08  987.68   85.11  986.55   88.13  986.07   91.15  986.15   94.18  986.52
   97.19  986.97   100.2   987.7  103.21  988.58  106.22  989.92  118.27  996.52
  121.28  998.27  124.29 1000.28  139.35 1005.92  142.37 1007.98  145.38 1009.17
  160.44 1013.98  166.46 1016.88  181.52 1021.71  184.53 1023.57  190.56 1025.72
#Mann= 3 , 0 , 0
       0      .1       0   85.11      .1       0   94.18      .1       0
Bank Sta=85.11,94.18
XS Rating Curve= 0 ,0
Exp/Cntr=0.3,0.1

Type RM Length L Ch R = 1 ,1645.92 ,84.38,91.44,105.13
XS GIS Cut Line= 5
     641089.6207    4317443.1627     641017.3815    4317452.9217
     641009.2994    4317456.8131     641000.7687     4317465.676
     640915.7523    4317470.2614
#Sta/Elev= 30
       0 1017.55    3.04 1015.55    6.07 1013.91   21.26 1008.16   27.34 1003.91
   33.41 1000.81   36.45  998.87   39.49  996.65   42.52  994.11   45.56  990.11
    48.6  985.34   51.63  982.81   54.67  981.44   57.71  981.14   63.78  981.08
   69.86  980.33    72.9  979.99   78.88  980.35   81.87  980.82   86.79  982.14
   97.21  985.57  109.37  988.14  118.49  991.35  130.66   995.1  136.74  998.16
  151.94 1004.36  158.02 1008.06  173.23 1013.66  176.27 1015.04  179.31 1016.98
#Mann= 3 , 0 , 0
       0      .1       0   69.86      .1       0   78.88      .1       0
Bank Sta=69.86,78.88
XS Rating Curve= 0 ,0
Exp/Cntr=0.3,0.1

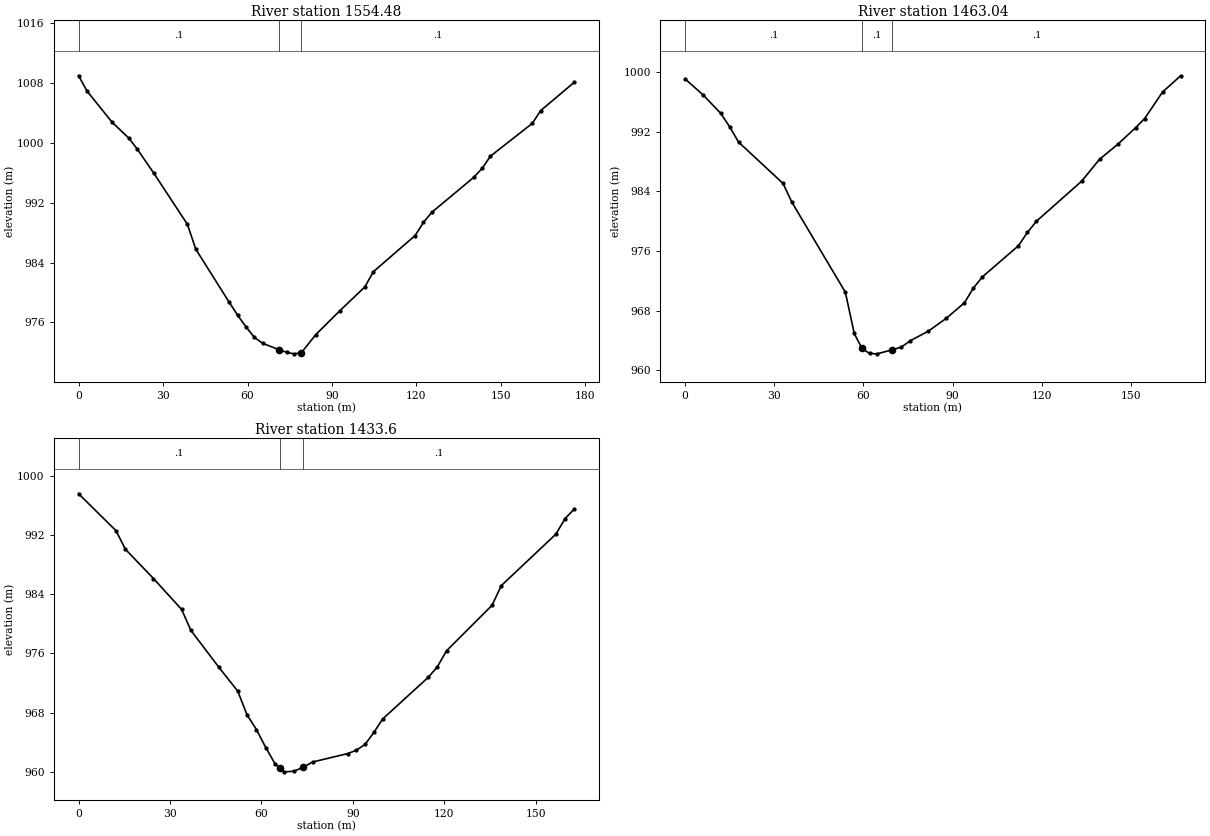
Type RM Length L Ch R = 1 ,1554.48 ,92.51,91.44,91.23
XS GIS Cut Line= 4
      641095.177    4317386.0126     641026.0142    4317368.4542
     641010.7091    4317366.1311     640923.7266     4317346.325
#Sta/Elev= 30
       0    1009    2.97 1006.96   11.89 1002.78   17.84 1000.65   20.81   999.2
   26.76  995.93   38.65  989.11   41.62  985.79   53.52  978.67   56.49  976.95
   59.46  975.39   62.44  973.98   65.41  973.18   71.36  972.31   73.94  971.98
   76.52  971.78    79.1  971.91   84.26  974.36   92.78  977.54  101.71  980.75
  104.68  982.76  119.55  987.62  122.52  989.38  125.49  990.73  140.36   995.4
  143.34   996.6  146.31  998.24  161.18 1002.63  164.15 1004.34  176.05 1008.12
#Mann= 3 , 0 , 0
       0      .1       0   71.36      .1       0    79.1      .1       0
Bank Sta=71.36,79.1
XS Rating Curve= 0 ,0
Exp/Cntr=0.3,0.1

Type RM Length L Ch R = 1 ,1463.04 ,31,29.44,26.92
XS GIS Cut Line= 4
      641102.873    4317281.1018     641045.9698    4317279.5526
     641033.3182    4317277.4143     640936.9558     4317266.209
#Sta/Elev= 30
       0  999.06    5.99  996.94   11.98  994.45   14.98  992.65   17.98  990.59
   32.96  985.04   35.95  982.51   53.93  970.46   56.92  964.93   59.49  962.94
   62.06  962.24   64.62  962.19   69.76  962.74   72.79   963.1   75.82  963.95
   81.88  965.24   87.95  966.97   94.01  969.04   97.04  971.02  100.07  972.52
   112.2  976.69  115.23  978.49  118.26  979.98  133.42  985.33  139.48  988.28
  145.55  990.27  151.61  992.51  154.64  993.74   160.7  997.31  166.77  999.48
#Mann= 3 , 0 , 0
       0      .1       0   59.49      .1       0   69.76      .1       0
Bank Sta=59.49,69.76
XS Rating Curve= 0 ,0
Exp/Cntr=0.3,0.1

Type RM Length L Ch R = 1 ,1433.6  ,32.76,29.75,27.43
XS GIS Cut Line= 4
     641107.1734    4317246.4986      641030.444    4317249.4751
     641007.6237    4317252.4517      640944.785    4317250.4673
#Sta/Elev= 30
       0  997.56   12.29  992.56   15.36  990.06   24.57  986.11   33.79  981.94
   36.86   979.1   46.07   974.1   52.22   970.9   55.29  967.69   58.36  965.71
   61.43  963.27    64.5  961.06   65.97  960.55   67.57  959.99   70.64  960.07
   73.72   960.6   76.79  961.32   88.29  962.45   91.17  962.91   94.05  963.71
   96.92  965.31    99.8  967.13  114.77  972.76  117.76  974.18  120.76  976.34
  135.73   982.5  138.72  985.14  156.68  992.11  159.68  994.21  162.67  995.48
#Mann= 3 , 0 , 0
       0      .1       0   65.97      .1       0   73.72      .1       0
Bank Sta=65.97,73.72
XS Rating Curve= 0 ,0
Exp/Cntr=0.3,0.1