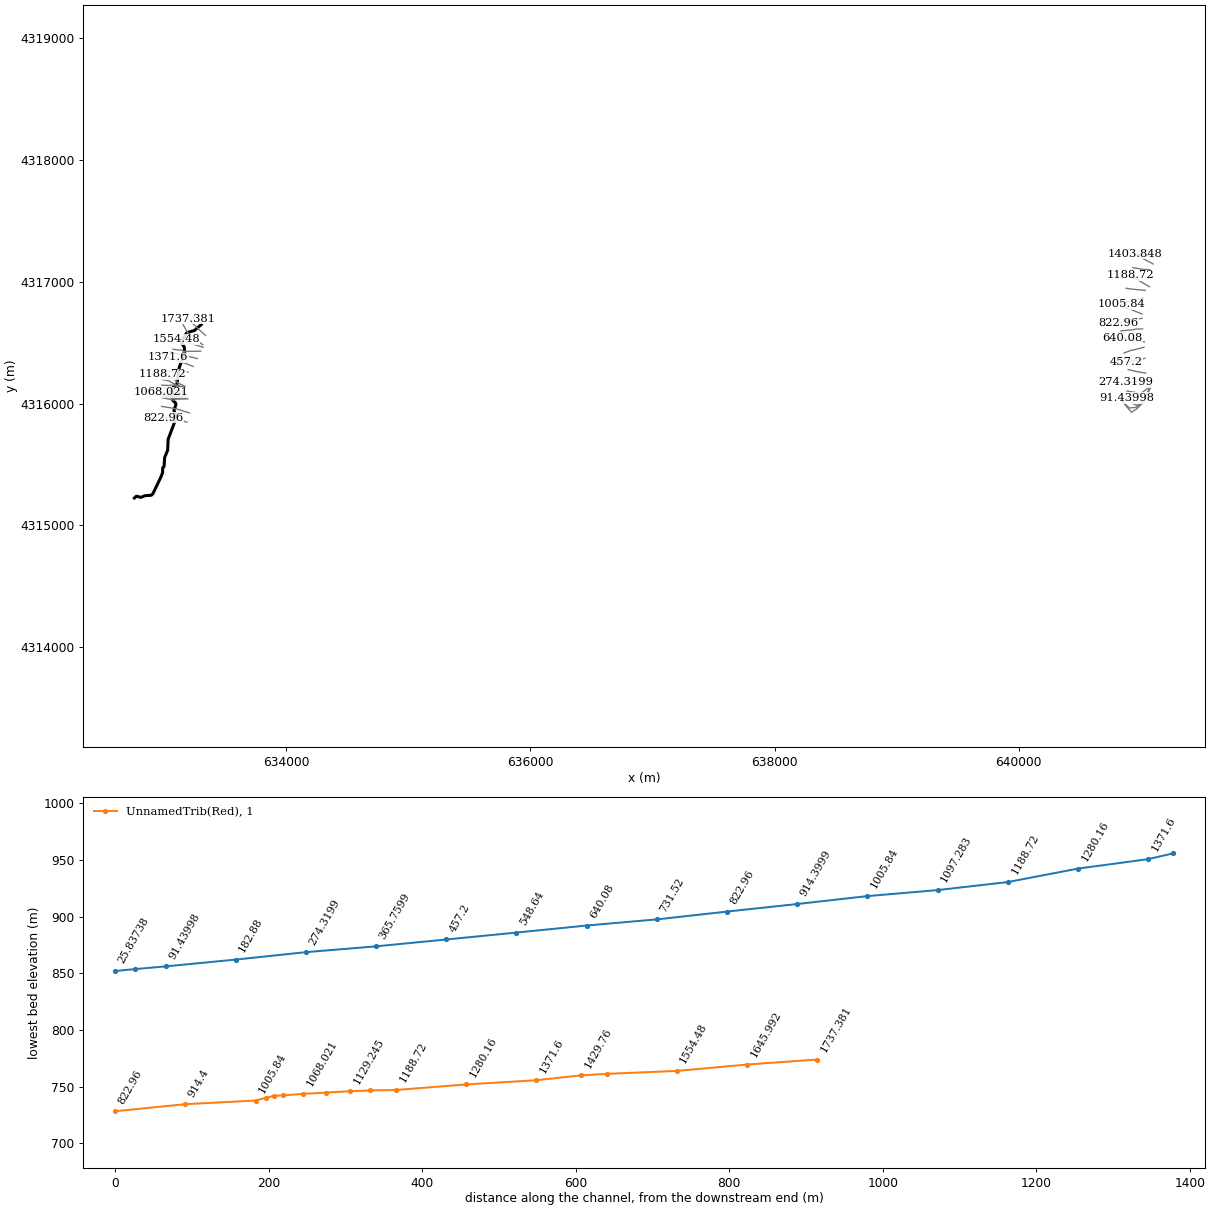
HEC-RAS study RedCreek.prj: RedCreek

--- RedCreek.g01 (geometry) --- (continued)

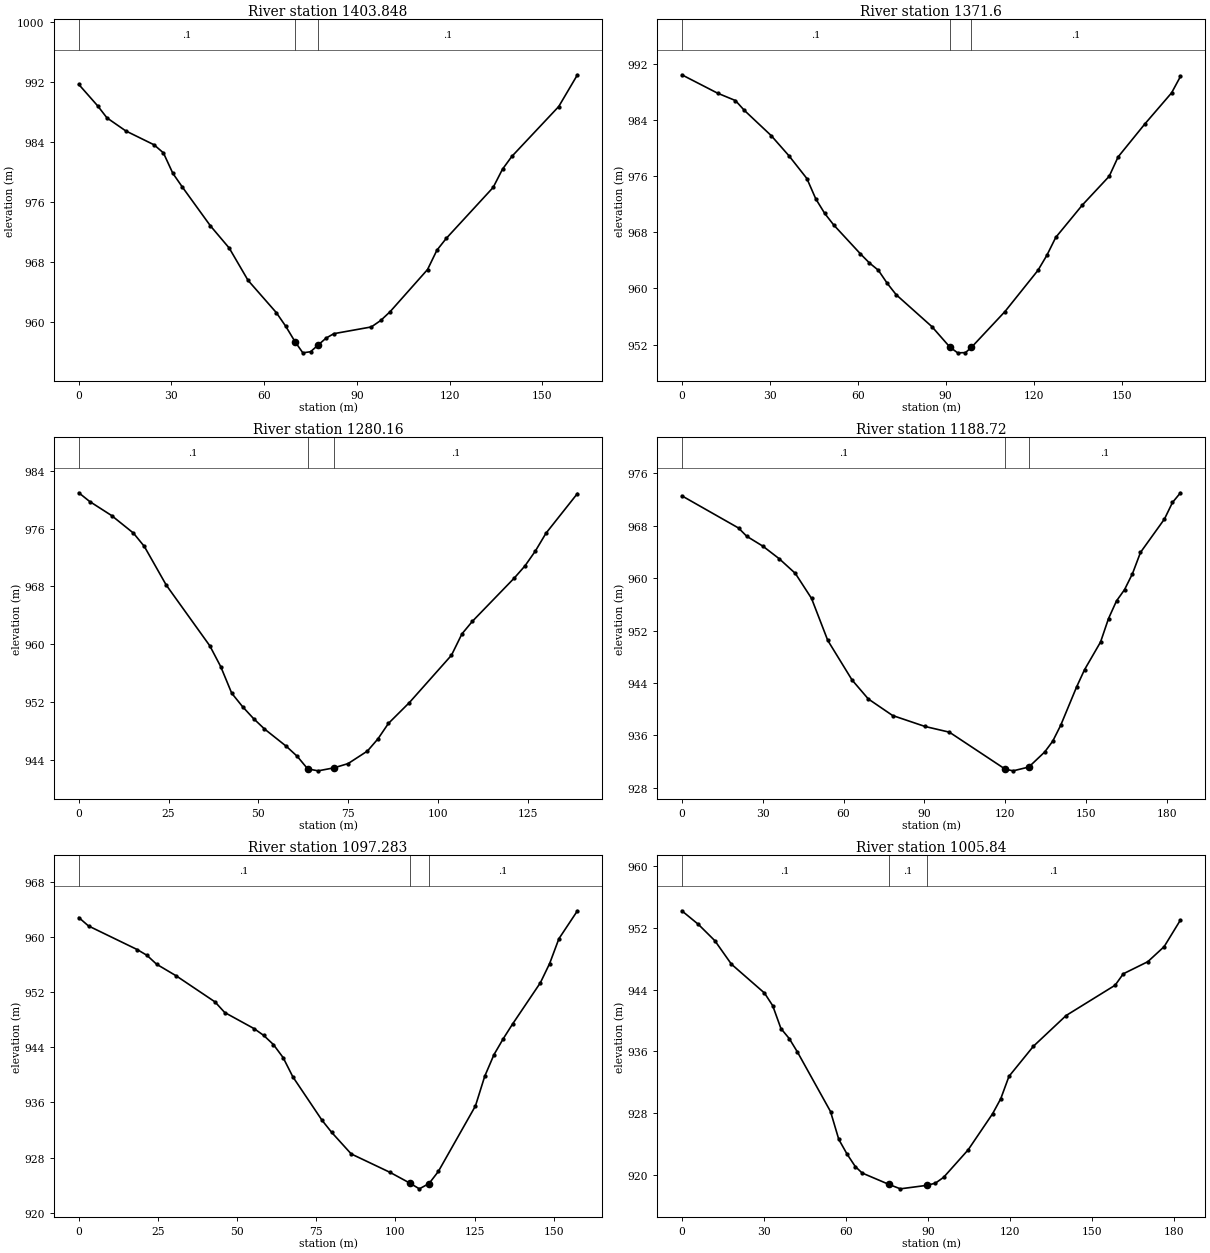
Type RM Length L Ch R = 1 ,1403.848,35.2,32.25,26.91
XS GIS Cut Line= 4
     641105.8504    4317198.5428     641038.7123    4317218.3865
      641026.806    4317222.3553      640948.423    4317230.9543
#Sta/Elev= 30
       0  991.71    6.09  988.86    9.13  987.24   15.22   985.5   24.35  983.65
   27.39  982.57   30.44  979.84   33.48  978.03   42.61  972.82    48.7  969.85
   54.79  965.54   63.92  961.24   66.97  959.42   70.01  957.34   72.52  955.86
   75.03  956.01   77.54  956.93   80.05  957.83   82.56  958.42   94.69  959.32
   97.72  960.18  100.76  961.35  112.89  966.99  115.92  969.57  118.95  971.15
  134.12  977.95  137.15  980.39  140.18   982.1  155.35  988.76  161.41     993
#Mann= 3 , 0 , 0
       0      .1       0   70.01      .1       0   77.54      .1       0
Bank Sta=70.01,77.54
XS Rating Curve= 0 ,0
Exp/Cntr=0.3,0.1

Type RM Length L Ch R = 1 ,1371.6  ,85.72,91.44,97.8
XS GIS Cut Line= 5
     641102.0561    4317146.3525     641021.3391    4317189.2352
     641011.9173    4317198.7057     641001.2516    4317207.2481
     640951.2433    4317220.1714
#Sta/Elev= 30
       0  990.44   12.19  987.82   18.28  986.77   21.33  985.37   30.47  981.78
   36.56  978.89   42.65  975.66    45.7  972.75   48.75  970.68   51.79  969.05
   60.93  964.92   63.98  963.63   67.03  962.59   70.07  960.72   73.12   959.1
   85.31  954.55    91.4  951.65   94.07  950.82   96.74  950.85    98.8  951.61
  110.23  956.71  121.46  962.57   124.5  964.71  127.54  967.27  136.65   971.9
  145.77  975.98  148.81  978.74  157.92  983.43  167.04  987.86  170.08  990.21
#Mann= 3 , 0 , 0
       0      .1       0    91.4      .1       0    98.8      .1       0
Bank Sta=91.4,98.8
XS Rating Curve= 0 ,0
Exp/Cntr=0.3,0.1

Type RM Length L Ch R = 1 ,1280.16 ,99.85,91.44,83.66
XS GIS Cut Line= 5
     641071.8936     4317100.315      641011.154    4317103.0275
     641002.5178    4317104.3769     640992.0818    4317107.1127
     640934.4022     4317116.657
#Sta/Elev= 30
       0  980.98    3.04  979.77    9.12  977.83    15.2   975.4   18.24  973.55
   24.32  968.21   36.48  959.77   39.52  956.88   42.56  953.22    45.6  951.34
   48.64   949.7   51.68  948.26   57.76  945.86    60.8  944.47   63.71  942.73
   66.63  942.46   71.05  942.88   74.94  943.46   80.33   945.2   83.25  946.88
   86.18  949.03   92.02  951.92  103.72  958.47  106.64  961.43  109.56  963.18
  121.25  969.19  124.18  970.85   127.1  972.93  130.02  975.37  138.79  980.88
#Mann= 3 , 0 , 0
       0      .1       0   63.71      .1       0   71.05      .1       0
Bank Sta=63.71,71.05
XS Rating Curve= 0 ,0
Exp/Cntr=0.3,0.1

Type RM Length L Ch R = 1 ,1188.72 ,85.92,91.44,99.57
XS GIS Cut Line= 5
     641069.5123    4316959.8209     640973.8529    4317016.7577
       640959.73    4317026.9862     640944.3175    4317040.7786
     640910.9338    4317053.1532
#Sta/Elev= 30
       0  972.56   21.06  967.64   24.07  966.39   30.09  964.87    36.1  962.97
   42.12  960.72   48.14   956.9   54.16  950.49   63.18  944.45    69.2  941.56
   78.23  939.03   90.26  937.36   99.29  936.49  120.04  930.84  122.95  930.59
  128.76  931.17  134.67  933.47  137.62   935.1  140.58  937.52  146.49  943.38
  149.44  946.02  155.38  950.24  158.34  953.82  161.31  956.52  164.28  958.23
  167.24  960.68  170.21  963.92  179.11  969.02  182.08  971.54  185.05  973.02
#Mann= 3 , 0 , 0
       0      .1       0  120.04      .1       0  128.76      .1       0
Bank Sta=120.04,128.76
XS Rating Curve= 0 ,0
Exp/Cntr=0.3,0.1

Type RM Length L Ch R = 1 ,1097.283,86.28,91.44,94.8
XS GIS Cut Line= 3
     641035.7117    4316930.2537     640925.5337    4316940.3677
     640879.2004    4316947.4272
#Sta/Elev= 30
       0  962.81    3.07  961.59   18.44  958.17   21.51  957.34   24.59  956.04
   30.73  954.37   43.03  950.58    46.1  949.04   55.32  946.72   58.39  945.73
   61.47   944.4   64.54  942.51   67.61  939.72   76.83  933.42   79.91  931.65
   86.05  928.54   98.35  925.86  104.49  924.33  107.57  923.48  110.64  924.25
  113.57     926  125.29   935.5  128.22   939.8  131.15  942.94  134.08  945.25
     137  947.36  145.79  953.35  148.72  956.14  151.65  959.74  157.51  963.79
#Mann= 3 , 0 , 0
       0      .1       0  104.49      .1       0  110.64      .1       0
Bank Sta=104.49,110.64
XS Rating Curve= 0 ,0
Exp/Cntr=0.3,0.1

Type RM Length L Ch R = 1 ,1005.84 ,101.2,91.44,82.37
XS GIS Cut Line= 6
     641016.5294    4316864.7692     640953.4743    4316857.4969
     640944.6186    4316852.6926     640938.5994    4316850.5022
     640932.0081    4316848.6009     640841.2426     4316818.467
#Sta/Elev= 30
       0  954.23    6.05  952.47   12.09  950.35   18.14  947.31   30.23  943.57
   33.25  941.93   36.27  938.96   39.29  937.67   42.32  935.91   54.41   928.2
   57.43  924.59   60.45  922.69   63.47  921.07   65.99  920.23   75.68  918.77
   79.95  918.18    89.8  918.64   92.79  918.92   95.78  919.67  104.75  923.23
  113.71  927.92   116.7  929.87  119.69  932.76  128.65  936.67  140.61  940.65
  158.54  944.58  161.53  946.06   170.5  947.63  176.47  949.58  182.45  953.04
#Mann= 3 , 0 , 0
       0      .1       0   75.68      .1       0    89.8      .1       0
Bank Sta=75.68,89.8
XS Rating Curve= 0 ,0
Exp/Cntr=0.3,0.1

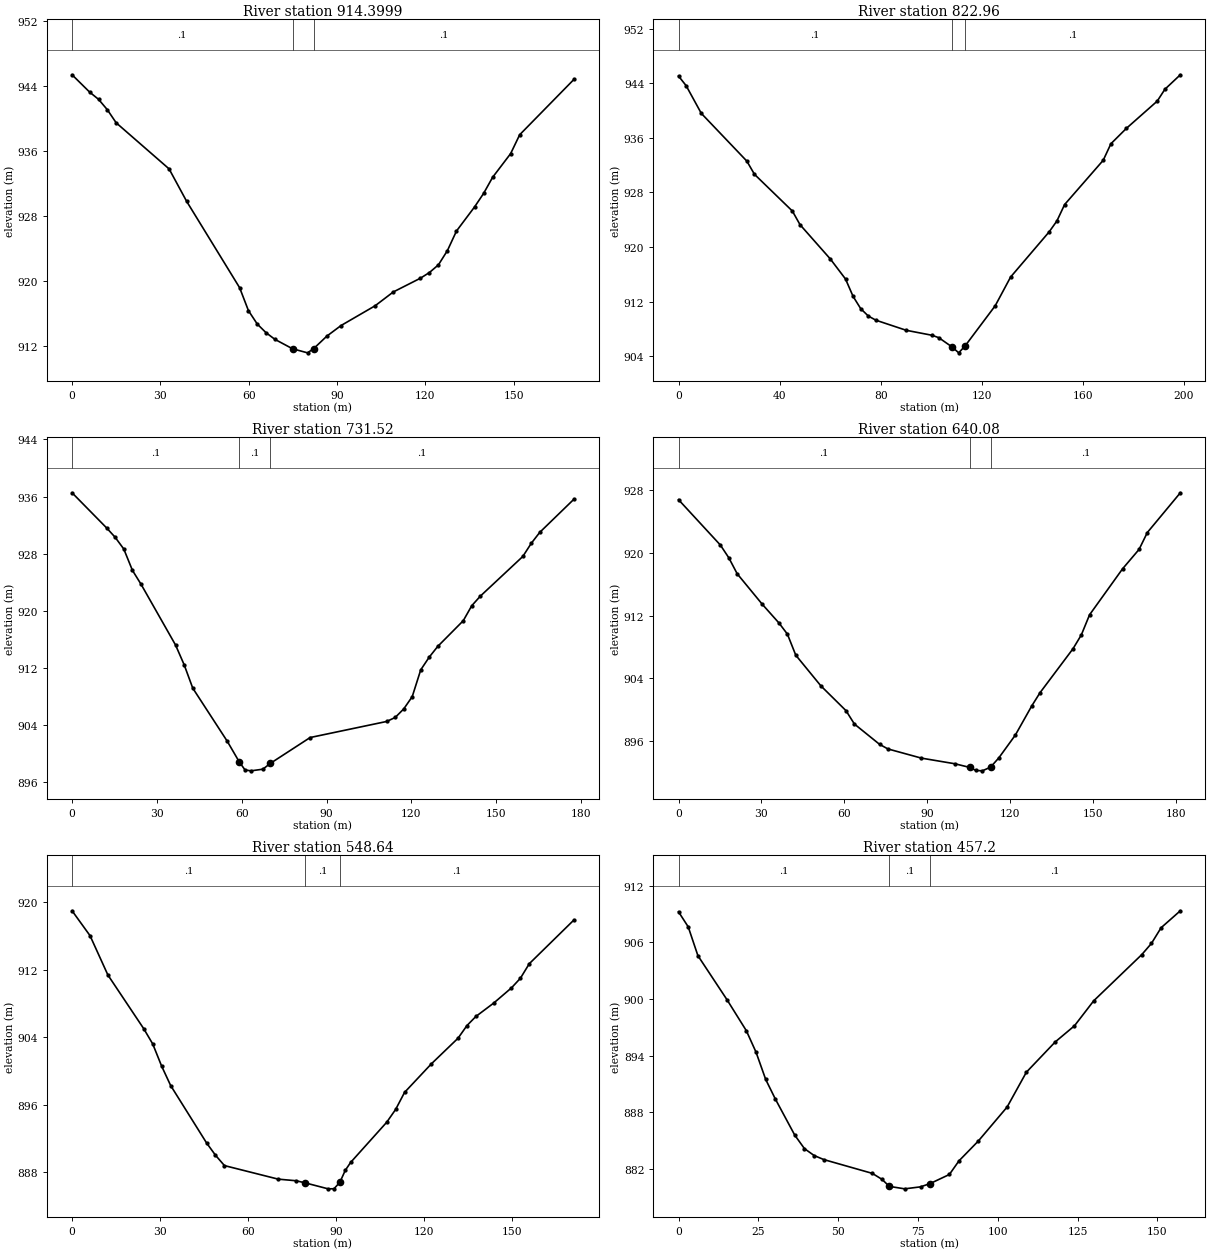
Type RM Length L Ch R = 1 ,914.3999,81.71,91.44,95.39
XS GIS Cut Line= 5
     641009.5597    4316736.2344      640937.411    4316765.5825
     640931.3728    4316767.2253     640923.1707    4316772.2524
     640849.6911    4316794.1496
#Sta/Elev= 30
       0  945.42    5.99  943.28    8.99   942.4   11.98  941.12   14.98  939.51
   32.95  933.84   38.94  929.83   56.92  919.21   59.91  916.39   62.91  914.74
   65.91  913.67    68.9  912.86   74.89   911.7   79.98   911.2   82.06  911.72
   86.55  913.26   91.36  914.56  102.97     917   109.1  918.69   118.3  920.38
  121.37  921.08  124.44  922.03   127.5  923.79  130.57  926.19   136.7  929.15
  139.77  930.81  142.84   932.8  148.97  935.72  152.04  938.04  170.44  944.84
#Mann= 3 , 0 , 0
       0      .1       0   74.89      .1       0   82.06      .1       0
Bank Sta=74.89,82.06
XS Rating Curve= 0 ,0
Exp/Cntr=0.3,0.1

Type RM Length L Ch R = 1 ,822.96  ,94.41,91.44,88.04
XS GIS Cut Line= 5
     641010.4019    4316700.6517     640918.1855    4316687.7615
     640911.0674    4316689.0369     640896.2976    4316683.4103
     640816.1071    4316664.3469
#Sta/Elev= 30
       0  945.04       3  943.64    9.01  939.58   27.03  932.59   30.04  930.66
   45.05  925.28   48.06  923.29   60.07  918.26   66.08  915.33   69.08  912.78
   72.09  910.99   75.09  909.91   78.09   909.3   90.11  907.82  100.34  907.09
  102.98  906.74  108.25  905.38  110.88  904.52  113.52  905.59  125.31  911.41
  131.41  915.62  146.68  922.24  149.73  923.83  152.78  926.23  168.05  932.71
   171.1  935.13  177.21  937.38  189.42  941.37  192.47  943.11  198.57  945.23
#Mann= 3 , 0 , 0
       0      .1       0  108.25      .1       0  113.52      .1       0
Bank Sta=108.25,113.52
XS Rating Curve= 0 ,0
Exp/Cntr=0.3,0.1

Type RM Length L Ch R = 1 ,731.52  ,96.53,91.44,82.84
XS GIS Cut Line= 6
     641014.2804    4316613.5247     640959.4048    4316612.8912
     640953.3631    4316611.1342     640947.3793    4316609.1936
     640936.9095    4316606.9475     640838.0676    4316597.6497
#Sta/Elev= 30
       0  936.54    12.2  931.63   15.24  930.31   18.29  928.67   21.34  925.69
   24.39  923.74   36.59  915.24   39.64  912.47   42.68   909.2   54.88  901.77
   59.07  898.92   61.17  897.75   63.27  897.63   67.46  897.86   70.14  898.68
   84.19  902.29  111.26  904.54  114.27   905.1  117.28  906.29  120.29  908.01
   123.3  911.76   126.3  913.54  129.31  915.04  138.34  918.64  141.35  920.74
  144.36  922.07   159.4  927.63  162.41  929.48  165.41  931.01  177.45  935.63
#Mann= 3 , 0 , 0
       0      .1       0   59.07      .1       0   70.14      .1       0
Bank Sta=59.07,70.14
XS Rating Curve= 0 ,0
Exp/Cntr=0.3,0.1

Type RM Length L Ch R = 1 ,640.08  ,85.33,91.44,95.06
XS GIS Cut Line= 4
      641028.568    4316506.6329     640927.3316    4316525.8708
     640920.4575    4316526.4108     640849.7093    4316537.8538
#Sta/Elev= 30
       0  926.75   15.15  920.97   18.18  919.36   21.22  917.32   30.31  913.43
   36.37  911.04    39.4  909.63   42.43  906.95   51.52  903.04   60.62  899.88
   63.65  898.18   72.74   895.6   75.77  895.01   87.89  893.84  100.02  893.12
  105.35  892.66  107.64  892.27  109.94  892.22  112.93  892.69  115.92  893.87
  121.89  896.77  127.86   900.5  130.85  902.18  142.79  907.78  145.78  909.53
  148.76  912.09  160.71  917.95  166.68  920.42  169.67  922.57  181.61  927.63
#Mann= 3 , 0 , 0
       0      .1       0  105.35      .1       0  112.93      .1       0
Bank Sta=105.35,112.93
XS Rating Curve= 0 ,0
Exp/Cntr=0.3,0.1

Type RM Length L Ch R = 1 ,548.64  ,91.49,91.44,95.59
XS GIS Cut Line= 6
      641025.393    4316463.2411     640945.5048    4316442.3527
     640940.9405    4316440.8984     640933.3961    4316439.4611
     640927.2373    4316440.4373     640861.8801     4316415.616
#Sta/Elev= 30
       0     919    6.12  916.05   12.23  911.37   24.47  904.99   27.52  903.19
   30.58  900.54   33.64  898.25   45.87  891.45   48.93  889.98   51.99  888.75
   70.34  887.14   76.46  886.95   79.52   886.7   87.36  885.99   89.37     886
   91.38  886.78   93.22  888.19   95.05  889.13  107.36   893.9   110.4  895.42
  113.44  897.44  122.56  900.82  131.68  903.87  134.72  905.37  137.76  906.45
  143.84  908.04  149.92  909.85  152.96  910.99     156  912.72   171.2   917.9
#Mann= 3 , 0 , 0
       0      .1       0   79.52      .1       0   91.38      .1       0
Bank Sta=79.52,91.38
XS Rating Curve= 0 ,0
Exp/Cntr=0.3,0.1

Type RM Length L Ch R = 1 ,457.2   ,98.34,91.44,87.9
XS GIS Cut Line= 5
     641033.1188    4316372.3389     640971.0392    4316357.9666
      640966.877    4316355.9143      640959.481    4316355.1358
      640879.131    4316342.1764
#Sta/Elev= 30
       0  909.25    3.03  907.66    6.07   904.6   15.17  899.94   21.24  896.65
   24.27  894.38   27.31  891.48   30.34   889.4   36.41  885.58   39.45  884.15
   42.48  883.42   45.52  882.99   60.69  881.53   63.72   880.9   66.04  880.15
   70.84  879.89    75.8   880.1   78.81  880.45   84.84  881.41   87.86  882.86
   93.89  884.95  102.93  888.56  108.96  892.25     118  895.46  124.03  897.17
  130.06  899.82  145.13  904.72  148.14   905.9  151.16  907.56  157.19  909.36
#Mann= 3 , 0 , 0
       0      .1       0   66.04      .1       0   78.81      .1       0
Bank Sta=66.04,78.81
XS Rating Curve= 0 ,0
Exp/Cntr=0.3,0.1

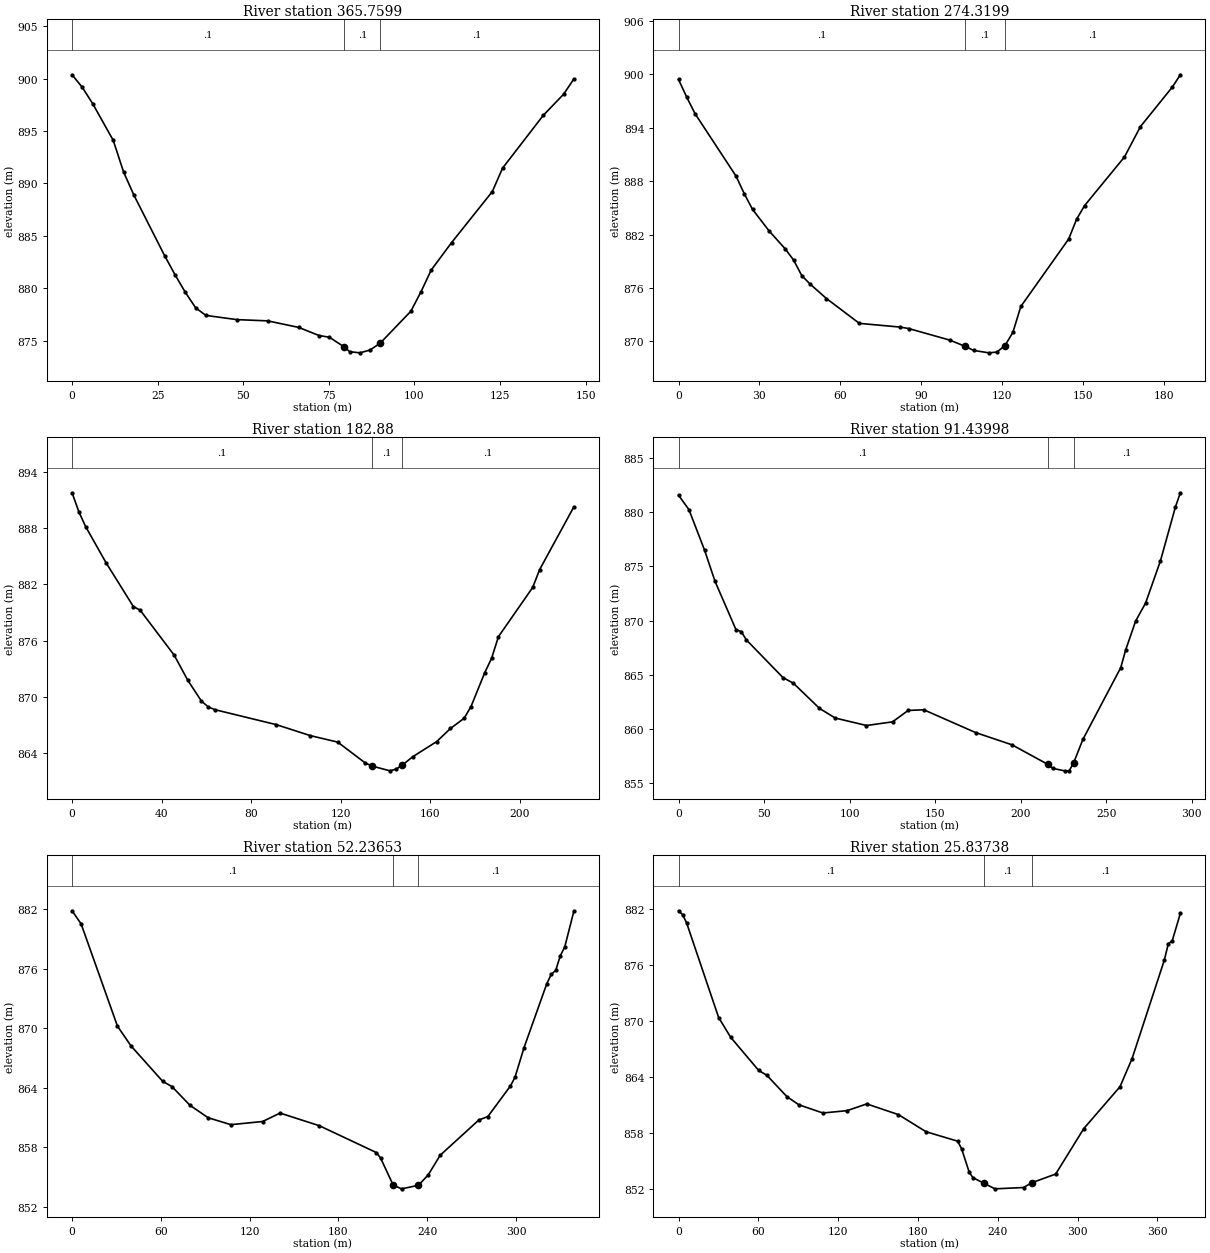
Type RM Length L Ch R = 1 ,365.7599,82.61,91.44,93.78
XS GIS Cut Line= 3
     641039.6706    4316250.7383     640968.5632    4316263.0385
     640896.1079    4316279.9213
#Sta/Elev= 30
       0  900.37    3.01  899.16    6.01  897.62   12.03  894.11   15.03  891.11
   18.04   888.9   27.06  883.09   30.07  881.29   33.07  879.62   36.08  878.14
   39.09  877.41   48.11  877.01   57.13  876.89   66.15  876.27   72.16  875.49
   75.14  875.33   79.55  874.39   81.09  873.95   84.07  873.84   87.04  874.11
   90.02  874.77   98.95  877.81  101.92  879.67   104.9  881.74  110.85  884.36
  122.75  889.23  125.73  891.46  137.63   896.5  143.58  898.52  146.56  899.97
#Mann= 3 , 0 , 0
       0      .1       0   79.55      .1       0   90.02      .1       0
Bank Sta=79.55,90.02
XS Rating Curve= 0 ,0
Exp/Cntr=0.3,0.1

Type RM Length L Ch R = 1 ,274.3199,106.66,91.44,86.59
XS GIS Cut Line= 4
     641055.3218    4316203.6226      640957.518    4316180.0583
     640943.7294    4316175.4929     640872.7589    4316177.1642
#Sta/Elev= 30
       0  899.42    3.05  897.43     6.1  895.59   21.34  888.56   24.39  886.58
   27.44  884.83   33.53  882.43   39.63  880.37   42.68  879.13   45.73  877.38
   48.78  876.44   54.87  874.81   67.07  872.02   82.31   871.6   85.36  871.44
   100.6  870.14  106.41  869.43  109.43  868.98  115.13  868.71  118.09   868.8
  121.04  869.51     124     871  126.96  873.92  144.71   881.5  147.66  883.73
  150.62  885.26  165.41  890.72  171.33  894.13  183.16  898.57  186.12  899.95
#Mann= 3 , 0 , 0
       0      .1       0  106.41      .1       0  121.04      .1       0
Bank Sta=106.41,121.04
XS Rating Curve= 0 ,0
Exp/Cntr=0.3,0.1

Type RM Length L Ch R = 1 ,182.88  ,98.81,91.44,79.32
XS GIS Cut Line= 6
     641082.4417    4316147.3985     640993.7671    4316078.1726
      640974.082    4316086.8509     640960.8262    4316088.5768
     640952.4391    4316092.6982     640885.9881    4316103.7422
#Sta/Elev= 30
       0  891.76    3.04  889.73    6.08  888.15    15.2   884.3   27.36  879.65
    30.4  879.26   45.61  874.47   51.69  871.79   57.77  869.58   60.81  868.96
   63.85  868.66   91.21  867.07  106.42   865.9  118.64  865.21  130.94  862.99
  134.01  862.66  141.97  862.15  144.69  862.33  147.41  862.74  152.08  863.64
  162.88  865.27     169  866.66  175.13  867.75  178.19     869  184.31   872.6
  187.37  874.13  190.44  876.44  205.74  881.68  208.81  883.57  224.12  890.26
#Mann= 3 , 0 , 0
       0      .1       0  134.01      .1       0  147.41      .1       0
Bank Sta=134.01,147.41
XS Rating Curve= 0 ,0
Exp/Cntr=0.3,0.1

Type RM Length L Ch R = 1 ,91.43998,24.57,39.2,58.14
XS GIS Cut Line= 6
     641070.5354     4316130.862     641020.8607    4316015.9985
     640964.6011    4315985.7358     640938.4073    4315999.7058
     640923.4848    4316022.8833     640883.3423    4316046.1952
#Sta/Elev= 30
       0  881.56     6.1  880.22   15.26  876.47   21.37   873.6   33.58  869.16
   36.63  868.98   39.68  868.21   61.05  864.74   67.15  864.22   82.41   861.9
   91.57  861.01  109.88  860.32  125.14  860.66  134.27  861.71   143.4  861.77
  173.82  859.66  194.96  858.54  215.74  856.75  218.71  856.37  225.69  856.14
  228.38  856.14  231.06   856.9  236.38  859.03  258.55  865.66  261.46  867.31
  267.26  869.96  273.06  871.61  281.76  875.51  290.47  880.45  293.37  881.78
#Mann= 3 , 0 , 0
       0      .1       0  215.74      .1       0  231.06      .1       0
Bank Sta=215.74,231.06
XS Rating Curve= 0 ,0
Exp/Cntr=0.3,0.1

Type RM Length L Ch R = 1 ,52.23653,17.35,26.4,34.57
XS GIS Cut Line= 6
     641075.4178    4316129.7915     641021.8396    4316012.7132
     640959.1332    4315968.2631     640933.7232    4315967.7339
     640905.6773    4315963.7651     640849.1666    4316019.7246
#Sta/Elev= 30
       0  881.83    6.13   880.5   30.66   870.2   39.85   868.2   61.31  864.62
   67.44  864.11   79.71  862.21   91.97  860.96   107.3  860.26  128.76  860.58
  140.58  861.43  167.19  860.15  205.62  857.45  208.46  856.91  216.99  854.17
  222.68  853.79  234.11  854.15  240.69   855.2  248.79  857.18  274.88  860.73
  280.99  861.08  296.29  864.17  299.35  865.05  305.46  868.04  320.76  874.45
  323.82  875.42  326.88  875.83  329.94  877.29  332.99   878.2  339.11  881.79
#Mann= 3 , 0 , 0
       0      .1       0  216.99      .1       0  234.11      .1       0
Bank Sta=216.99,234.11
XS Rating Curve= 0 ,0
Exp/Cntr=0.3,0.1

Type RM Length L Ch R = 1 ,25.83738,8.4,25.84,10.09
XS GIS Cut Line= 6
     641077.4628    4316128.9122     641022.7733    4316011.4105
     640960.3844    4315952.0026     640943.2923    4315944.0122
     640923.9248     4315928.878     640846.9926    4316018.1839
#Sta/Elev= 30
       0  881.76    3.01  881.35    6.03  880.48   30.14  870.36   39.18  868.25
   60.28   864.7   66.31   864.2   81.38  861.92   90.42  861.04  108.51  860.16
  126.59  860.41  141.49  861.13  165.25  859.99  186.05  858.16  209.81  857.15
  212.78  856.34  218.54  853.82  221.33  853.25  229.49  852.66  237.85  852.06
  259.32   852.2  265.36   852.7   283.5  853.64  304.65   858.5  331.85  862.97
  340.92  865.97   365.1  876.46  368.12  878.22  371.14  878.57  377.19  881.47
#Mann= 3 , 0 , 0
       0      .1       0  229.49      .1       0  265.36      .1       0
Bank Sta=229.49,265.36
XS Rating Curve= 0 ,0
Exp/Cntr=0.3,0.1

River Reach=UnnamedTrib(Red),1
Reach XY= 30
     633302.0188    4316648.8901     633245.5798    4316599.8906
     633184.2678    4316582.8915633144.790733996 4316520.6580885
     633144.5049    4316493.3553      633163.555    4316465.1771
     633167.1269    4316417.9489633121.4033464894316293.60206749
633103.8241829714316159.59855053633076.0767929774316138.39864351
633057.138889497 4316103.3519225633079.165613487  4316071.911778
633068.775467495  4316027.131756633092.6843224994316005.84210099
     633095.2923    4315992.8949     633078.7712    4315942.8869
     633101.2455    4315892.8822     633031.3953    4315707.1444
     633027.8235    4315618.2442     633002.9923    4315558.1084
     632998.2356    4315484.0887     632986.9453    4315473.7814
     632986.1515    4315434.0938     632975.4359    4315404.3281
     632906.3795    4315259.4685     632892.8857    4315247.9591
     632839.7043    4315244.3872     632809.9387    4315230.8934
     632771.0448    4315240.4184     632755.1003    4315225.6854

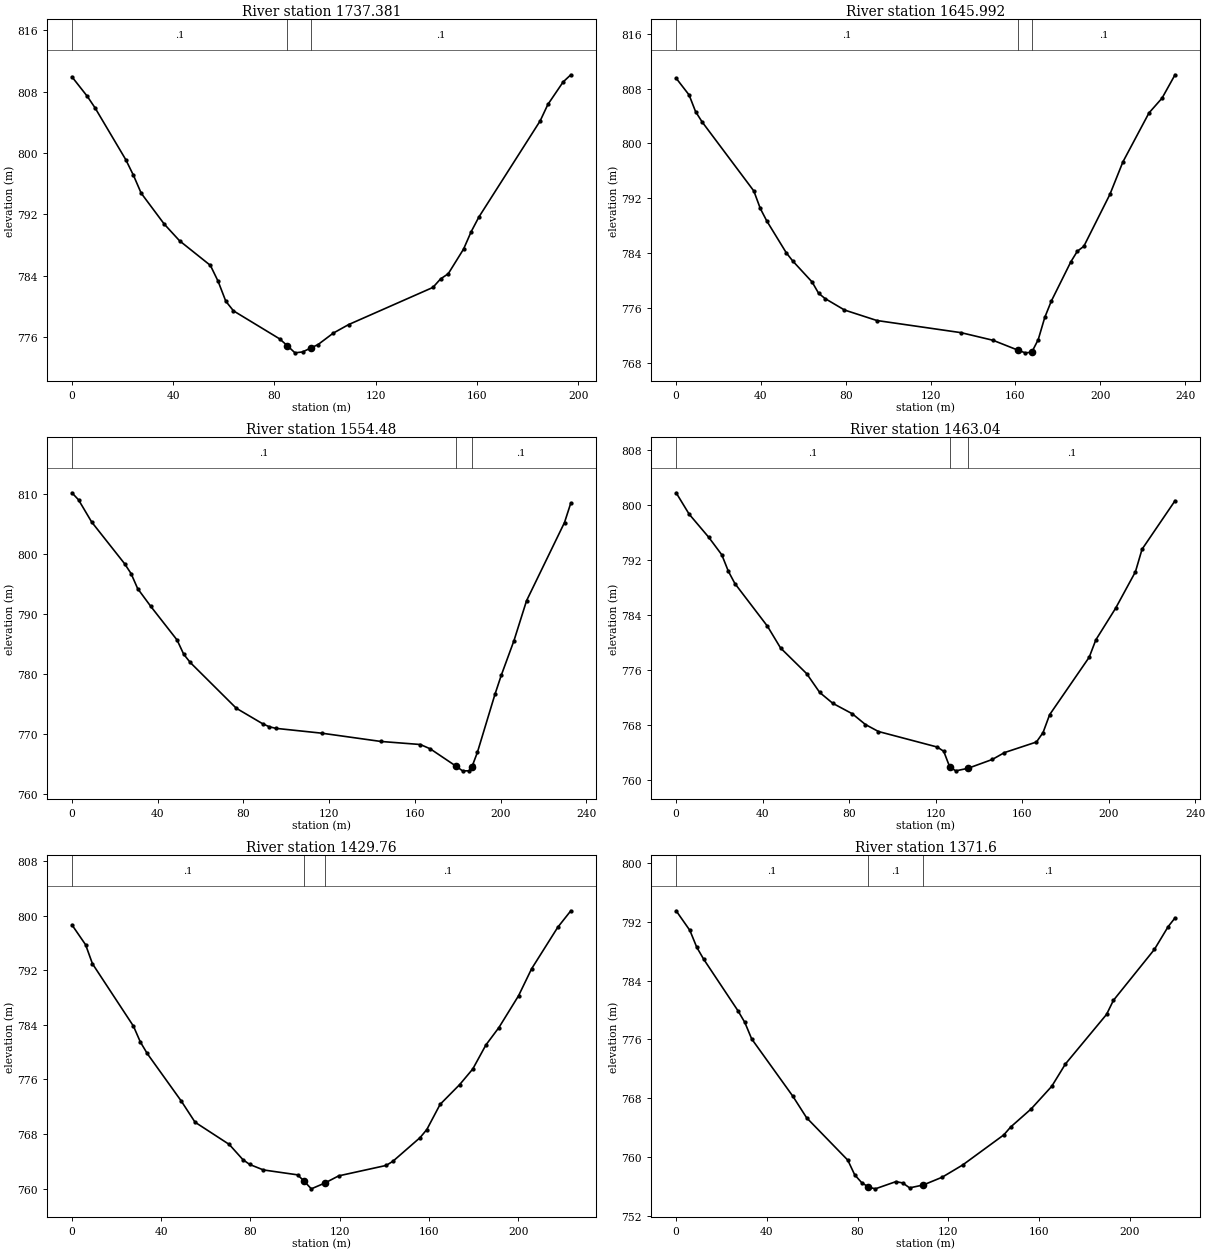
Type RM Length L Ch R = 1 ,1737.381,91.02,91.39,88.49
XS GIS Cut Line= 3
      633337.054    4316561.2788     633273.6233    4316618.0245
     633194.8616    4316697.6801
#Sta/Elev= 30
       0  809.92    6.08  807.37    9.12  805.88   21.28  799.12   24.32  797.08
   27.36  794.76   36.48  790.73   42.55  788.55   54.71  785.35   57.75  783.29
   60.79  780.69   63.83  779.43   82.07  775.78   85.11  774.89   88.14  773.96
   91.16  774.08   94.49  774.61   97.22  775.03  103.27  776.53  109.33  777.64
  142.63  782.48  145.66  783.59  148.69  784.26  154.74  787.47  157.77  789.75
   160.8  791.65  185.02  804.18  188.05  806.31   194.1  809.25  197.13  810.18
#Mann= 3 , 0 , 0
       0      .1       0   85.11      .1       0   94.49      .1       0
Bank Sta=85.11,94.49
XS Rating Curve= 0 ,0
Exp/Cntr=0.3,0.1

Type RM Length L Ch R = 1 ,1645.992,73.67,91.51,98.44
XS GIS Cut Line= 4
     633315.5118    4316483.3671     633203.6526    4316568.3148
     633193.5663    4316579.3267     633153.5865    4316648.4675
#Sta/Elev= 30
       0  809.51    6.11  807.07    9.16  804.65   12.21  803.16   36.64  793.08
   39.69  790.53   42.75  788.71   51.91  784.09   54.96  782.89   64.12  779.82
   67.18  778.18   70.23  777.41   79.39  775.74   94.66  774.21  134.35  772.44
  149.42  771.33  161.19  769.89  164.61   769.5  167.68  769.58  170.75  771.43
  173.82  774.65  176.89  777.02  186.11  782.75  189.18   784.3  192.25  785.02
  204.54  792.58  210.68  797.32  222.97  804.45  229.12   806.6  235.26  810.01
#Mann= 3 , 0 , 0
       0      .1       0  161.19      .1       0  167.68      .1       0
Bank Sta=161.19,167.68
XS Rating Curve= 0 ,0
Exp/Cntr=0.3,0.1

Type RM Length L Ch R = 1 ,1554.48 ,86.56,91.44,94.4
XS GIS Cut Line= 6
     633317.8931    4316462.7296     633163.3635    4316513.0291
     633158.9979     4316511.521     633139.5427    4316512.3514
     633135.0953    4316513.2122     633096.4364    4316527.8172
#Sta/Elev= 30
       0  810.27    3.07   809.1     9.2   805.4   24.53  798.46    27.6  796.79
   30.66  794.29   36.79  791.32   49.06  785.71   52.13  783.35   55.19  781.97
   76.66  774.34   88.92  771.76   91.99  771.26   95.05  770.99  116.52  770.18
  144.11   768.8  162.51  768.29  167.13  767.57  179.19  764.67   182.2   763.9
  185.22   763.9  186.47  764.61  186.84  764.82  189.11  766.97  197.32  776.67
  200.27  779.85  206.17   785.6  212.06  792.28  229.75  805.31   232.7  808.57
#Mann= 3 , 0 , 0
       0      .1       0  179.19      .1       0  186.47      .1       0
Bank Sta=179.19,186.47
XS Rating Curve= 0 ,0
Exp/Cntr=0.3,0.1

Type RM Length L Ch R = 1 ,1463.04 ,36.59,33.28,34.79
XS GIS Cut Line= 5
     633298.8959    4316430.7502     633175.1866    4316429.3493
     633158.3271    4316429.5802     633143.7645    4316438.0725
     633071.0039    4316446.3408
#Sta/Elev= 30
       0  801.79    6.03  798.67   15.09   795.3   21.12  792.75   24.14  790.36
   27.16  788.57   42.24  782.34   48.28  779.18   60.35  775.44   66.38   772.7
   72.42  771.12   81.47  769.59   87.51  768.03   93.54  767.01   120.7  764.75
  123.72  764.13  126.53  761.82  129.34  761.28  134.96  761.65   146.2  762.94
  151.82  763.94  166.59  765.48  169.64  766.85  172.69  769.46     191  777.84
  194.05  780.36   203.2  784.97  212.36  790.28  215.41  793.56  230.67  800.63
#Mann= 3 , 0 , 0
       0      .1       0  126.53      .1       0  134.96      .1       0
Bank Sta=126.53,134.96
XS Rating Curve= 0 ,0
Exp/Cntr=0.3,0.1

Type RM Length L Ch R = 1 ,1429.76 ,59.96,58.16,58.99
XS GIS Cut Line= 4
     633270.6586    4316370.2378     633151.5959    4316399.3421
     633113.2312    4316408.6025     633053.0384    4316421.1702
#Sta/Elev= 30
       0  798.67    6.13  795.75    9.19  792.97   27.58  783.81   30.64  781.51
   33.71  779.82   49.03  772.82   55.16  769.74   70.48  766.48   76.61  764.25
   79.67  763.54    85.8  762.74  101.12  762.02  104.18  761.05  107.25  759.97
  113.38  760.83   119.5  761.87  140.78   763.4  143.82  764.01  155.96  767.47
     159  768.66  164.96  772.35  173.75  775.26   179.6  777.54  185.46  781.05
  191.32  783.62   200.1  788.27  205.96  792.23  217.67  798.31  223.53  800.73
#Mann= 3 , 0 , 0
       0      .1       0  104.18      .1       0  113.38      .1       0
Bank Sta=104.18,113.38
XS Rating Curve= 0 ,0
Exp/Cntr=0.3,0.1

Type RM Length L Ch R = 1 ,1371.6  ,76.05,91.44,94.85
XS GIS Cut Line= 4
     633236.8729    4316305.3445     633132.5597    4316346.2777
     633127.3559    4316347.0204     633030.0787    4316379.9501
#Sta/Elev= 30
       0   793.5    6.06  790.83    9.09  788.54   12.11  786.93   27.26   779.9
   30.29  778.31   33.31  776.07   51.49  768.26   57.54  765.34   75.71  759.57
   78.74  757.58   81.77  756.53    84.8  755.91   87.83  755.67   96.91  756.65
   99.94  756.47  102.97   755.8  109.03   756.2  117.31  757.25  126.38  758.92
   144.5  763.01  147.52  764.08  156.58  766.55  165.64  769.62  171.68  772.66
  189.81   779.4  192.83  781.31  210.95  788.26  216.99  791.35  220.01  792.53
#Mann= 3 , 0 , 0
       0      .1       0    84.8      .1       0  109.03      .1       0
Bank Sta=84.8,109.03
XS Rating Curve= 0 ,0
Exp/Cntr=0.3,0.1

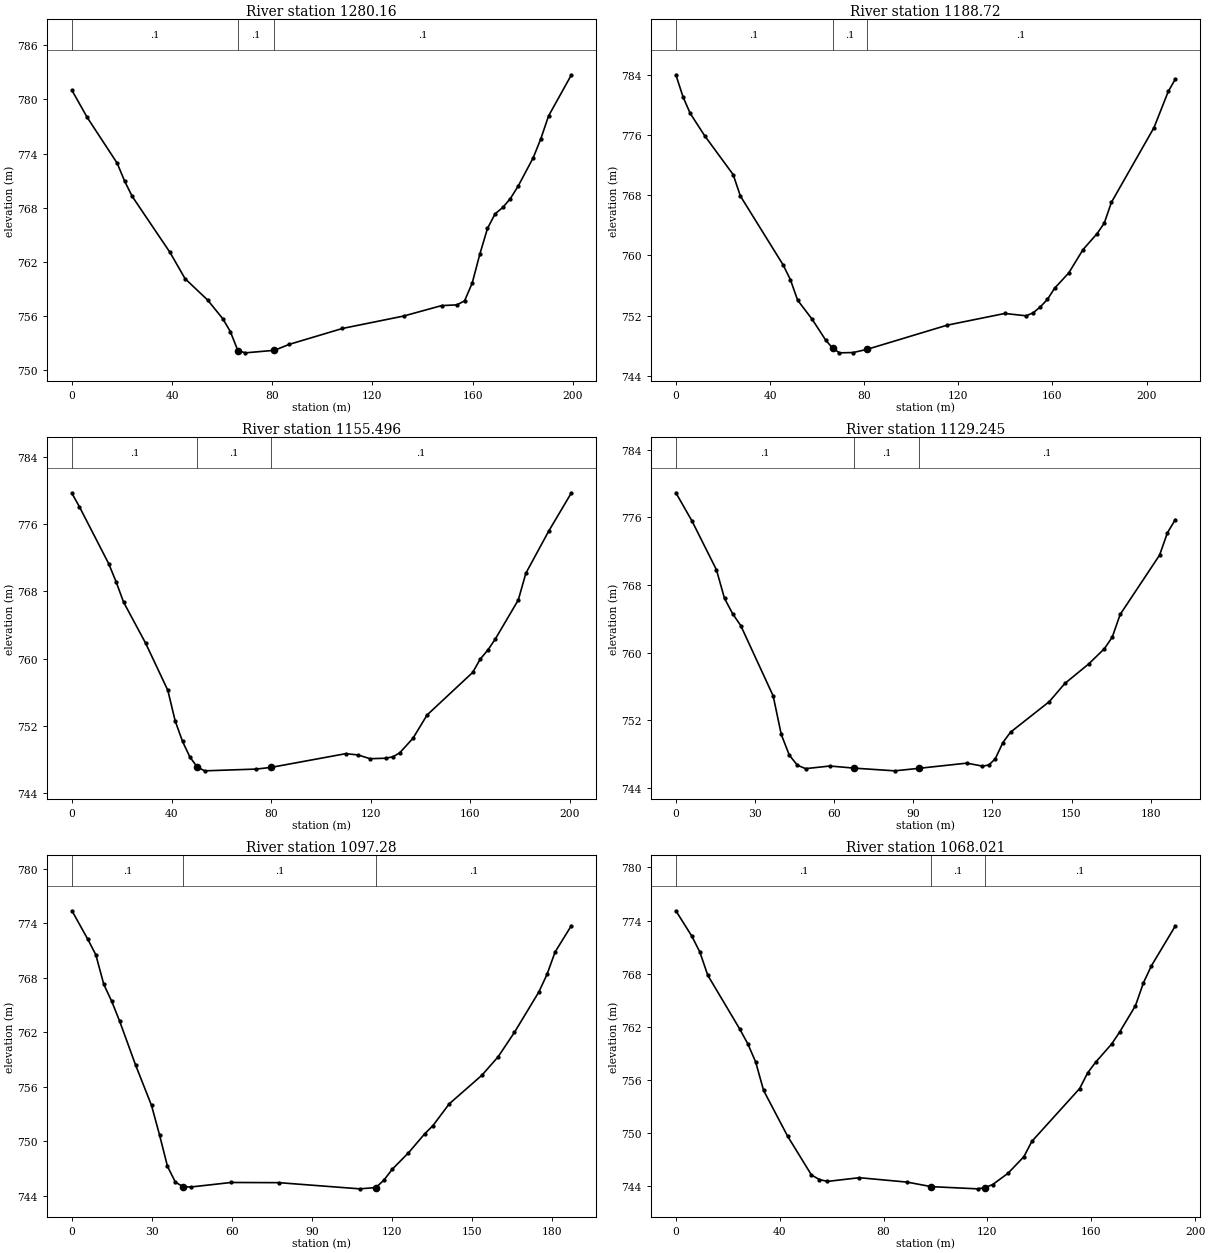
Type RM Length L Ch R = 1 ,1280.16 ,99.16,91.44,63.86
XS GIS Cut Line= 5
      633194.385    4316257.8438     633125.9201    4316268.3708
     633111.4341     4316267.392     633099.8405    4316264.0218
      632996.212    4316265.6499
#Sta/Elev= 30
       0  781.01    6.02  778.04   18.07  772.94   21.08  770.93   24.09  769.26
   39.15  763.07   45.18  760.16   54.21  757.79   60.23  755.73   63.25  754.31
   66.26   752.2   69.27  751.95   80.88  752.23   86.81  752.89  108.06  754.65
  132.44  756.02  147.68  757.18  153.78  757.26  156.83  757.71  159.88  759.68
  162.92  762.88  165.97  765.72  169.02  767.34  172.07  768.04  175.12  769.03
  178.17  770.38  184.26  773.56  187.31  775.67  190.36  778.17   199.5  782.73
#Mann= 3 , 0 , 0
       0      .1       0   66.26      .1       0   80.88      .1       0
Bank Sta=66.26,80.88
XS Rating Curve= 0 ,0
Exp/Cntr=0.3,0.1

Type RM Length L Ch R = 1 ,1188.72 ,25.48,33.22,34.61
XS GIS Cut Line= 6
     633169.9347    4316143.2278     633114.4791    4316168.2661
     633083.2053    4316198.2699      633073.055     4316202.216
      633060.504    4316214.9387     632986.8638    4316242.0926
#Sta/Elev= 30
       0  783.98    3.04  781.04    6.08  778.86   12.17  775.91   24.34  770.72
   27.38  767.89   45.63  758.69   48.68  756.74   51.72  754.04    57.8  751.54
   63.74  748.69   66.62  747.66   69.51  747.04   75.29  747.08   81.07  747.49
  115.29  750.72  139.75  752.27  148.81  751.96  151.82  752.36  154.84  753.15
  157.86  754.14  160.88  755.61  166.92  757.66  172.96  760.75  178.99  762.89
  182.01  764.28  185.03  767.03  203.14  776.97  209.18  781.76   212.2  783.41
#Mann= 3 , 0 , 0
       0      .1       0   66.62      .1       0   81.07      .1       0
Bank Sta=66.62,81.07
XS Rating Curve= 0 ,0
Exp/Cntr=0.3,0.1

Type RM Length L Ch R = 1 ,1155.496,9.57,26.25,34.05
XS GIS Cut Line= 6
      633166.648    4316133.3595     633092.8291    4316155.3199
     633064.5186    4316172.2533     633055.2581    4316175.4283
     633039.2508    4316186.6731     632979.3694    4316198.4306
#Sta/Elev= 30
       0  779.63    2.96  778.06   14.81  771.25   17.77   769.1   20.74  766.71
   29.62  761.82   38.51  756.24   41.47   752.6   44.43  750.16   47.39  748.31
   50.36  747.12   53.32  746.67   74.05  746.88   80.02  747.08     110  748.71
   114.9  748.56  119.79  748.11  126.18  748.17  129.04  748.35  131.69  748.81
  136.99  750.53  142.69  753.31     161  758.36  164.05  759.95   167.1  761.02
  170.15  762.36  179.31  766.96  182.36  770.14  191.51  775.13  200.67   779.7
#Mann= 3 , 0 , 0
       0      .1       0   50.36      .1       0   80.02      .1       0
Bank Sta=50.36,80.02
XS Rating Curve= 0 ,0
Exp/Cntr=0.3,0.1

Type RM Length L Ch R = 1 ,1129.245,32.81,31.96,29.57
XS GIS Cut Line= 6
     633165.7081    4316129.8447     633069.7965    4316151.6728
     633051.9371    4316152.0697       633047.11    4316151.4902
      633032.887    4316148.8947     632979.1765    4316152.3343
#Sta/Elev= 30
       0  778.89    6.15  775.53   15.37  769.79   18.44   766.4   21.52  764.59
   24.59  763.19   36.89  754.87   39.96  750.31   43.03  747.85   46.11  746.67
   49.18  746.27    58.4  746.58   67.63  746.33   82.99  746.01   92.22  746.31
  110.27  746.92  116.23  746.57  118.66   746.7  121.09  747.43  123.98  749.35
  126.87  750.58  141.53  754.18  147.51  756.35  156.48  758.64  162.46  760.45
  165.45  761.82  168.44   764.5  183.39  771.52  186.38  774.17  189.37  775.72
#Mann= 3 , 0 , 0
       0      .1       0   67.63      .1       0   92.22      .1       0
Bank Sta=67.63,92.22
XS Rating Curve= 0 ,0
Exp/Cntr=0.3,0.1

Type RM Length L Ch R = 1 ,1097.28 ,22.67,29.26,36.17
XS GIS Cut Line= 3
     633162.6953    4316101.3746     633074.4986    4316116.5758
      632977.957     4316131.674
#Sta/Elev= 30
       0  775.36    5.97  772.21    8.95  770.51   11.93  767.26   14.92  765.38
    17.9  763.18   23.87  758.36   29.83  753.92   32.82  750.68    35.8  747.22
   38.78  745.47   41.77  744.96   44.75  744.95   59.66  745.44   77.56  745.42
  107.82  744.74  113.93  744.88  116.98  745.72  120.03  746.89  126.14  748.71
  132.25  750.81   135.3   751.7  141.41   754.1  153.62  757.24  159.73  759.28
  165.84  761.97     175  766.42  178.05  768.35   181.1  770.83  187.21  773.73
#Mann= 3 , 0 , 0
       0      .1       0   41.77      .1       0  113.93      .1       0
Bank Sta=41.77,113.93
XS Rating Curve= 0 ,0
Exp/Cntr=0.3,0.1

Type RM Length L Ch R = 1 ,1068.021,26.97,25.85,19.29
XS GIS Cut Line= 4
     633165.5758     4316084.592     633061.5944    4316094.5139
       633040.56    4316084.1951      632976.663    4316092.9264
#Sta/Elev= 30
       0   775.1    6.14  772.23    9.22  770.44   12.29   767.8   24.58  761.73
   27.65  760.08   30.72     758   33.79  754.77   43.01  749.61   52.23   745.2
    55.3  744.69   58.37  744.48   70.66   744.9   89.09   744.4   98.31  743.89
  116.17  743.64   119.1  743.78  122.03  744.13  127.88  745.39  134.02  747.27
   137.1  749.01  155.52  754.99  158.59  756.76  161.66  757.96  167.81  760.02
  170.88  761.36  177.02  764.37  180.09  766.96  183.16  768.88  192.37  773.39
#Mann= 3 , 0 , 0
       0      .1       0   98.31      .1       0   119.1      .1       0
Bank Sta=98.31,119.1
XS Rating Curve= 0 ,0
Exp/Cntr=0.3,0.1

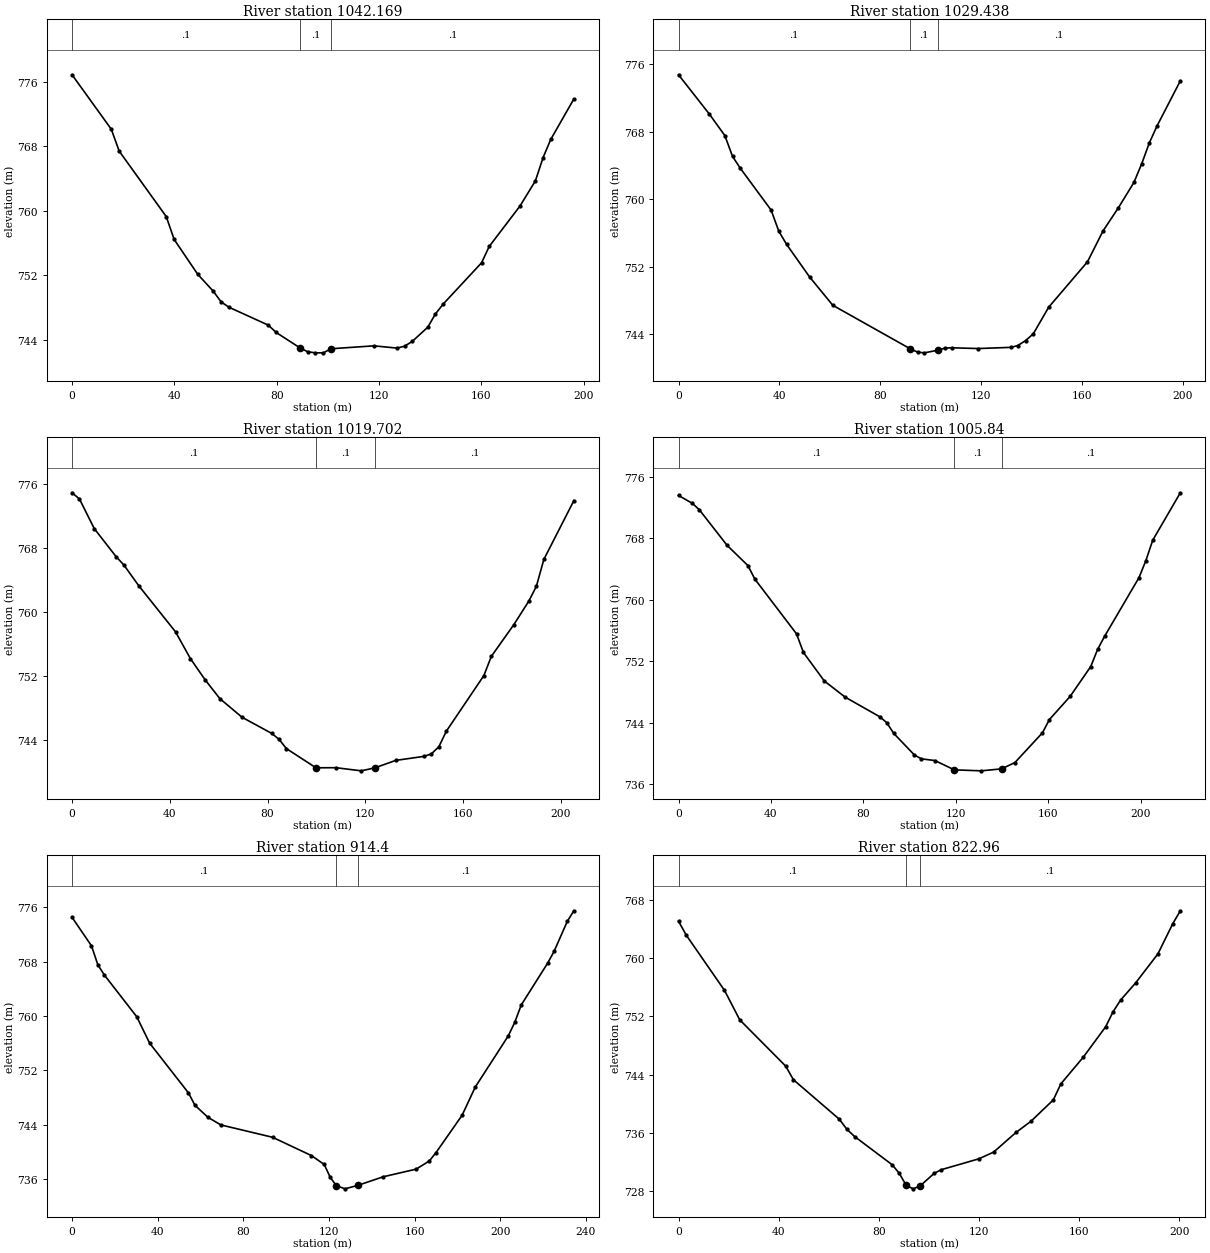
Type RM Length L Ch R = 1 ,1042.169,12.18,12.73,12.33
XS GIS Cut Line= 6
     633175.4977     4316062.367     633074.2944    4316065.9388
     633066.6744    4316067.7645     633062.0706     4316068.082
     633058.1019    4316069.6695     632979.9967    4316072.8445
#Sta/Elev= 30
       0   776.9   15.34  770.13   18.41  767.42   36.82  759.28   39.89  756.45
    49.1  752.12   55.24  749.99    58.3  748.67   61.37  748.01   76.72  745.79
   79.79  744.88   88.99  742.99   92.06  742.49   95.13  742.35    98.2  742.35
  101.27  742.86  117.99  743.22  127.01  742.94  130.02  743.18  133.02  743.78
  139.04  745.53  142.04  747.18  145.05   748.4  160.08  753.54  163.09  755.58
  175.12   760.6  181.13  763.72  184.13  766.61  187.14  768.88  196.16  773.89
#Mann= 3 , 0 , 0
       0      .1       0   88.99      .1       0  101.27      .1       0
Bank Sta=88.99,101.27
XS Rating Curve= 0 ,0
Exp/Cntr=0.3,0.1

Type RM Length L Ch R = 1 ,1029.438,10.01,9.74,9.01
XS GIS Cut Line= 6
     633178.7571    4316053.1773     633083.9038    4316053.1773
     633065.6475    4316055.2014       633062.79    4316055.0956
     633044.7983    4316059.4347      632980.395    4316062.1511
#Sta/Elev= 30
       0  774.78   12.24  770.11   18.36  767.57   21.42   765.1   24.48   763.7
   36.72  758.73   39.78  756.22   42.84  754.67   52.02  750.78    61.2  747.43
   91.79  742.29   94.85  741.87   97.56  741.79  102.98  742.11  105.69  742.35
   108.4  742.39  118.74   742.3  131.96  742.44   134.6  742.66  137.67  743.24
  140.74  744.05  146.88  747.22  162.23  752.59  168.37  756.24  174.51  759.01
  180.64     762  183.71   764.2  186.78  766.71  189.85  768.73  199.06  774.06
#Mann= 3 , 0 , 0
       0      .1       0   91.79      .1       0  102.98      .1       0
Bank Sta=91.79,102.98
XS Rating Curve= 0 ,0
Exp/Cntr=0.3,0.1

Type RM Length L Ch R = 1 ,1019.702,13.99,13.86,13.96
XS GIS Cut Line= 5
     633185.9008    4316045.6367       633083.11    4316043.2554
     633067.6319    4316044.4461     633045.8037    4316050.0023
     632981.5098     4316054.368
#Sta/Elev= 30
       0  774.85    3.02  774.08    9.07  770.39   18.14  766.85   21.17  765.87
   27.22   763.3   42.34  757.53   48.39  754.21   54.43  751.56   60.48  749.21
   69.55  746.89   81.65  744.89   84.67  744.15    87.7  742.99   99.79   740.6
  107.99  740.61  118.34  740.22  123.97   740.6  132.42  741.52  143.94  742.02
     147  742.33  150.07  743.22  153.14  745.16  168.48  752.08  171.55  754.48
  180.76  758.43   186.9  761.37  189.97   763.2  193.03  766.55  205.31  773.87
#Mann= 3 , 0 , 0
       0      .1       0   99.79      .1       0  123.97      .1       0
Bank Sta=99.79,123.97
XS Rating Curve= 0 ,0
Exp/Cntr=0.3,0.1

Type RM Length L Ch R = 1 ,1005.84 ,89.74,91.44,77.09
XS GIS Cut Line= 5
     633192.5828    4316039.9929     633084.5287    4316035.8011
     633076.9084    4316027.5452     633051.5688    4316034.3325
     632981.4449    4316048.7242
#Sta/Elev= 30
       0  773.56    6.01  772.53    9.01   771.7   21.03  767.07   30.04  764.44
   33.04  762.68   51.06  755.57   54.07  753.14   63.08  749.44   72.09  747.34
   87.11  744.78   90.11  744.02   93.12  742.63  102.13   739.8  105.13  739.31
  110.94  739.09  119.37  737.88  131.03  737.75  139.88  738.01   145.6  738.83
  157.53   742.7  160.52  744.42  169.47  747.42  178.41  751.31   181.4  753.55
  184.38  755.23  199.29  762.87  202.28  765.09  205.26  767.75  217.19  773.91
#Mann= 3 , 0 , 0
       0      .1       0  119.37      .1       0  139.88      .1       0
Bank Sta=119.37,139.88
XS Rating Curve= 0 ,0
Exp/Cntr=0.3,0.1

Type RM Length L Ch R = 1 ,914.4   ,91.45,91.44,94.26
XS GIS Cut Line= 6
     633205.6797    4315924.2375      633093.051      4315958.78
     633081.8737    4315959.5589     633079.8481     4315959.837
      633072.252    4315962.8685     632978.1376    4315977.1543
#Sta/Elev= 30
       0  774.54    9.06  770.35   12.08  767.52    15.1  766.04   30.21   759.9
   36.25     756   54.37  748.68   57.39  746.86   63.43  745.09   69.48  743.96
   93.64  742.14  111.77  739.45  117.81  738.13  120.61  736.24  123.41  735.02
  127.51  734.54  133.78  735.08  145.38  736.32  160.73  737.44  166.87  738.64
  169.94  739.84  182.22  745.38  188.37  749.54  203.72  757.04  206.79  759.05
  209.86  761.64  222.14  767.77  225.21  769.54  231.36  773.95  234.43  775.51
#Mann= 3 , 0 , 0
       0      .1       0  123.41      .1       0  133.78      .1       0
Bank Sta=123.41,133.78
XS Rating Curve= 0 ,0
Exp/Cntr=0.3,0.1

Type RM Length L Ch R = 1 ,822.96  ,94.42,91.44,89.84
XS GIS Cut Line= 4
     633185.7025    4315848.3453     633106.0956     4315870.219
     633085.0543    4315877.9267      632989.887    4315885.4293
#Sta/Elev= 30
       0  765.04    3.06  763.14   18.35  755.55   24.46   751.5   42.81  745.15
   45.87  743.29   64.21  737.87   67.27  736.47   70.33  735.49   85.36  731.61
   88.16  730.44   90.96  728.77   93.76  728.31   96.56  728.73  102.16  730.45
  104.97  730.94  119.88  732.42  125.85  733.35   134.8  736.05  140.76  737.58
  149.71  740.52   152.7  742.71  161.65  746.37   170.6  750.55  173.58  752.62
  176.56  754.21  182.53  756.55  191.48  760.56  197.45  764.72  200.43  766.47
#Mann= 3 , 0 , 0
       0      .1       0   90.96      .1       0   96.56      .1       0
Bank Sta=90.96,96.56
XS Rating Curve= 0 ,0
Exp/Cntr=0.3,0.1