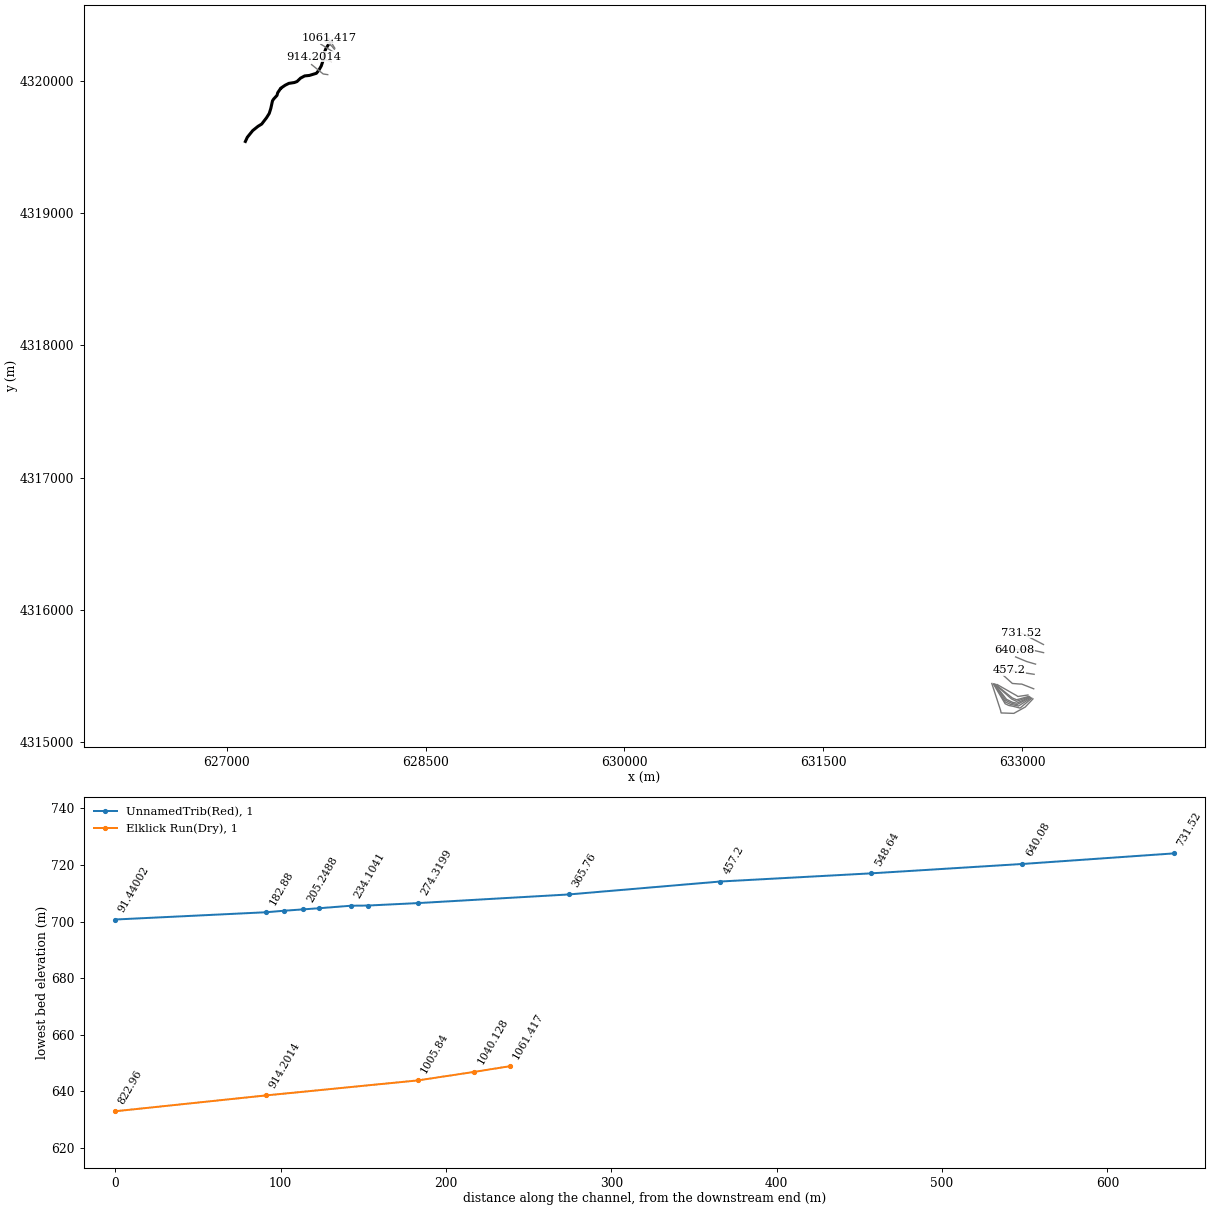
HEC-RAS study RedCreek.prj: RedCreek

--- RedCreek.g01 (geometry) --- (continued)

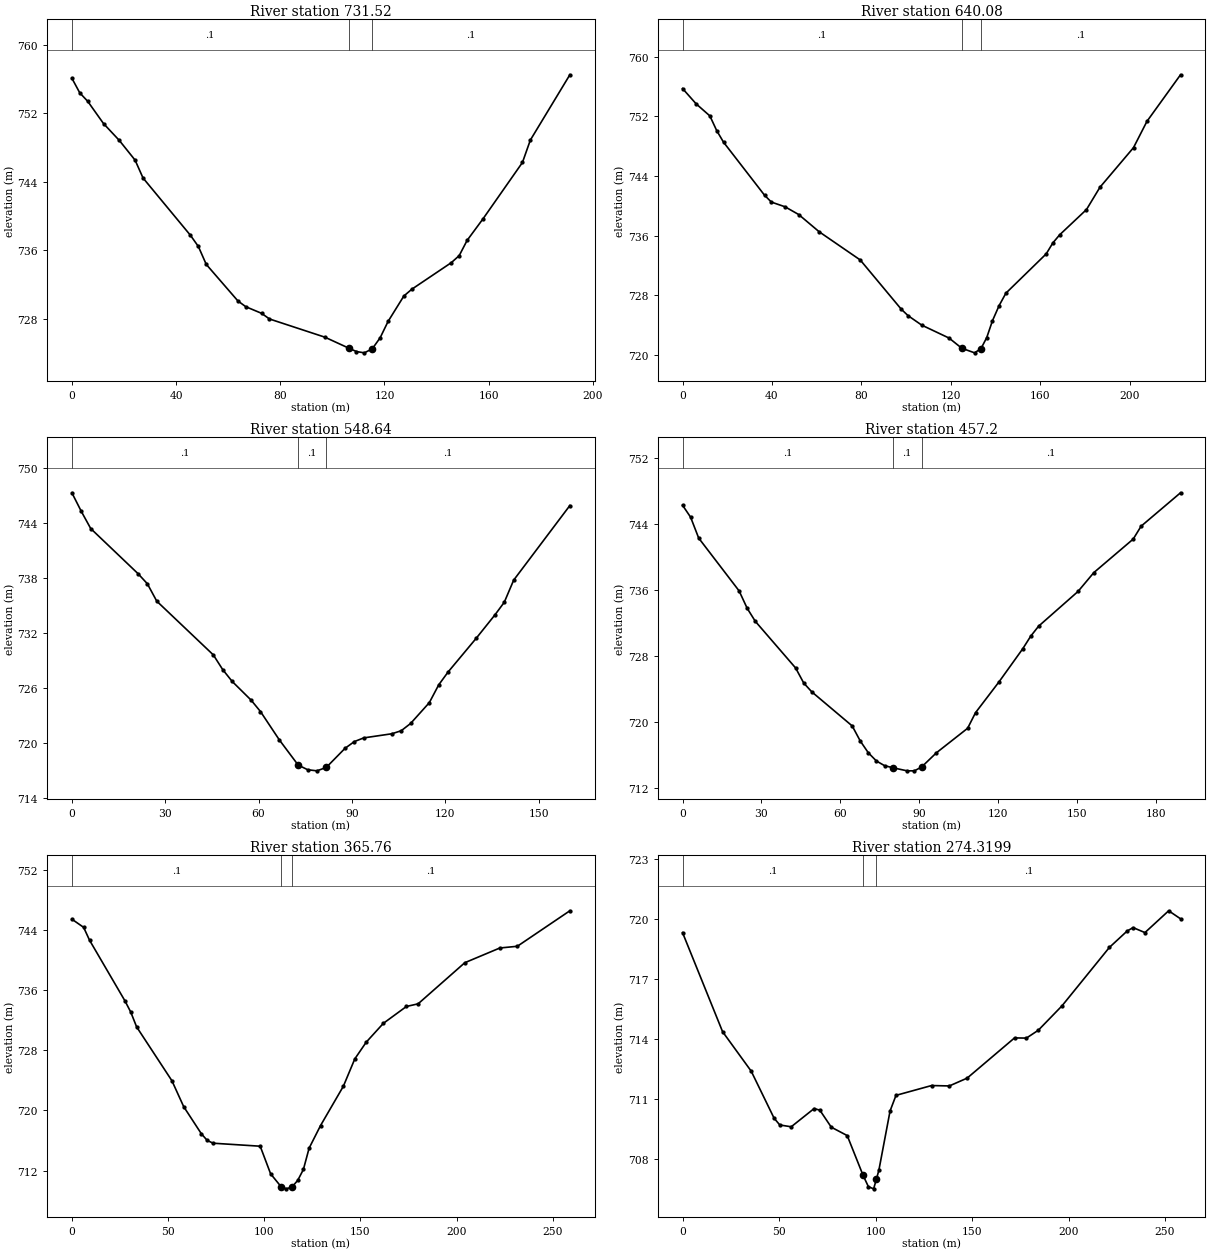
Type RM Length L Ch R = 1 ,731.52  ,82.99,91.44,96.03
XS GIS Cut Line= 2
     633159.8935    4315738.7045     632990.0527    4315826.4434
#Sta/Elev= 30
       0  756.09    3.03  754.38    6.07   753.4   12.14   750.8   18.21  748.83
   24.27  746.53   27.31  744.45   45.52  737.76   48.55  736.46   51.58  734.37
   63.72  730.11   66.76  729.43   72.82  728.66   75.86     728    97.1  725.88
   106.2  724.61  109.24   724.2  112.27  724.05  115.31  724.52  118.34  725.81
  121.37  727.71  127.44  730.68  130.48  731.47  145.65  734.57  148.68  735.39
  151.72  737.17  157.79  739.67  172.96  746.26  175.99  748.87  191.16  756.49
#Mann= 3 , 0 , 0
       0      .1       0   106.2      .1       0  115.31      .1       0
Bank Sta=106.2,115.31
XS Rating Curve= 0 ,0
Exp/Cntr=0.3,0.1

Type RM Length L Ch R = 1 ,640.08  ,94.99,91.44,88
XS GIS Cut Line= 5
     633160.5902    4315677.2925     633044.4049    4315704.0356
     633030.1361    4315703.4327     633025.0518    4315702.8115
     632940.9856    4315699.7822
#Sta/Elev= 30
       0  755.72    6.11  753.66   12.23  752.05   15.29  750.08   18.34  748.53
   36.68  741.43   39.74  740.51   45.86  739.88   51.97  738.84   61.14  736.53
   79.48  732.76   97.82  726.17  100.88   725.3     107  724.03  119.22   722.3
  124.94  720.93  130.65  720.32   133.5  720.89  136.07  722.36  138.63  724.62
  141.63  726.66  144.64  728.31  162.66  733.57  165.67  735.05  168.67  736.12
  180.69  739.51   186.7  742.49  201.72   747.8  207.73  751.32  222.75  757.56
#Mann= 3 , 0 , 0
       0      .1       0  124.94      .1       0   133.5      .1       0
Bank Sta=124.94,133.5
XS Rating Curve= 0 ,0
Exp/Cntr=0.3,0.1

Type RM Length L Ch R = 1 ,548.64  ,86.92,91.44,94.18
XS GIS Cut Line= 3
     633100.0621    4315590.5251     633033.1261    4315610.0136
     632949.8364    4315644.9953
#Sta/Elev= 30
       0  747.31    3.03  745.28    6.06  743.41   21.22  738.51   24.25   737.4
   27.28   735.5   45.47  729.64    48.5  728.03   51.53  726.75   57.59  724.72
   60.62  723.47   66.68  720.38   72.73  717.64   75.79  717.13   78.75  717.01
   81.76  717.38   87.78  719.46   90.79   720.2   93.81   720.6  102.84  721.05
  105.85  721.38  108.86  722.17  114.88  724.44   117.9  726.38  120.91  727.78
  129.94  731.45  135.96     734  138.97  735.38  141.99  737.79  160.05  745.92
#Mann= 3 , 0 , 0
       0      .1       0   72.73      .1       0   81.76      .1       0
Bank Sta=72.73,81.76
XS Rating Curve= 0 ,0
Exp/Cntr=0.3,0.1

Type RM Length L Ch R = 1 ,457.2   ,88.58,91.44,90.46
XS GIS Cut Line= 5
     633089.4187    4315513.6834     633010.4656    4315525.6485
     632996.6961    4315526.5333     632991.0048    4315527.1537
      632902.621    4315543.6777
#Sta/Elev= 30
       0  746.31    3.07  744.86    6.14  742.33    21.5  735.93   24.57  733.82
   27.64  732.25      43  726.58   46.07  724.76   49.14  723.69    64.5  719.56
   67.57  717.73   70.64   716.3   73.71  715.31   76.78  714.75   79.85   714.5
   85.37  714.12   88.13  714.12   90.89  714.59   96.51  716.31  108.37  719.28
  111.37  721.17  120.36  724.93  129.35  728.93  132.35  730.44  135.34  731.65
  150.33  735.86  156.32  738.14  171.31  742.21  174.31  743.77  189.29  747.82
#Mann= 3 , 0 , 0
       0      .1       0   79.85      .1       0   90.89      .1       0
Bank Sta=79.85,90.89
XS Rating Curve= 0 ,0
Exp/Cntr=0.3,0.1

Type RM Length L Ch R = 1 ,365.76  ,96.23,91.44,86.97
XS GIS Cut Line= 5
      633086.244    4315404.1021     632995.1054    4315439.8988
     632981.5455    4315439.8988      632925.319    4315444.4099
     632857.6417     4315505.313
#Sta/Elev= 30
       0  745.49    6.12   744.4    9.18  742.69   27.54  734.63    30.6  733.12
   33.66  731.14   52.02  723.96   58.14  720.51   67.32   716.9   70.38  716.01
   73.44  715.64   97.92  715.24  103.34  711.56  108.76  709.85  111.48  709.56
  114.45  709.81  117.41  710.68  120.38  712.14  123.35  714.98  129.29  717.99
  141.16  723.23   147.1  726.87  153.04   729.1  161.95  731.61  173.95  733.86
  180.02  734.21   204.3  739.69  222.51  741.65  231.62  741.88  258.93  746.61
#Mann= 3 , 0 , 0
       0      .1       0  108.76      .1       0  114.45      .1       0
Bank Sta=108.76,114.45
XS Rating Curve= 0 ,0
Exp/Cntr=0.3,0.1

Type RM Length L Ch R = 1 ,274.3199,29.02,30.17,30.88
XS GIS Cut Line= 5
     633042.8504    4315357.1461     632966.5965    4315345.9802
     632955.4125    4315354.0207     632943.3586    4315360.3541
     632810.0166    4315436.5212
#Sta/Elev= 30
       0   719.3   20.75  714.35   35.57  712.38   47.43  710.03   50.39  709.69
   56.32   709.6   68.17  710.51   71.14  710.43   77.07  709.58   85.33  709.16
   93.56  707.17   96.29  706.61   99.01   706.5  100.41  706.97  101.73  707.43
  107.53  710.39   110.6  711.17  129.03  711.66  138.24  711.64  147.46  712.03
  172.03  714.04  178.17  714.03  184.31  714.42   196.6  715.64  221.17  718.56
  230.38  719.38  233.45  719.55  239.59   719.3  251.88  720.39  258.02  719.99
#Mann= 3 , 0 , 0
       0      .1       0   93.56      .1       0  100.41      .1       0
Bank Sta=93.56,100.41
XS Rating Curve= 0 ,0
Exp/Cntr=0.3,0.1

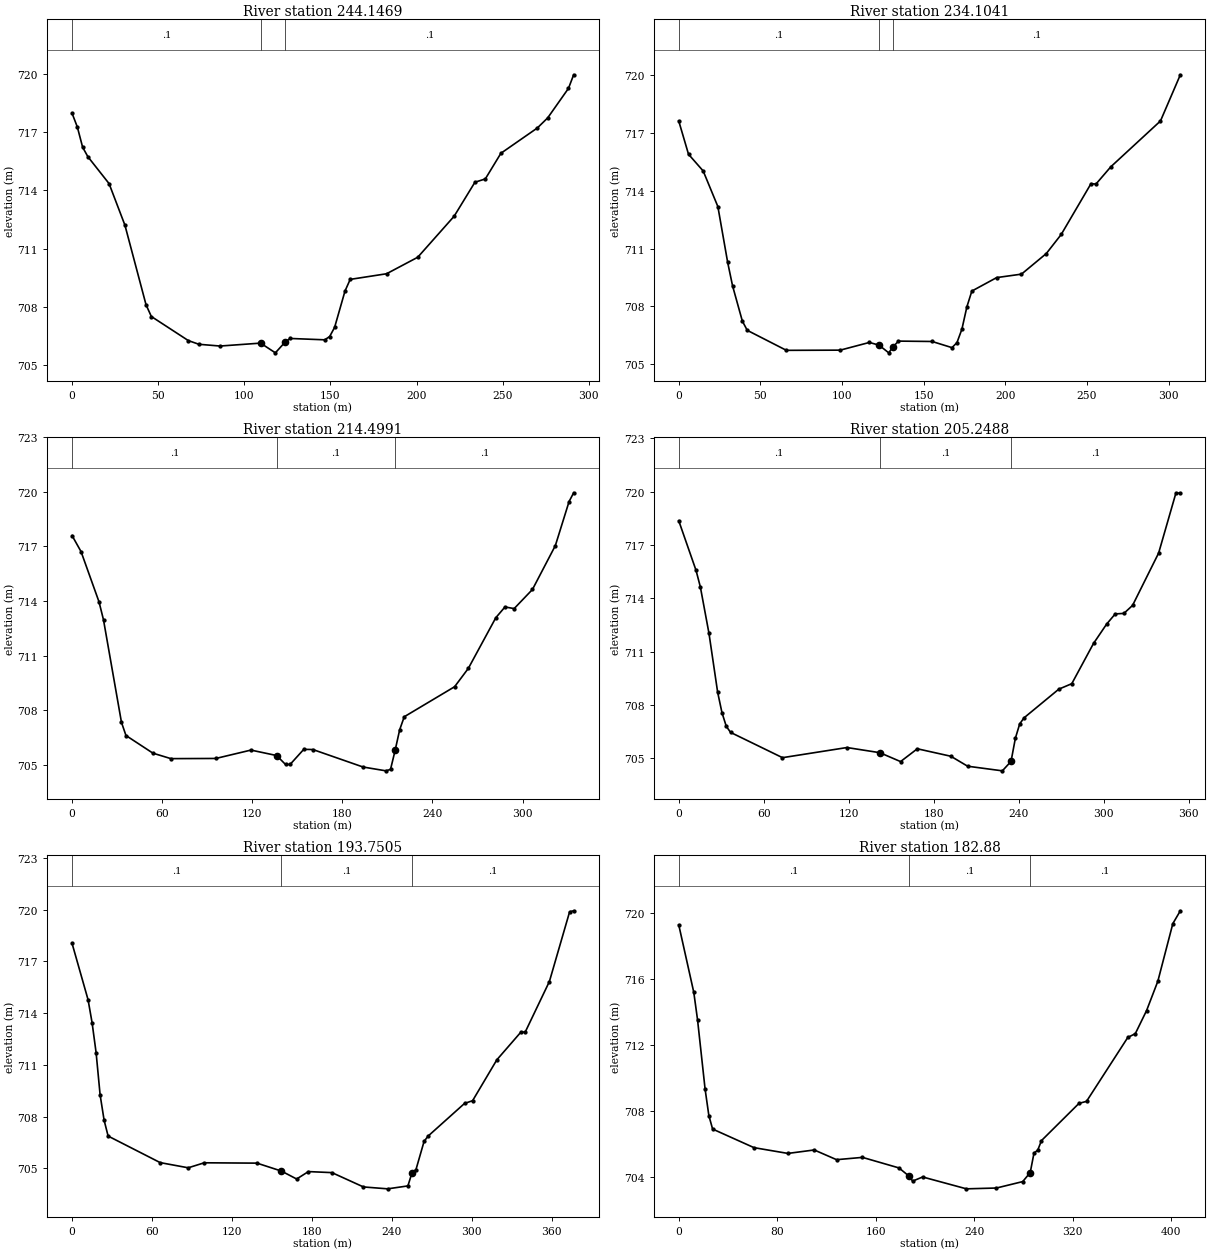
Type RM Length L Ch R = 1 ,244.1469,10.9,10.04,9.72
XS GIS Cut Line= 5
     633049.3441    4315346.6654     632957.6658    4315321.2653
     632925.9158    4315334.3623     632907.6595    4315348.2529
     632800.1061    4315435.9625
#Sta/Elev= 30
       0  717.97    3.07  717.26    6.14  716.22    9.21  715.73   21.48  714.35
   30.69  712.21   42.96  708.11   46.03  707.51   67.51  706.27   73.65  706.08
   85.93  705.99  109.44  706.14  118.03  705.64  123.75   706.2  126.62  706.38
  146.68  706.31  149.55  706.48  152.42  706.95  158.45  708.82  161.47  709.42
  182.59  709.71  200.69  710.56  221.81  712.67  233.88  714.42  239.91  714.59
  248.96  715.91  270.08  717.21  276.11  717.73  288.18  719.25   291.2  719.95
#Mann= 3 , 0 , 0
       0      .1       0  109.44      .1       0  123.75      .1       0
Bank Sta=109.44,123.75
XS Rating Curve= 0 ,0
Exp/Cntr=0.3,0.1

Type RM Length L Ch R = 1 ,234.1041,16.87,19.6,20.23
XS GIS Cut Line= 5
     633051.9927    4315343.6505     632956.0811    4315309.2546
     632918.7086    4315327.4447      632912.094    4315333.0671
     632796.6693    4315436.5856
#Sta/Elev= 30
       0  717.63    5.99   715.9   14.98  715.03   23.97  713.18   29.97  710.28
   32.97  709.06   38.96  707.23   41.96  706.75   65.93  705.71    98.9  705.72
  116.74  706.12  122.67  705.98  128.61  705.58  130.93  705.86  134.55  706.19
  155.18  706.17  167.34  705.85  170.38  706.11  173.42  706.81  176.46  707.97
   179.5  708.79   194.7  709.49   209.9  709.67   225.1  710.74  234.22  711.73
  252.46  714.37   255.5  714.35  264.62  715.25  295.02  717.63  307.18  720.03
#Mann= 3 , 0 , 0
       0      .1       0  122.67      .1       0  130.93      .1       0
Bank Sta=122.67,130.93
XS Rating Curve= 0 ,0
Exp/Cntr=0.3,0.1

Type RM Length L Ch R = 1 ,214.4991,9.21,9.25,9.45
XS GIS Cut Line= 5
     633055.6308    4315341.0047     632958.0655    4315295.3639
     632927.3076    4315301.6478     632881.0054    4315324.4682
     632793.0313    4315437.5778
#Sta/Elev= 30
       0   717.6    5.98  716.72   17.95  713.96   20.94  712.97   32.91  707.34
    35.9  706.62   53.86  705.65   65.82  705.35   95.74  705.36  119.13  705.82
  136.25  705.52  142.14  705.03  145.18  705.03  154.29  705.86  160.36  705.85
  193.78  704.89  209.02  704.68  212.07  704.76  215.12   705.8  218.17  706.94
  221.21  707.65  254.75   709.3   263.9  710.31  282.19  713.09  288.29  713.68
  294.39  713.59  306.58  714.64  321.83  717.05  330.97  719.47  334.02  719.95
#Mann= 3 , 0 , 0
       0      .1       0  136.25      .1       0  215.12      .1       0
Bank Sta=136.25,215.12
XS Rating Curve= 0 ,0
Exp/Cntr=0.3,0.1

Type RM Length L Ch R = 1 ,205.2488,8.74,11.5,11.74
XS GIS Cut Line= 5
     633060.0598    4315339.1248     632960.8408    4315285.1497
     632923.9314    4315293.0872     632875.9094     4315316.106
     632789.7874    4315439.1375
#Sta/Elev= 30
       0  718.36   12.21  715.57   15.26  714.64   21.37  712.02   27.47  708.72
   30.53  707.57   33.58   706.8   36.63  706.46   73.26  705.04  118.76  705.61
  141.99  705.32  156.62  704.82  168.45  705.54  192.12  705.12  203.96  704.56
  228.48   704.3  234.61  704.83  237.67  706.13  240.74  706.94   243.8  707.28
  268.32  708.89  277.51   709.2  292.84  711.46  302.03  712.54  308.16  713.12
  314.29  713.15  320.42   713.6  338.81  716.54  351.07  719.93  354.14   719.9
#Mann= 3 , 0 , 0
       0      .1       0  141.99      .1       0  234.61      .1       0
Bank Sta=141.99,234.61
XS Rating Curve= 0 ,0
Exp/Cntr=0.3,0.1

Type RM Length L Ch R = 1 ,193.7505,10.77,10.87,12.97
XS GIS Cut Line= 6
     633064.5853    4315334.4755     632971.3195    4315273.7535
     632926.4725    4315283.6754     632915.0954    4315284.6014
     632872.3651    4315304.4452     632785.3749    4315439.7881
#Sta/Elev= 30
       0  718.05   12.03  714.78   15.04  713.45   18.05  711.72   21.06  709.27
   24.06   707.8   27.07  706.88   66.17  705.34   87.23  705.04   99.26  705.33
  138.85  705.31  157.22  704.85  168.64  704.39  177.47  704.82  195.14  704.76
  218.79  703.93     237  703.82  252.18  703.99  255.21  704.74  258.25  704.94
  264.32  706.57  267.36  706.88  294.68  708.77  300.75  708.93  318.96   711.3
  337.18  712.92  340.21   712.9  358.42  715.84   373.6  719.88  376.64  719.94
#Mann= 3 , 0 , 0
       0      .1       0  157.22      .1       0  255.21      .1       0
Bank Sta=157.22,255.21
XS Rating Curve= 0 ,0
Exp/Cntr=0.3,0.1

Type RM Length L Ch R = 1 ,182.88  ,116.67,91.44,69.24
XS GIS Cut Line= 6
     633071.9547    4315333.3335     632983.1981    4315258.3136
     632927.8879    4315272.5537      632898.172    4315278.0504
     632871.0024    4315291.0746     632782.2353      4315440.49
#Sta/Elev= 30
       0  719.31   12.23  715.21   15.29  713.54   21.41  709.34   24.47  707.73
   27.52  706.91   61.17  705.78   88.69  705.43   110.1  705.64  128.24  705.05
  149.28  705.19  178.93  704.55  187.32  704.04  190.04  703.75  198.19     704
  233.76  703.28  258.15  703.33  279.49  703.72  285.59  704.27  288.64  705.45
  291.69  705.63  294.74  706.21  325.23  708.47  331.32  708.59  364.86  712.47
  370.96   712.7  380.11   714.1  389.26  715.88  401.45  719.38  407.55  720.16
#Mann= 3 , 0 , 0
       0      .1       0  187.32      .1       0  285.59      .1       0
Bank Sta=187.32,285.59
XS Rating Curve= 0 ,0
Exp/Cntr=0.3,0.1

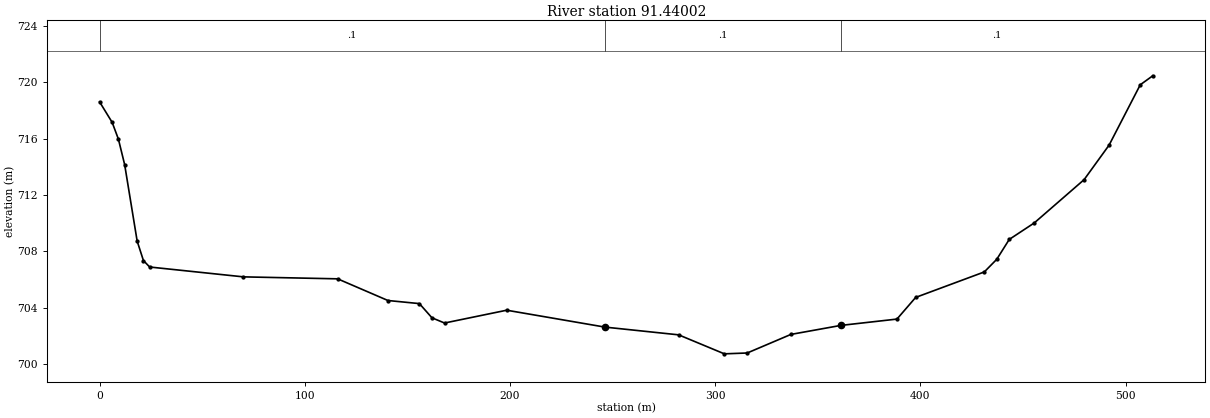
Type RM Length L Ch R = 1 ,91.44002,53.51,91.44,66.99
XS GIS Cut Line= 6
     633080.6407    4315327.8685     633021.9031    4315265.9559
      632936.178    4315218.3308     632840.4647    4315221.5014
     632836.4602    4315240.8379      632770.329    4315444.4587
#Sta/Elev= 30
       0  718.61     6.1  717.16    9.14  715.97   12.19  714.16   18.29  708.72
   21.34  707.34   24.38  706.88    70.1  706.18  115.99  706.04   140.5   704.5
  155.83  704.28  161.96  703.27  168.09   702.9  198.37  703.81  246.25  702.61
  282.17  702.06  304.45  700.71  315.59  700.77  336.88  702.09   361.2  702.73
  388.56  703.18  397.69  704.72  431.13  706.53  437.21  707.43  443.29  708.84
  455.46  710.01  479.78  713.09  491.94  715.54  507.14  719.83  513.23  720.47
#Mann= 3 , 0 , 0
       0      .1       0  246.25      .1       0   361.2      .1       0
Bank Sta=246.25,361.2
XS Rating Curve= 0 ,0
Exp/Cntr=0.3,0.1

River Reach=Elklick Run(Dry),1
Reach XY= 30
     627790.5643    4320292.6597     627774.3585    4320283.0685
     627747.2387    4320239.7429     627740.5593    4320220.8685
      627733.348    4320170.2896     627713.5043     4320111.089
     627694.9834     4320078.016     627676.7932    4320055.5264
     627623.8765    4320039.3206     627588.4884    4320035.6826
      627557.186    4320018.8587     627530.7425    4319993.3648
     627510.7669    4319985.7424     627469.4256    4319979.4585
     627441.6443    4319965.5679     627411.4103    4319945.0247
627410.1245641374319940.97138682     627407.1187    4319941.0721
     627385.0895    4319908.6823     627379.7979    4319888.5078
        627354.8    4319861.3564     627345.7327    4319847.4973
      627333.165    4319790.2811     627321.2587    4319752.2471
     627300.7534    4319719.5049     627264.3731    4319671.8798
     627236.9226    4319655.0126     627196.4271    4319622.3503
     627155.7376    4319571.8508     627141.3213    4319540.3754

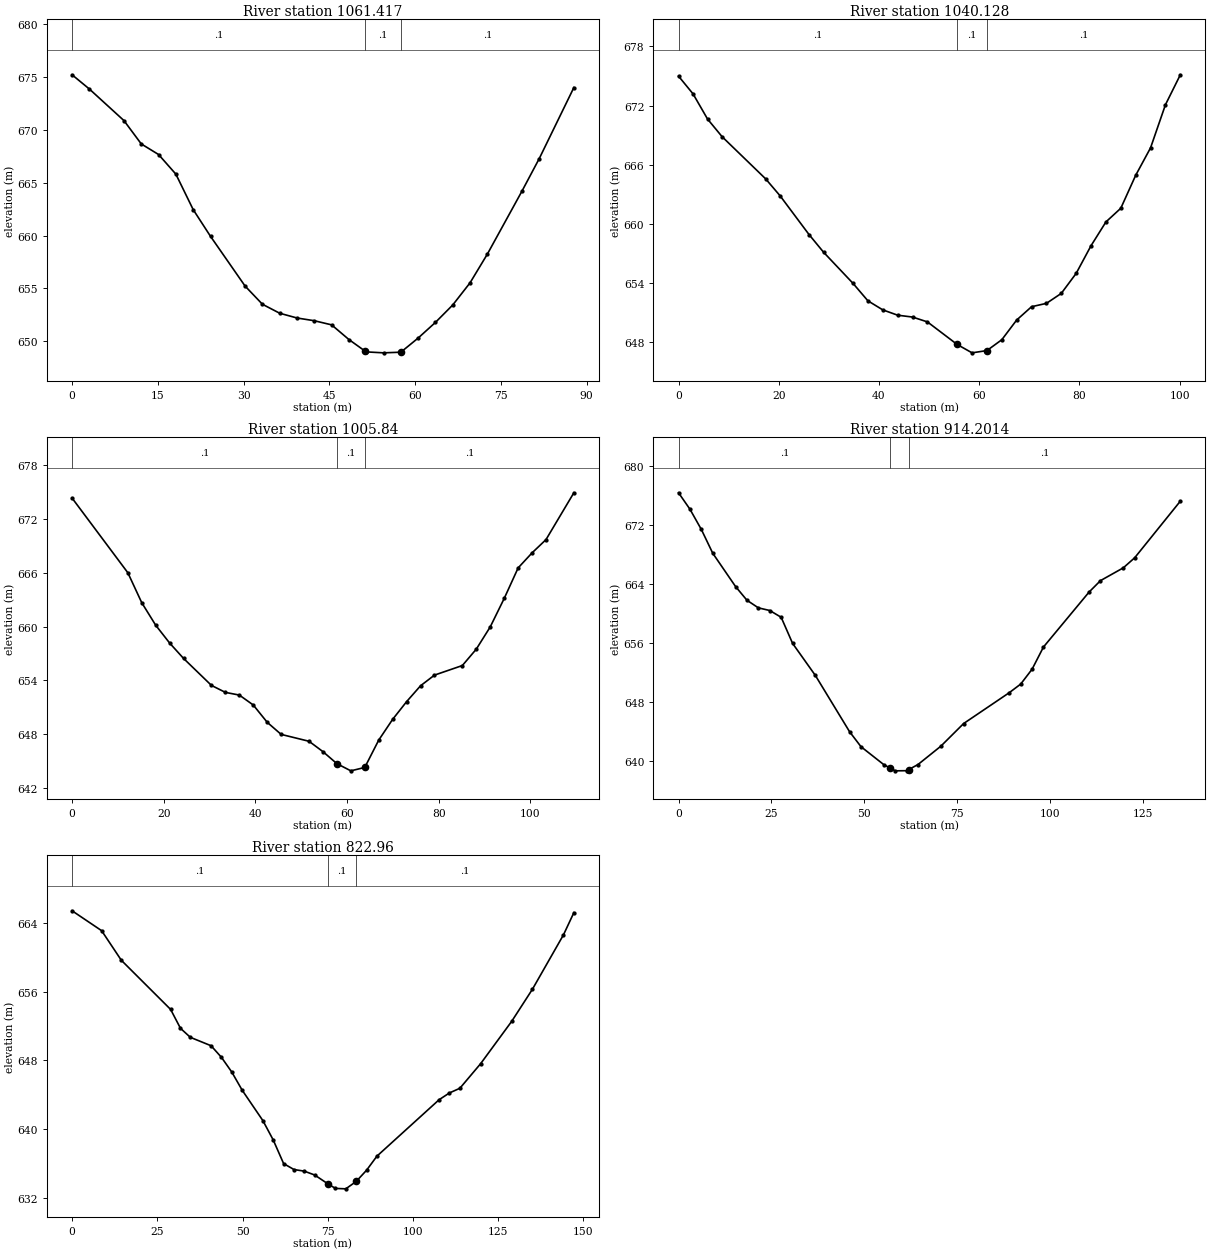
Type RM Length L Ch R = 1 ,1061.417,19.63,21.29,22.94
XS GIS Cut Line= 2
     627815.6968    4320245.0369     627769.5155    4320319.6862
#Sta/Elev= 27
       0  675.23    3.03  673.88    9.08  670.89   12.11  668.68   15.13  667.68
   18.16  665.82   21.19  662.46   24.22  659.93   30.27  655.22    33.3   653.5
   36.32  652.65   39.35   652.2   42.38  651.94    45.4  651.55   48.43  650.16
   51.29  649.05   51.46  648.99   54.48   648.9   57.51  648.96   60.54   650.3
   63.56  651.78   66.59  653.43   69.62  655.53   72.65  658.25    78.7  664.21
   81.73   667.3   87.78  674.02
#Mann= 3 , 0 , 0
       0      .1       0   51.29      .1       0   57.51      .1       0
Bank Sta=51.29,57.51
XS Rating Curve= 0 ,0
Exp/Cntr=0.3,0.1

Type RM Length L Ch R = 1 ,1040.128,33.85,34.29,34.73
XS GIS Cut Line= 3
     627812.3413    4320237.5641     627791.7763    4320261.8883
     627737.7334    4320303.6488
#Sta/Elev= 30
       0  674.98     2.9  673.18    5.79  670.63    8.69  668.84   17.37  664.57
   20.27  662.84   26.06   658.9   28.96  657.11   34.82  653.96   37.79  652.19
   40.76  651.27   43.73  650.73    46.7  650.54   49.67  650.05   55.61  647.76
   58.58  646.91   61.55  647.14   64.52  648.24   67.49  650.24   70.46  651.59
   73.43  651.93   76.39  652.94   79.36  654.97   82.33  657.78    85.3  660.19
   88.27  661.58   91.24  664.92   94.21  667.71   97.18  672.08  100.15  675.12
#Mann= 3 , 0 , 0
       0      .1       0   55.61      .1       0   61.55      .1       0
Bank Sta=55.61,61.55
XS Rating Curve= 0 ,0
Exp/Cntr=0.3,0.1

Type RM Length L Ch R = 1 ,1005.84 ,90.33,91.64,92.95
XS GIS Cut Line= 2
     627803.1233    4320217.2935     627710.3754    4320275.4881
#Sta/Elev= 30
       0  674.35   12.17  666.01   15.21  662.66   18.25  660.15   21.29  658.16
   24.33  656.44   30.41  653.43   33.46  652.65    36.5  652.35   39.54  651.24
   42.58  649.31   45.62  647.96   51.71  647.19   54.75  646.03   57.79  644.69
   60.83  643.89   63.87  644.27   66.91  647.32   69.95  649.64      73  651.62
   76.04  653.39   79.08  654.58   85.16  655.65    88.2  657.48   91.24  659.96
   94.29  663.14   97.33  666.55  100.37  668.23  103.41  669.71  109.49  674.94
#Mann= 3 , 0 , 0
       0      .1       0   57.79      .1       0   63.87      .1       0
Bank Sta=57.79,63.87
XS Rating Curve= 0 ,0
Exp/Cntr=0.3,0.1

Type RM Length L Ch R = 1 ,914.2014,93.09,91.24,89.39
XS GIS Cut Line= 2
     627788.0319    4320144.9373     627657.7437    4320181.0126
#Sta/Elev= 30
       0  676.39    3.07  674.16    6.15   671.4    9.22  668.17   15.36  663.65
   18.44  661.78   21.51  660.75   24.58  660.39   27.65  659.47   30.73  655.92
   36.87  651.56   46.09  643.91   49.16  641.88   55.31  639.44      57  638.98
   58.38   638.6   61.45  638.62      62  638.77   64.52  639.46   70.67  641.95
   76.81  645.03    89.1  649.22   92.18  650.39   95.25  652.41   98.32  655.43
  110.61   662.9  113.68  664.45  119.83  666.19   122.9  667.56  135.19  675.25
#Mann= 3 , 0 , 0
       0      .1       0      57      .1       0      62      .1       0
Bank Sta=57,62
XS Rating Curve= 0 ,0
Exp/Cntr=0.3,0.1

Type RM Length L Ch R = 1 ,822.96  ,95.98,91.37,87.74
XS GIS Cut Line= 3
     627762.2543    4320045.4134     627727.9395    4320050.4926
     627640.4744    4320121.2367
#Sta/Elev= 30
       0  665.42    8.67   663.1   14.45  659.65   28.91  653.92    31.8  651.72
   34.69  650.67   40.77  649.69   43.81  648.34   46.85  646.62   49.89  644.51
   55.97  640.96   59.01   638.7   62.05  635.95   65.09  635.26   68.13  635.07
   71.17  634.62   75.12  633.57   77.25  633.06   80.29  633.01   83.33  633.87
   86.38  635.18   89.42  636.82  107.66   643.4   110.7  644.19  113.74  644.73
  119.82  647.59  128.94  652.53  135.02  656.27  144.14  662.62  147.18   665.2
#Mann= 3 , 0 , 0
       0      .1       0   75.12      .1       0   83.33      .1       0
Bank Sta=75.12,83.33
XS Rating Curve= 0 ,0
Exp/Cntr=0.3,0.1