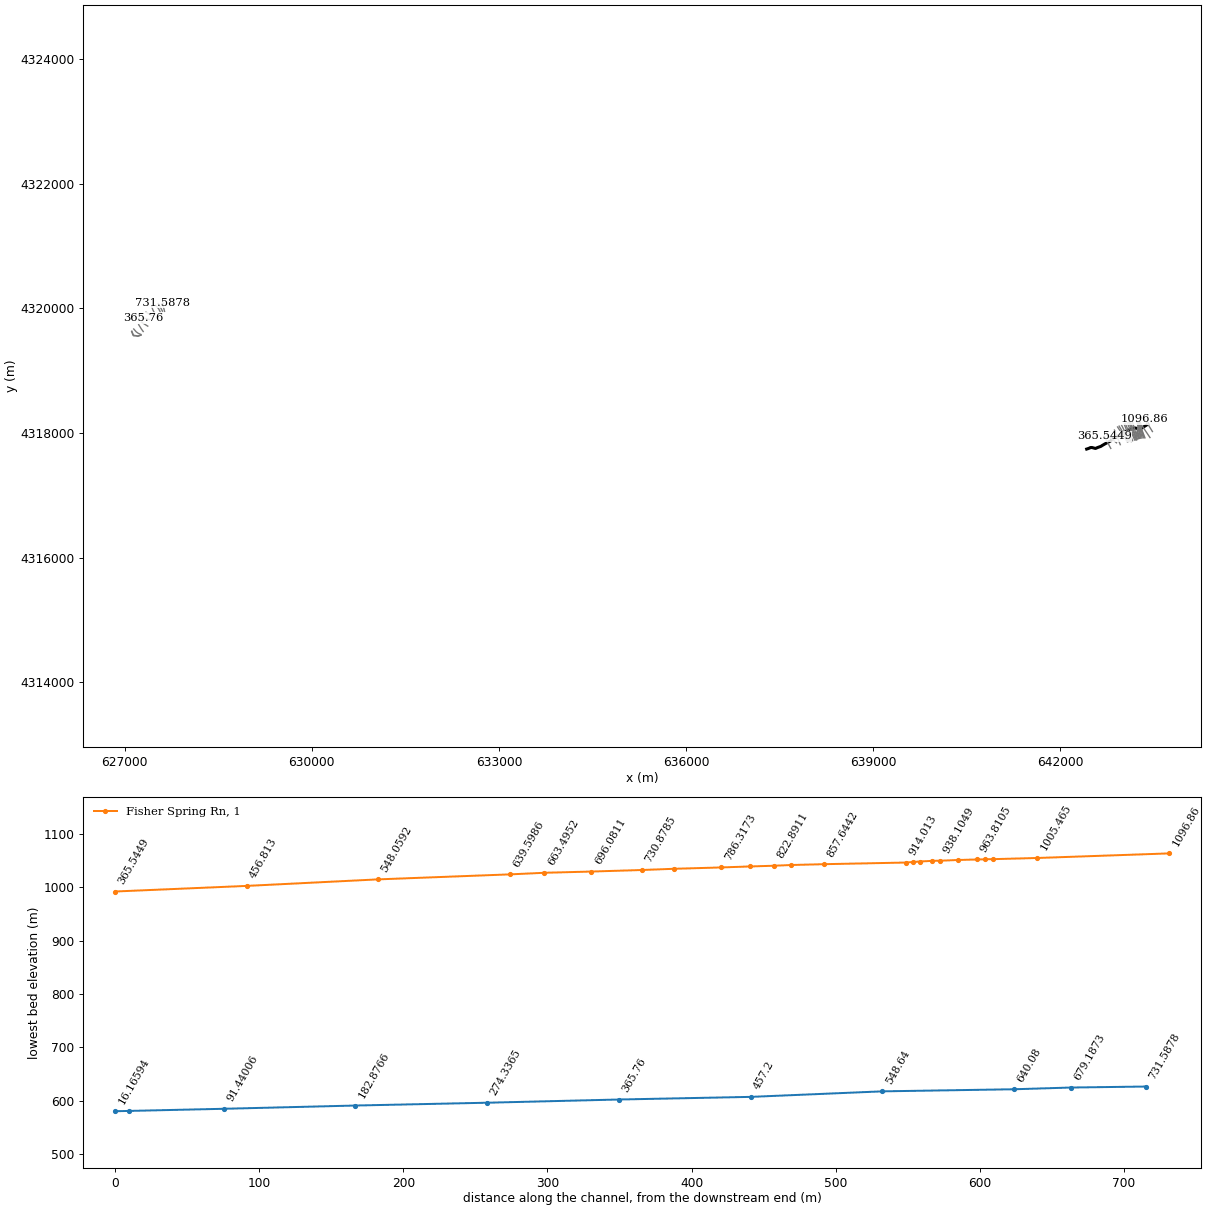
HEC-RAS study RedCreek.prj: RedCreek

--- RedCreek.g01 (geometry) --- (continued)

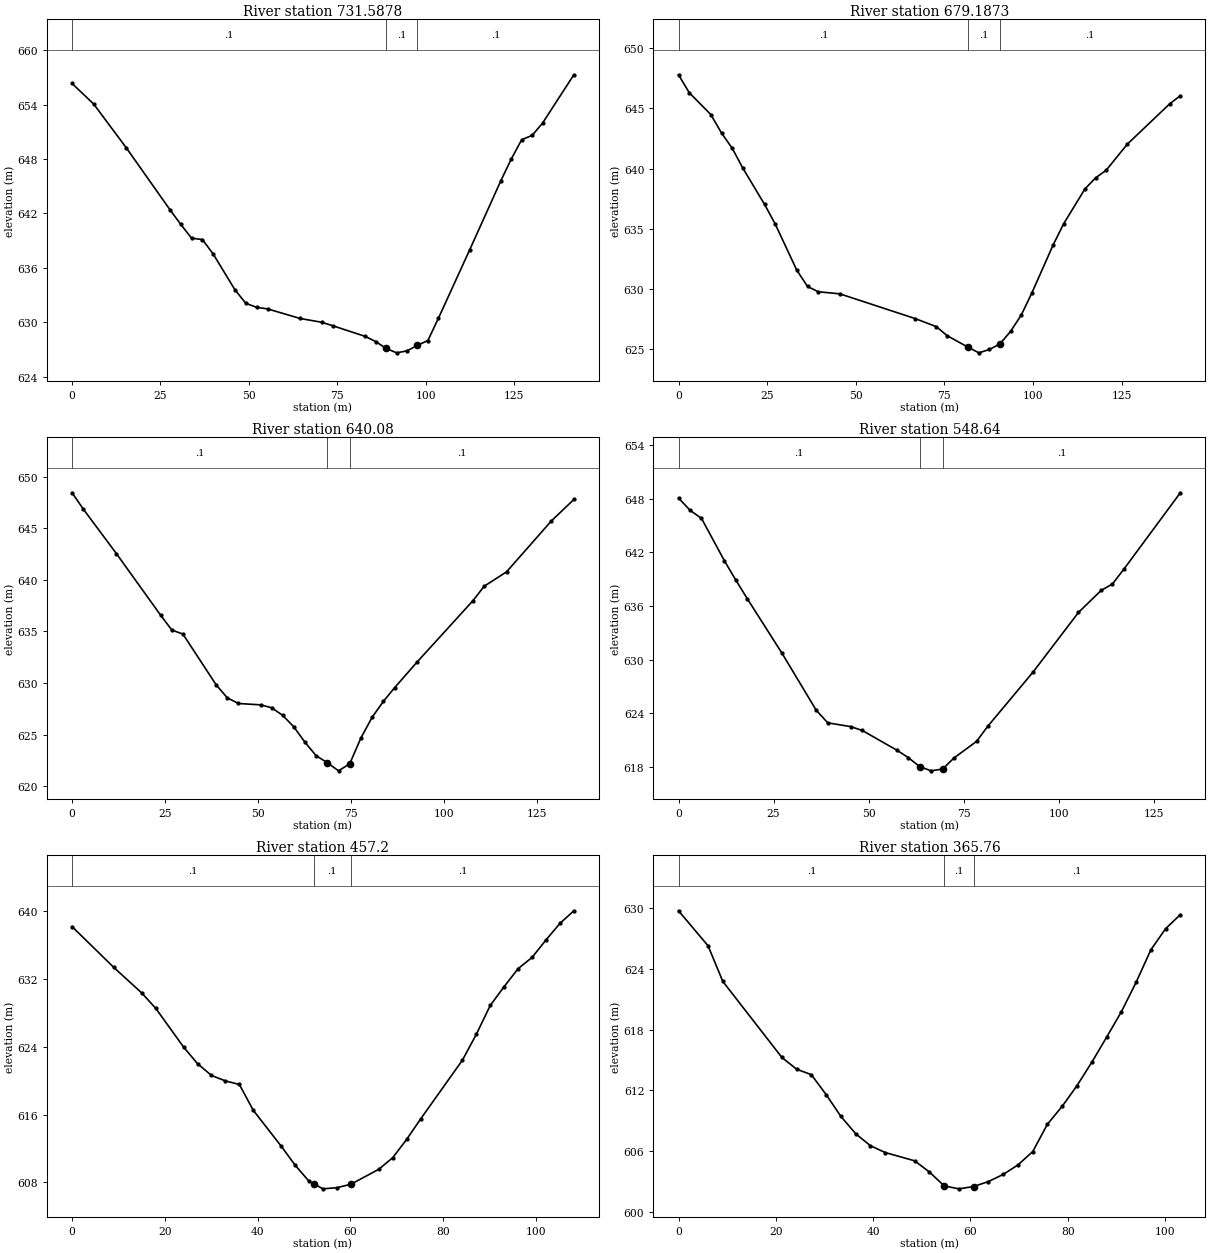
Type RM Length L Ch R = 1 ,731.5878,46.35,52.4,54.51
XS GIS Cut Line= 3
     627637.7551    4319950.7871     627616.9429    4320031.0395
     627611.4415    4320089.7312
#Sta/Elev= 30
       0  656.34    6.14  654.06   15.35  649.23   27.64  642.43   30.71   640.8
   33.78  639.27   36.85  639.12   39.92  637.51   46.06  633.57   49.13  632.08
    52.2  631.64   55.27  631.47   64.48  630.41   70.62  629.99    73.7  629.61
   82.91  628.43   85.85  627.86    88.8  627.11   91.75  626.62    94.7  626.84
   97.64  627.45  100.59  627.98  103.54  630.41  112.38  637.96  121.22  645.61
  124.17  648.01  127.12  650.14  130.07  650.61  133.01  651.97  141.86   657.3
#Mann= 3 , 0 , 0
       0      .1       0    88.8      .1       0   97.64      .1       0
Bank Sta=88.8,97.64
XS Rating Curve= 0 ,0
Exp/Cntr=0.3,0.1

Type RM Length L Ch R = 1 ,679.1873,37.17,39.11,40.04
XS GIS Cut Line= 3
     627604.1216    4319951.7738     627571.5778    4320016.8614
     627535.0652    4320075.2021
#Sta/Elev= 30
       0  647.79    3.03   646.3     9.1  644.49   12.13  642.96   15.16  641.68
   18.19  640.02   24.26  637.04   27.29   635.4   33.35  631.58   36.39  630.22
   39.42  629.78   45.48  629.61   66.71  627.56   72.77  626.88   75.76  626.14
   81.75  625.17   84.74  624.71   87.73  624.99   90.72  625.46   93.72   626.5
   96.71  627.85    99.7  629.68  105.69  633.66  108.68  635.43  114.66  638.31
  117.66  639.23  120.65  639.86  126.63  642.03   138.6  645.38  141.59  646.05
#Mann= 3 , 0 , 0
       0      .1       0   81.75      .1       0   90.72      .1       0
Bank Sta=81.75,90.72
XS Rating Curve= 0 ,0
Exp/Cntr=0.3,0.1

Type RM Length L Ch R = 1 ,640.08  ,92.71,91.44,89.78
XS GIS Cut Line= 3
     627569.6028    4319938.3482     627541.8756    4319994.4519
     627491.6975    4320046.4991
#Sta/Elev= 28
       0  648.43    2.98  646.87   11.92  642.54   23.84  636.56   26.82  635.14
    29.8  634.75   38.74  629.83   41.72  628.58    44.7  628.03   50.66   627.9
   53.64  627.62   56.62  626.88    59.6  625.77   62.58  624.29   65.59  622.98
   68.61   622.3   71.62  621.51   74.63  622.19   77.64  624.69   80.66   626.7
   83.67  628.23   86.68  629.55    92.7  632.03  107.77  637.99  110.78  639.38
   116.8  640.78  128.85  645.71  134.88  647.78
#Mann= 3 , 0 , 0
       0      .1       0   68.61      .1       0   74.63      .1       0
Bank Sta=68.61,74.63
XS Rating Curve= 0 ,0
Exp/Cntr=0.3,0.1

Type RM Length L Ch R = 1 ,548.64  ,85.4,91.44,96.52
XS GIS Cut Line= 3
     627481.8206    4319911.1232     627450.7459    4319973.2728
     627428.8908    4320031.8865
#Sta/Elev= 25
       0  648.06    3.02   646.7    6.04  645.79   12.08  641.05   15.11  638.87
   18.13  636.79   27.19  630.75   36.25  624.35   39.27  622.95   45.32  622.53
   48.34   622.1    57.4  619.91   60.42  619.08   63.44  618.07   66.46  617.59
   69.49  617.79   72.46  619.02   78.42  620.88    81.4  622.58   93.32  628.64
  105.23  635.28  111.19  637.74  114.17  638.46  117.15   640.1  132.04  648.65
#Mann= 3 , 0 , 0
       0      .1       0   63.44      .1       0   69.49      .1       0
Bank Sta=63.44,69.49
XS Rating Curve= 0 ,0
Exp/Cntr=0.3,0.1

Type RM Length L Ch R = 1 ,457.2   ,89.75,91.44,92.7
XS GIS Cut Line= 2
     627433.3271    4319883.0389     627339.6302    4319937.0958
#Sta/Elev= 30
       0  638.21    9.01  633.38   15.02  630.37   18.03  628.56   24.04  623.98
   27.04  622.02   30.05  620.63   33.05  619.98   36.06  619.56   39.06  616.51
   45.07  612.28   48.08  610.03   51.08  608.12    52.1  607.82   54.09  607.23
   57.09  607.37    60.1  607.77   66.11  609.54   69.11   610.9   72.11  613.06
   75.12  615.47   84.13  622.42   87.14  625.48   90.14  628.89   93.15  631.13
   96.15  633.24   99.16  634.57  102.16  636.63  105.17  638.59  108.17  640.08
#Mann= 3 , 0 , 0
       0      .1       0    52.1      .1       0    60.1      .1       0
Bank Sta=52.1,60.1
XS Rating Curve= 0 ,0
Exp/Cntr=0.3,0.1

Type RM Length L Ch R = 1 ,365.76  ,93.85,91.42,89.98
XS GIS Cut Line= 2
     627398.6403    4319819.0153     627298.3951    4319843.3067
#Sta/Elev= 30
       0   629.7    6.07  626.25     9.1  622.74   21.24  615.25   24.27  614.09
    27.3  613.55   30.34  611.59   33.37  609.44    36.4  607.74   39.44  606.55
   42.47  605.88   48.54  605.06   51.57  603.96   54.61  602.59   57.64   602.3
   60.67  602.53   63.71  603.02   66.74  603.72   69.78  604.66   72.81  605.97
   75.84  608.68   78.88  610.44   81.91  612.47   84.94  614.76   87.98  617.23
   91.01  619.73   94.05  622.64   97.08  625.84  100.11  627.93  103.15  629.32
#Mann= 3 , 0 , 0
       0      .1       0   54.61      .1       0   60.67      .1       0
Bank Sta=54.61,60.67
XS Rating Curve= 0 ,0
Exp/Cntr=0.3,0.1

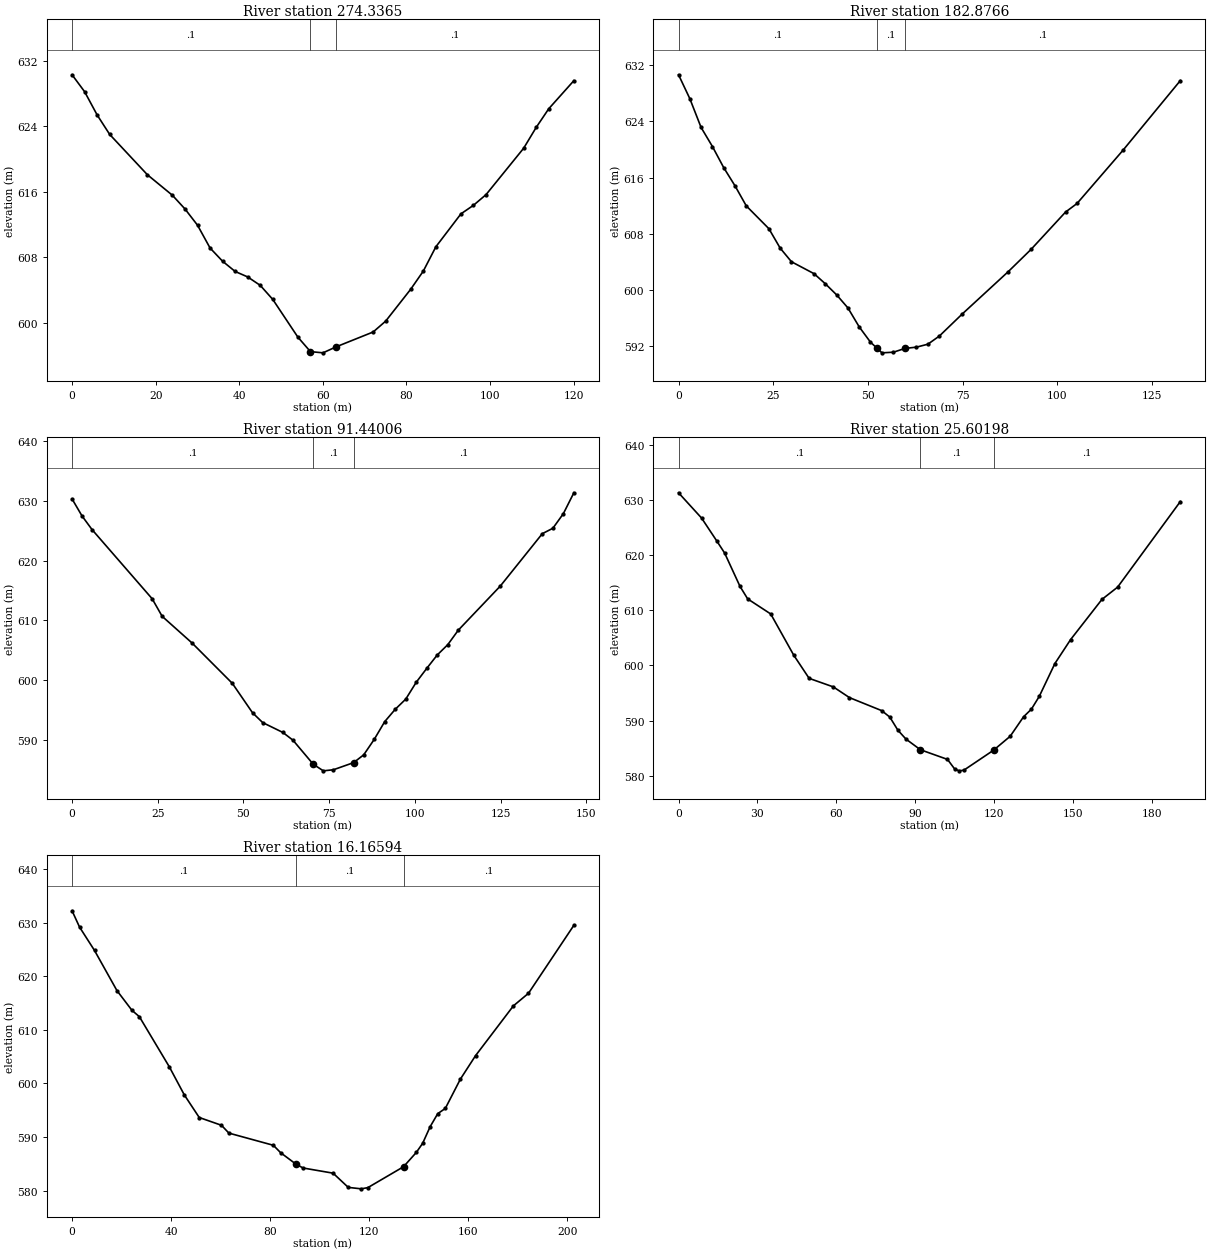
Type RM Length L Ch R = 1 ,274.3365,94.77,91.46,89.36
XS GIS Cut Line= 2
     627368.3815    4319713.2151     627266.5167    4319776.7152
#Sta/Elev= 30
       0  630.32       3  628.25       6   625.4       9  623.02   18.01  618.09
   24.01  615.57   27.01   613.9   30.01  611.91   33.01  609.12   36.01   607.5
   39.01  606.25   42.01  605.58   45.01  604.55   48.01  602.83   54.02  598.21
   57.02  596.44   60.02  596.29   63.15  597.02   72.02  598.84   75.02  600.17
   81.02  604.08   84.03   606.3   87.03  609.27   93.03   613.3   96.03  614.35
   99.03  615.65  108.03  621.33  111.03  623.88  114.03  626.16  120.04   629.6
#Mann= 3 , 0 , 0
       0      .1       0   57.02      .1       0   63.15      .1       0
Bank Sta=57.02,63.15
XS Rating Curve= 0 ,0
Exp/Cntr=0.3,0.1

Type RM Length L Ch R = 1 ,182.8766,88.26,91.44,94.99
XS GIS Cut Line= 3
       627295.44    4319626.7363     627265.6373    4319667.7448
     627222.7501    4319737.4135
#Sta/Elev= 30
       0  630.64    2.98  627.24    5.96  623.13    8.95  620.42   11.93  617.41
   14.91  614.82   17.89  611.96   23.86  608.71   26.84  605.94   29.82     604
   35.78   602.3   38.77  600.86   41.75  599.28   44.73  597.42   47.71  594.72
   50.69  592.54   52.38   591.7   53.72  591.02   56.75  591.11   59.78  591.65
   62.81  591.83   65.84  592.25   68.87  593.41   74.93  596.56   87.05  602.58
   93.11  605.77   102.2  611.08  105.23   612.3  117.36  619.88  132.51  629.81
#Mann= 3 , 0 , 0
       0      .1       0   52.38      .1       0   59.78      .1       0
Bank Sta=52.38,59.78
XS Rating Curve= 0 ,0
Exp/Cntr=0.3,0.1

Type RM Length L Ch R = 1 ,91.44006,57.38,65.84,67.65
XS GIS Cut Line= 4
     627257.8075    4319579.9861     627217.5869    4319597.3657
     627183.8829    4319621.1973     627143.5327    4319667.3534
#Sta/Elev= 30
       0  630.27    2.92  627.42    5.84  625.15   23.37  613.62   26.29  610.69
   35.05  606.22   46.76  599.51   52.66   594.6   55.61  592.97   61.51  591.32
   64.45  590.03   70.35  586.03    73.3  584.92   76.25   585.1   82.14  586.29
   85.09  587.59   88.16  590.17   91.22  593.13   94.29  595.19   97.35  596.88
  100.42   599.7  103.49  602.02  106.55  604.25  109.62  605.97  112.68  608.38
  124.94  615.74   137.2  624.48  140.27  625.38  143.33  627.81   146.4   631.3
#Mann= 3 , 0 , 0
       0      .1       0   70.35      .1       0   82.14      .1       0
Bank Sta=70.35,82.14
XS Rating Curve= 0 ,0
Exp/Cntr=0.3,0.1

Type RM Length L Ch R = 1 ,25.60198,4.05,9.44,5.97
XS GIS Cut Line= 6
     627257.3831    4319570.9937     627210.5517    4319554.5895
     627166.8954    4319562.7916      627153.137    4319563.0562
     627136.4683    4319573.3749     627113.6093    4319631.5799
#Sta/Elev= 30
       0  631.27    8.76  626.69   14.59   622.5   17.51  620.36   23.35  614.32
   26.27  612.05   35.03  609.32   43.78  601.85   49.62  597.66   58.82  596.11
   64.95  594.17   77.21  591.81   80.28  590.64   83.34  588.27   86.41  586.66
    91.9  584.73  102.19  582.98  105.03  581.17  106.72  580.91  108.41  581.03
  119.67  584.64  126.01  587.17  131.09   590.7  134.07  592.08  137.05  594.39
     143  600.35  148.96  604.68  160.87  611.96  166.82  614.18  190.65  629.68
#Mann= 3 , 0 , 0
       0      .1       0    91.9      .1       0  119.67      .1       0
Bank Sta=91.9,119.67
XS Rating Curve= 0 ,0
Exp/Cntr=0.3,0.1

Type RM Length L Ch R = 1 ,16.16594,2.67,16.17,2.45
XS GIS Cut Line= 6
     627259.4998    4319568.3479     627211.0809    4319551.1499
     627164.2496    4319559.6166     627141.4954    4319557.4999
      627130.912    4319569.6708     627109.6405    4319626.9497
#Sta/Elev= 30
       0  632.19    3.02  629.15    9.07  624.79   18.13  617.31   24.18  613.64
    27.2  612.44   39.29   603.1   45.34  597.87   51.38  593.65   60.36   592.2
   63.36  590.74   81.32  588.47   84.31  587.07    90.3  585.01   93.29  584.24
  105.46  583.27  111.59  580.62  116.88  580.35  119.52  580.58  133.92  584.47
  139.07  587.13  141.64  588.83  144.69  591.95  147.75  594.37   150.8  595.34
  156.91  600.82  163.02  605.18   178.3  614.46  184.41  616.81  202.74  629.48
#Mann= 3 , 0 , 0
       0      .1       0    90.3      .1       0  133.92      .1       0
Bank Sta=90.3,133.92
XS Rating Curve= 0 ,0
Exp/Cntr=0.3,0.1

River Reach=Fisher Spring Rn,1
Reach XY= 30
      643409.528     4318141.789     643331.7403    4318093.1056
     643310.6803    4318078.9654     643299.7412    4318076.4722
     643283.3036    4318074.9596     643253.4235    4318067.7056
     643228.5526    4318073.5264     643198.3901    4318080.4056
     643175.1067    4318073.5264     643151.8024    4318064.4657
     643135.9858    4318062.4614      643126.234    4318059.4645
     643071.3898    4318032.7805     643031.7022    4318016.3763
     642992.5438    4317992.0346     642947.6048     4317962.465
     642927.6759    4317949.9583     642864.4852    4317924.6715
      642843.054     4317913.559     642808.4204    4317871.9646
     642723.9912    4317827.8338     642673.1911     4317798.465
     642654.1411     4317785.765     642596.4618    4317764.5983
     642566.2992    4317751.3691     642509.9429     4317766.715
     642486.1303    4317765.9212      642471.049    4317758.2483
     642451.7344    4317750.3108     642425.7667    4317741.9269

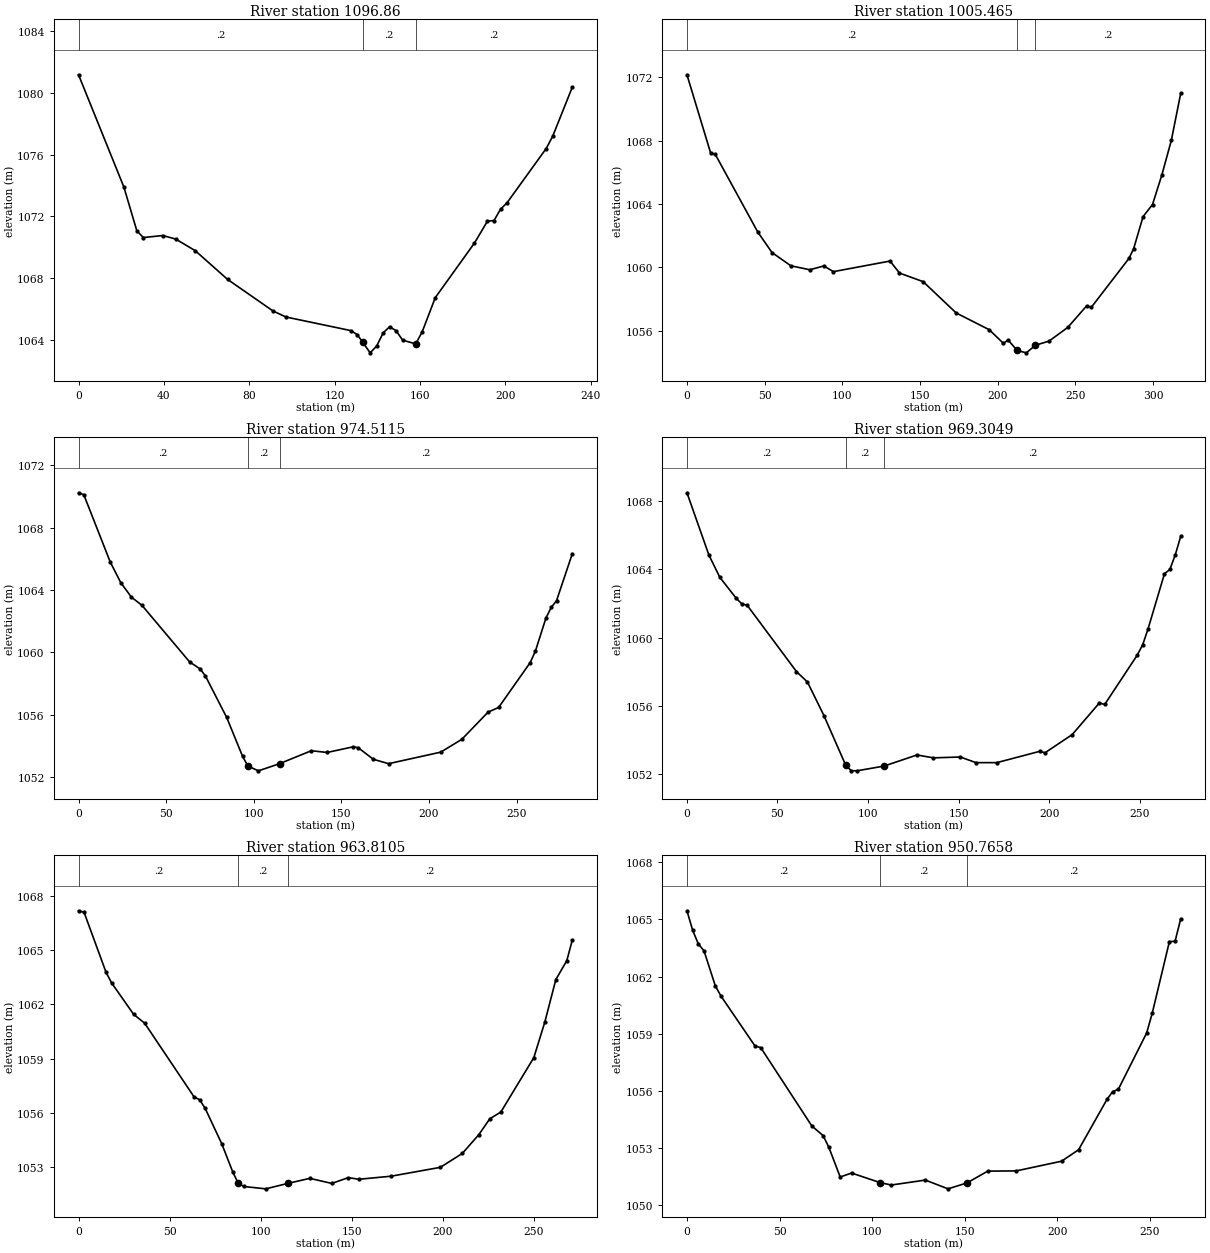
Type RM Length L Ch R = 1 ,1096.86 ,91.1,91.4,92.38
XS GIS Cut Line= 3
     643479.9948    4318022.9409     643401.4376     4318149.328
     643355.1112    4318217.6747
#Sta/Elev= 30
       0 1081.16   21.26 1073.89   27.33 1071.06   30.37 1070.63   39.48 1070.76
   45.55 1070.53   54.67 1069.78   69.85 1067.92   91.11 1065.88   97.18 1065.49
  127.55 1064.61  130.59 1064.35  133.13 1063.86  136.66 1063.17   139.7 1063.61
  142.74 1064.46  145.77 1064.86  148.81  1064.6  151.87 1063.99  157.99 1063.75
  161.04 1064.53  167.16 1066.74  185.51 1070.27  191.62 1071.69  194.68 1071.73
  197.74 1072.46   200.8 1072.88  219.15 1076.39  222.21 1077.19  231.38 1080.36
#Mann= 3 , 0 , 0
       0      .2       0  133.13      .2       0  157.99      .2       0
Bank Sta=133.13,157.99
XS Rating Curve= 0 ,0
Exp/Cntr=0.3,0.1

Type RM Length L Ch R = 1 ,1005.465,33.69,30.95,27.97
XS GIS Cut Line= 4
     643440.8364    4317926.6324     643325.3201    4318098.1245
     643307.7168    4318117.6961      643269.386    4318193.3329
#Sta/Elev= 30
       0 1072.17    15.2 1067.24   18.24 1067.14   45.61 1062.23   54.73 1060.94
    66.9  1060.1   79.06 1059.85   88.18 1060.09   94.26 1059.73  130.75  1060.4
  136.83 1059.64  152.04  1059.1  173.32 1057.12  194.61 1056.06  203.73  1055.2
  206.77 1055.41  212.62 1054.75  218.47  1054.6  224.32 1055.08  233.09 1055.34
  245.21 1056.21  257.32 1057.57  260.35 1057.48  284.58 1060.57   287.6 1061.19
  293.66 1063.21  299.72 1063.97  305.77 1065.85  311.83 1068.02  317.89    1071
#Mann= 3 , 0 , 0
       0      .2       0  212.62      .2       0  224.32      .2       0
Bank Sta=212.62,224.32
XS Rating Curve= 0 ,0
Exp/Cntr=0.3,0.1

Type RM Length L Ch R = 1 ,974.5115,5.96,5.21,4.46
XS GIS Cut Line= 4
     643360.3085    4317921.3563     643307.3917    4318059.4691
     643297.8667    4318095.9817     643261.3541    4318184.8818
#Sta/Elev= 30
       0 1070.24    3.02 1070.11   18.11 1065.79   24.15 1064.46   30.18 1063.54
   36.22 1063.01   63.39 1059.38   69.42 1058.93   72.44 1058.47   84.52 1055.82
   93.57 1053.33   96.59  1052.7  102.63 1052.39   114.7 1052.85  132.81 1053.68
  141.87 1053.57  156.61 1053.93  159.51 1053.88  168.22 1053.13  176.93 1052.85
  206.66 1053.59  218.67 1054.41  233.69 1056.16   239.7 1056.46  257.72 1059.34
  260.72 1060.09  266.73 1062.21  269.73 1062.88  272.73 1063.31  281.74 1066.33
#Mann= 3 , 0 , 0
       0      .2       0   96.59      .2       0   114.7      .2       0
Bank Sta=96.59,114.7
XS Rating Curve= 0 ,0
Exp/Cntr=0.3,0.1

Type RM Length L Ch R = 1 ,969.3049,5.8,5.49,5.19
XS GIS Cut Line= 4
     643345.7652     4317925.838     643299.7276    4318063.5539
     643294.1713    4318097.6852     643259.2462    4318183.8072
#Sta/Elev= 30
       0 1068.49    12.1 1064.85   18.15 1063.54   27.23 1062.31   30.25 1061.99
   33.28  1061.9    60.5 1058.02   66.55 1057.41   75.63 1055.45   87.73 1052.53
   90.75 1052.22   93.78 1052.21  108.91 1052.49  127.06 1053.14  136.13 1052.97
  150.97 1053.02  159.62 1052.69  171.14 1052.69  194.78 1053.35  197.78 1053.27
  212.76 1054.33  227.75 1056.18  230.75  1056.1  248.74 1058.99  251.74  1059.6
  254.73 1060.54  263.73 1063.75  266.73    1064  269.72 1064.86  272.72 1065.94
#Mann= 3 , 0 , 0
       0      .2       0   87.73      .2       0  108.91      .2       0
Bank Sta=87.73,108.91
XS Rating Curve= 0 ,0
Exp/Cntr=0.3,0.1

Type RM Length L Ch R = 1 ,963.8105,12.21,13.04,13.88
XS GIS Cut Line= 4
     643334.2447    4317923.6844     643293.7634    4318062.9878
     643289.7947    4318095.1347     643257.2508    4318182.8443
#Sta/Elev= 30
       0 1067.18    3.02  1067.1   15.11 1063.77   18.13 1063.19   30.22 1061.45
   36.27 1060.96   63.47 1056.87   66.49 1056.72   69.51 1056.24   78.58 1054.29
   84.62 1052.73   87.64  1052.1   90.67 1051.92  102.76 1051.79  114.84 1052.09
  126.93 1052.37  139.02 1052.09  148.01 1052.41   153.9 1052.32  171.57 1052.49
  198.58 1052.98  210.65 1053.75  219.71 1054.79  225.74 1055.67  231.78 1056.04
  249.88 1059.05  255.92 1061.02  261.96 1063.37  267.99 1064.42  271.01 1065.56
#Mann= 3 , 0 , 0
       0      .2       0   87.64      .2       0  114.84      .2       0
Bank Sta=87.64,114.84
XS Rating Curve= 0 ,0
Exp/Cntr=0.3,0.1

Type RM Length L Ch R = 1 ,950.7658,12.93,12.66,12.39
XS GIS Cut Line= 2
      643314.401       4317921.7     643254.4727    4318181.6536
#Sta/Elev= 30
       0 1065.45    3.07 1064.43    6.13 1063.71     9.2 1063.35   15.33 1061.51
    18.4 1060.97    36.8 1058.35   39.86 1058.27   67.46 1054.16   73.59 1053.65
   76.66 1053.04   82.79 1051.48   88.92 1051.69  104.26 1051.19  110.39 1051.06
  128.79 1051.32  141.05 1050.86  151.28 1051.17  162.52 1051.79  177.85  1051.8
  202.38 1052.31  211.58 1052.91  226.91 1055.55  229.98 1055.96  233.04 1056.08
  248.37 1059.04  251.44  1060.1  260.64 1063.83  263.71 1063.85  266.77 1065.03
#Mann= 3 , 0 , 0
       0      .2       0  104.26      .2       0  151.28      .2       0
Bank Sta=104.26,151.28
XS Rating Curve= 0 ,0
Exp/Cntr=0.3,0.1

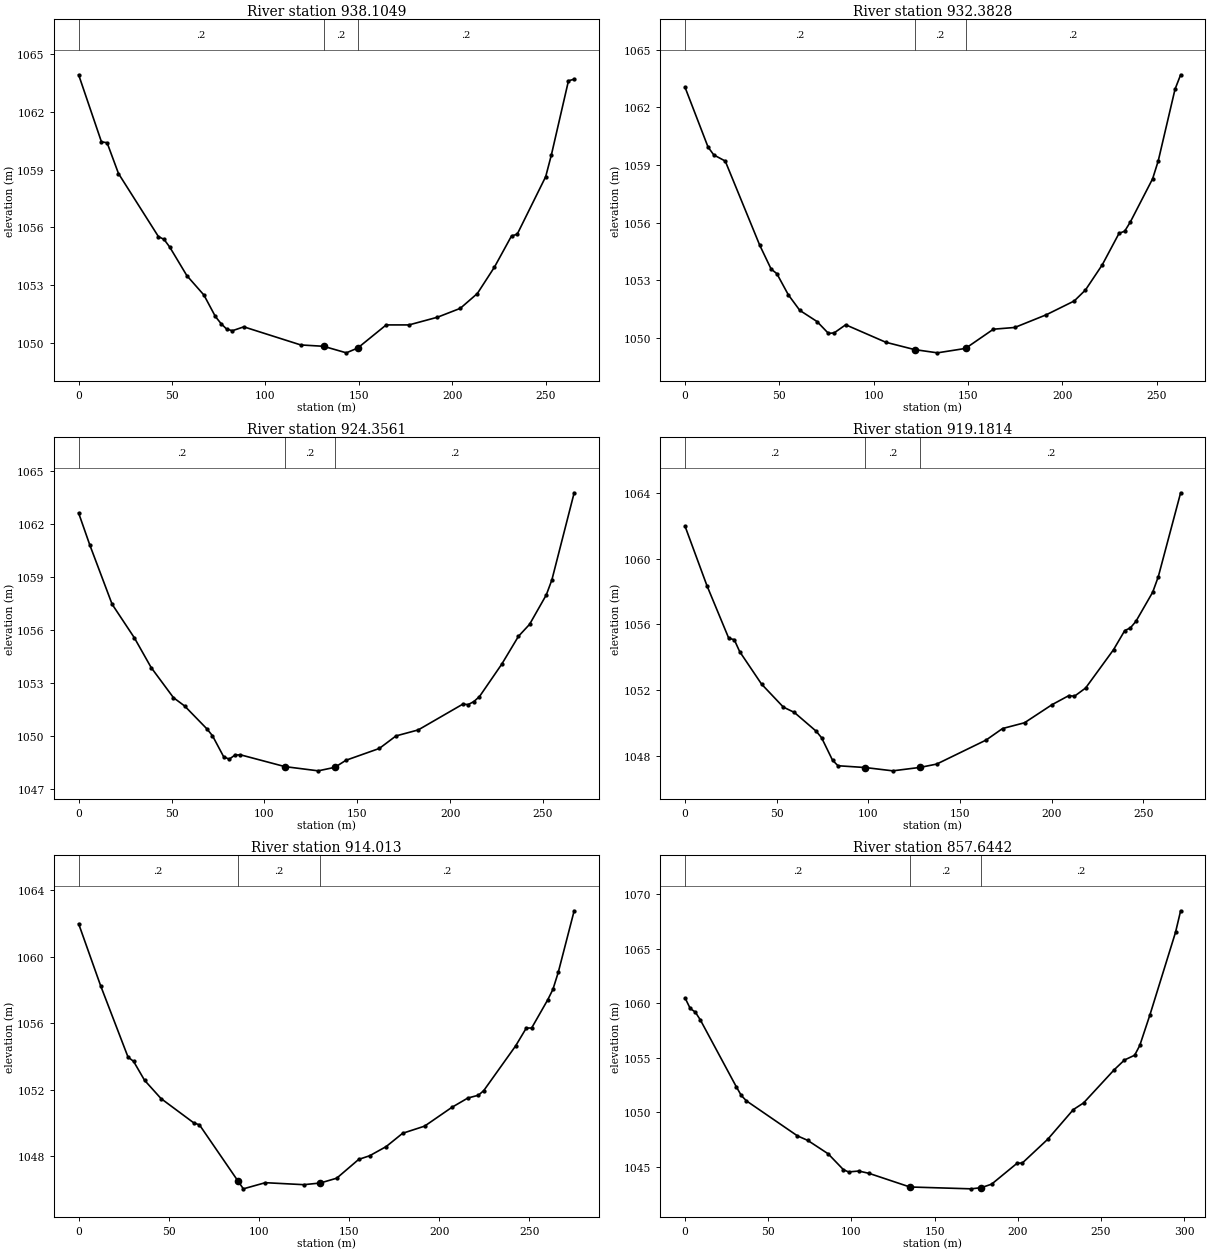
Type RM Length L Ch R = 1 ,938.1049,5.64,5.72,5.8
XS GIS Cut Line= 2
     643296.8083    4317918.1813     643246.0082    4318178.5318
#Sta/Elev= 30
       0 1063.93    12.2 1060.45   15.24  1060.4   21.34  1058.8   42.69 1055.53
   45.73 1055.38   48.78 1054.98   57.93  1053.5   67.08 1052.49   73.18 1051.38
   76.22 1051.01   79.27 1050.72   82.32 1050.64   88.42 1050.84  118.91  1049.9
  131.11 1049.83   143.3 1049.49   149.4 1049.74  164.64 1050.94  176.84 1050.94
  192.09 1051.34  204.28  1051.8  213.43 1052.57  222.57 1053.94  231.72 1055.56
  234.77 1055.65  250.02 1058.64  253.06 1059.77  262.21 1063.62  265.26  1063.7
#Mann= 3 , 0 , 0
       0      .2       0  131.11      .2       0   149.4      .2       0
Bank Sta=131.11,149.4
XS Rating Curve= 0 ,0
Exp/Cntr=0.3,0.1

Type RM Length L Ch R = 1 ,932.3828,10.05,8.03,6
XS GIS Cut Line= 5
     643284.6463    4317917.9004     643264.8025    4318053.2351
     643258.8494     4318082.207     643257.2619    4318107.2102
     643243.3712    4318177.0603
#Sta/Elev= 30
       0 1063.04   12.16 1059.94    15.2 1059.53   21.28 1059.21   39.51 1054.84
   45.59 1053.59   48.63 1053.35   54.71 1052.25   60.79 1051.44   69.91 1050.86
   75.99 1050.24   79.03 1050.27   85.11 1050.69  106.39 1049.78  121.58  1049.4
  133.74 1049.23  148.61 1049.46   163.4 1050.46  174.71 1050.55  191.41 1051.21
  206.25 1051.93  212.18  1052.5  221.09 1053.81  229.99 1055.45  232.96 1055.56
  235.92 1056.03  247.79 1058.29  250.76 1059.22  259.66 1062.95  262.63  1063.7
#Mann= 3 , 0 , 0
       0      .2       0  121.58      .2       0  148.61      .2       0
Bank Sta=121.58,148.61
XS Rating Curve= 0 ,0
Exp/Cntr=0.3,0.1

Type RM Length L Ch R = 1 ,924.3561,6.01,5.17,4.34
XS GIS Cut Line= 4
      643272.729    4317913.7625     643250.9008    4318004.2501
     643255.2665    4318105.8503     643241.3758    4318176.4942
#Sta/Elev= 30
       0 1062.63    6.01 1060.82   18.02 1057.46   30.03 1055.55   39.03 1053.87
   51.05 1052.16   57.05 1051.69   69.06 1050.39   72.06    1050   78.07 1048.81
   81.07 1048.67   84.08  1048.9   87.08 1048.92  111.03 1048.25  128.98 1048.01
  137.95 1048.21  143.93 1048.61  161.88 1049.28  170.85 1049.99  182.81 1050.33
  206.78 1051.79  209.78 1051.77  212.78 1051.94  215.78 1052.22  227.78 1054.06
  236.78 1055.64  242.77 1056.32  251.77 1057.99  254.77 1058.84  266.77 1063.78
#Mann= 3 , 0 , 0
       0      .2       0  111.03      .2       0  137.95      .2       0
Bank Sta=111.03,137.95
XS Rating Curve= 0 ,0
Exp/Cntr=0.3,0.1

Type RM Length L Ch R = 1 ,919.1814,5.84,5.17,4.49
XS GIS Cut Line= 4
     643265.8608    4317913.4687      643238.741    4318001.7735
      643253.981    4318105.5301     643238.1801    4318177.0418
#Sta/Elev= 30
       0 1061.96   11.92 1058.36   23.84 1055.16   26.82 1055.08    29.8 1054.35
   41.72 1052.38   53.64 1050.98    59.6 1050.66   71.52 1049.52    74.5 1049.12
   80.46 1047.76   83.44 1047.42   98.37 1047.31  113.35 1047.11  128.33 1047.32
  137.32 1047.52  164.29 1048.98  173.28 1049.68  185.26 1050.03   200.3 1051.13
  209.45 1051.68   212.5 1051.64  218.61 1052.14  233.86 1054.47  239.97 1055.63
  243.02 1055.79  246.07 1056.19  255.22 1057.96  258.28  1058.9  270.48    1064
#Mann= 3 , 0 , 0
       0      .2       0   98.37      .2       0  128.33      .2       0
Bank Sta=98.37,128.33
XS Rating Curve= 0 ,0
Exp/Cntr=0.3,0.1

Type RM Length L Ch R = 1 ,914.013 ,52.15,56.37,60.59
XS GIS Cut Line= 4
     643257.7443     4317909.699      643226.098    4317995.4074
     643251.7828    4318105.1525     643236.5776    4318174.2829
#Sta/Elev= 30
       0 1061.98   12.18 1058.26   27.41 1053.96   30.45 1053.71   36.55 1052.57
   45.68 1051.47   63.95    1050      67 1049.89   88.32 1046.52   91.36 1046.04
  103.55 1046.41  124.87 1046.29  134.01 1046.39  143.15 1046.68  155.34 1047.81
  161.43 1048.03  170.57 1048.58   179.7 1049.38  191.89 1049.81  207.02 1050.94
  215.87  1051.5  221.77 1051.67  224.72 1051.95  242.42 1054.64  248.31 1055.71
  251.26 1055.71  260.11 1057.39  263.06 1058.03  266.01 1059.05  274.86 1062.76
#Mann= 3 , 0 , 0
       0      .2       0   88.32      .2       0  134.01      .2       0
Bank Sta=88.32,134.01
XS Rating Curve= 0 ,0
Exp/Cntr=0.3,0.1

Type RM Length L Ch R = 1 ,857.6442,22.65,23.23,23.8
XS GIS Cut Line= 2
     643239.6582    4317904.7757     643155.5205    4318190.5263
#Sta/Elev= 30
       0 1060.47    3.07 1059.51    6.14 1059.18    9.21 1058.45   30.71 1052.36
   33.78 1051.54   36.85 1051.05   67.56 1047.84    73.7 1047.43   85.99  1046.2
    95.2 1044.74   98.27 1044.54  104.41 1044.62  110.55 1044.41  135.12 1043.16
  171.97 1042.99  178.11  1043.1  184.26 1043.42  199.61 1045.34  202.68 1045.35
  218.04 1047.54  233.39 1050.25  239.53 1050.86  257.96  1053.9   264.1 1054.79
  270.24 1055.23  273.31 1056.12  279.45 1058.94  294.81 1066.49  297.88 1068.46
#Mann= 3 , 0 , 0
       0      .2       0  135.12      .2       0  178.11      .2       0
Bank Sta=135.12,178.11
XS Rating Curve= 0 ,0
Exp/Cntr=0.3,0.1

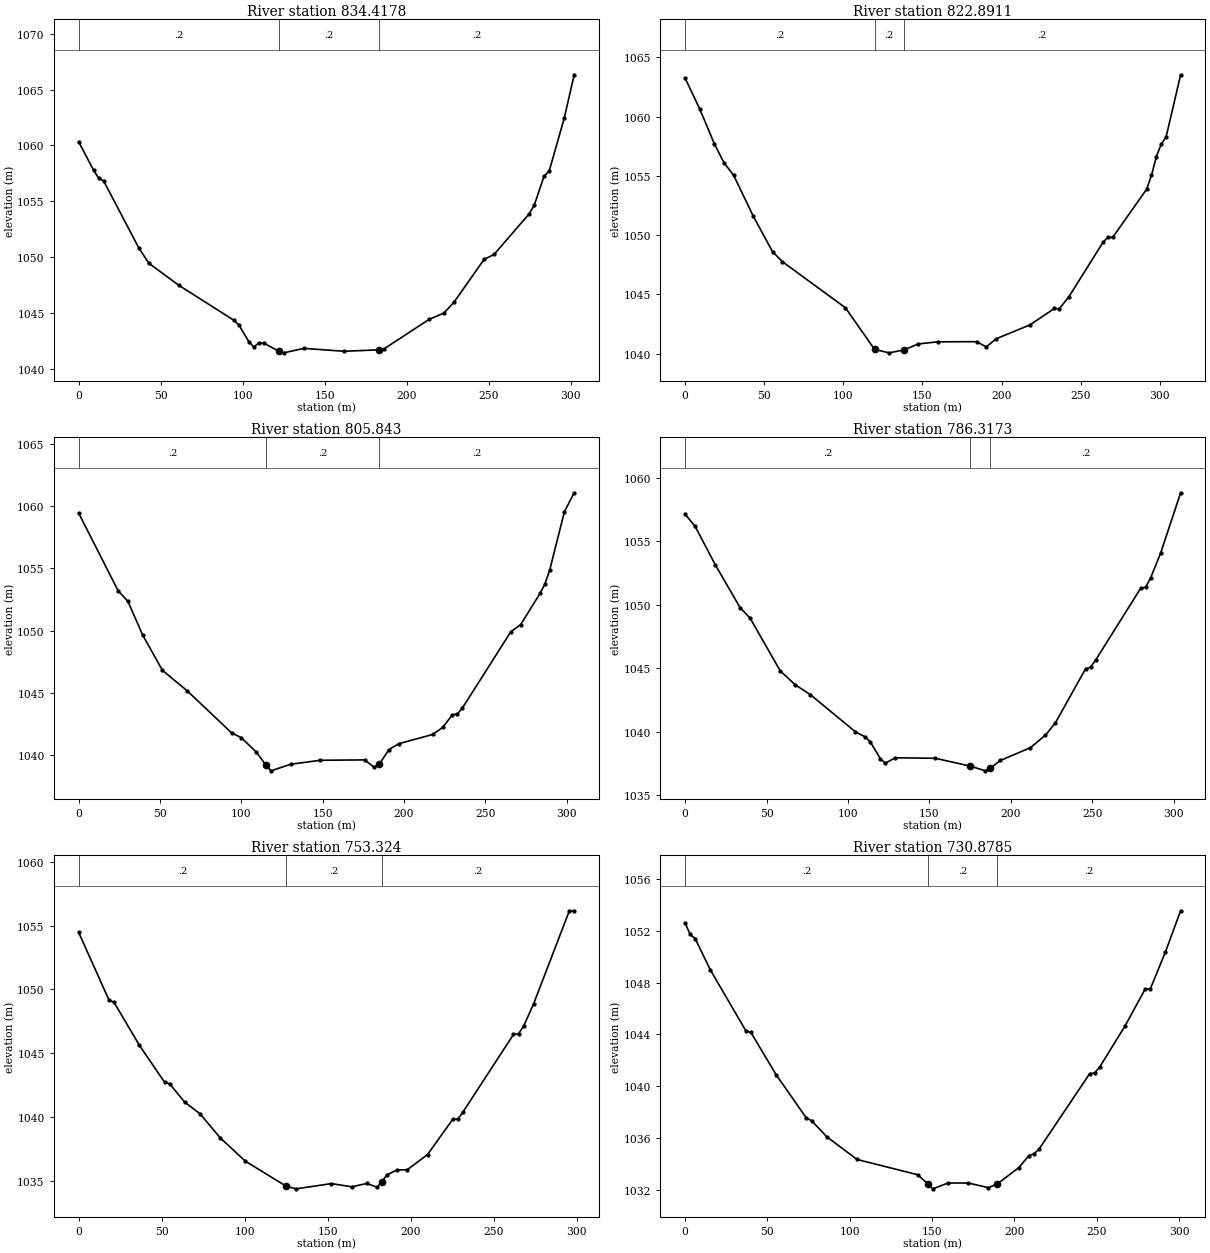
Type RM Length L Ch R = 1 ,834.4178,11.41,11.53,11.65
XS GIS Cut Line= 2
     643230.2633    4317900.6656     643124.2974     4318183.638
#Sta/Elev= 30
       0 1060.33    9.16 1057.76   12.21 1057.07   15.26 1056.81   36.63 1050.84
   42.73 1049.46   61.04 1047.48   94.62 1044.35   97.67 1043.93  103.77 1042.44
  106.83 1041.95  109.88 1042.32  112.93  1042.3  122.09 1041.57  125.14 1041.43
  137.35 1041.83  161.76 1041.57  183.13  1041.7  186.18 1041.78  213.65 1044.42
  222.81    1045  228.91 1045.97  247.22 1049.79  253.33 1050.24  274.69 1053.87
  277.75 1054.62  283.85 1057.26   286.9 1057.69  296.06 1062.41  302.16 1066.32
#Mann= 3 , 0 , 0
       0      .2       0  122.09      .2       0  183.13      .2       0
Bank Sta=122.09,183.13
XS Rating Curve= 0 ,0
Exp/Cntr=0.3,0.1

Type RM Length L Ch R = 1 ,822.8911,18.45,17.05,15.65
XS GIS Cut Line= 2
     643225.9943     4317887.474     643111.7362    4318179.0821
#Sta/Elev= 30
       0 1063.24    9.21 1060.65   18.42 1057.72   24.56  1056.1   30.71 1055.04
   42.99 1051.62   55.27  1048.6   61.41 1047.77  101.33 1043.87  119.75 1040.36
  128.96 1040.07  138.17 1040.31  147.39 1040.82  159.67    1041  184.23 1041.01
  190.37 1040.57  196.51 1041.25  218.01 1042.43  233.36 1043.81  236.43 1043.78
  242.57  1044.8  264.07 1049.38  267.14 1049.82  270.21  1049.8   291.7 1053.87
  294.77 1055.04  297.84 1056.61  300.91 1057.67  303.98 1058.27  313.19 1063.52
#Mann= 3 , 0 , 0
       0      .2       0  119.75      .2       0  138.17      .2       0
Bank Sta=119.75,138.17
XS Rating Curve= 0 ,0
Exp/Cntr=0.3,0.1

Type RM Length L Ch R = 1 ,805.843 ,17.81,19.53,21.24
XS GIS Cut Line= 4
     643209.6257    4317891.1405     643142.5537    4318047.1127
       643135.41    4318082.4347     643098.5005     4318174.113
#Sta/Elev= 30
       0 1059.45   24.25 1053.21   30.32 1052.34   39.41 1049.63   51.54  1046.8
    66.7 1045.16   93.99 1041.78  100.05 1041.38  109.15 1040.24  115.21 1039.17
  118.24 1038.72  130.37 1039.25  148.56 1039.57  175.79  1039.6  181.79    1039
   184.8 1039.25   190.8 1040.43  196.81  1040.9   217.8 1041.65  223.79 1042.21
  229.78 1043.23  232.77 1043.29  235.77 1043.74  265.72 1049.91  271.71 1050.47
  283.68 1052.99  286.68 1053.75  289.67  1054.9  298.66 1059.56  304.65 1061.08
#Mann= 3 , 0 , 0
       0      .2       0  115.21      .2       0   184.8      .2       0
Bank Sta=115.21,184.8
XS Rating Curve= 0 ,0
Exp/Cntr=0.3,0.1

Type RM Length L Ch R = 1 ,786.3173,33.09,32.99,32.9
XS GIS Cut Line= 2
     643196.0019    4317885.7257     643073.7641    4318164.3325
#Sta/Elev= 30
       0 1057.15    6.15 1056.19   18.44 1053.18    33.8 1049.77   39.95 1048.94
   58.39 1044.79   67.61 1043.69   76.83 1042.92  104.49 1039.99  110.63 1039.57
  113.71 1039.18  119.85 1037.87  122.93  1037.5  129.07 1037.93  153.66 1037.89
  175.17 1037.27  184.39  1036.9  187.46 1037.13  193.61 1037.72  212.05 1038.73
  221.27 1039.72  227.41  1040.7  245.85 1044.95  248.93 1045.08     252 1045.63
  279.66  1051.3  282.73 1051.39   285.8 1052.12  291.95 1054.08  304.24 1058.84
#Mann= 3 , 0 , 0
       0      .2       0  175.17      .2       0  187.46      .2       0
Bank Sta=175.17,187.46
XS Rating Curve= 0 ,0
Exp/Cntr=0.3,0.1

Type RM Length L Ch R = 1 ,753.324 ,22.54,22.45,22.35
XS GIS Cut Line= 2
     643161.8706    4317876.2007     643045.1891    4318150.8387
#Sta/Elev= 30
       0 1054.47   18.27 1049.16   21.31 1048.98   36.54 1045.62   51.76 1042.71
   54.81 1042.59   63.94 1041.14   73.08 1040.24   85.26 1038.35  100.48 1036.51
  124.84 1034.57  130.93 1034.35  152.24 1034.76  164.42 1034.51  173.56 1034.77
  179.65 1034.48  182.69 1034.92  185.74 1035.46  191.83 1035.83  197.92 1035.85
   210.1 1037.04  225.32 1039.81  228.36 1039.82  231.41 1040.37  261.86 1046.46
   264.9 1046.51  267.95 1047.11  274.04 1048.88  295.35 1056.11   298.4 1056.16
#Mann= 3 , 0 , 0
       0      .2       0  124.84      .2       0  182.69      .2       0
Bank Sta=124.84,182.69
XS Rating Curve= 0 ,0
Exp/Cntr=0.3,0.1

Type RM Length L Ch R = 1 ,730.8785,34.15,34.8,35.45
XS GIS Cut Line= 2
      643141.151    4317861.9857     643026.8201    4318140.3153
#Sta/Elev= 30
       0 1052.63    3.07 1051.72    6.14  1051.4   15.35 1048.98   36.84 1044.29
   39.91 1044.16   55.27 1040.89   73.69 1037.53   76.76 1037.34   85.97  1036.1
  104.39 1034.34  141.24 1033.16  147.38 1032.45  150.45 1032.07  159.66 1032.52
  171.94 1032.52  184.22 1032.16  189.49 1032.44  202.64 1033.71  208.79 1034.64
  211.86 1034.78  214.93 1035.14  245.63 1040.96   248.7 1041.03  251.77 1041.48
  267.12 1044.65   279.4 1047.51  282.47 1047.51  291.69 1050.38   300.9 1053.55
#Mann= 3 , 0 , 0
       0      .2       0  147.38      .2       0  189.49      .2       0
Bank Sta=147.38,189.49
XS Rating Curve= 0 ,0
Exp/Cntr=0.3,0.1

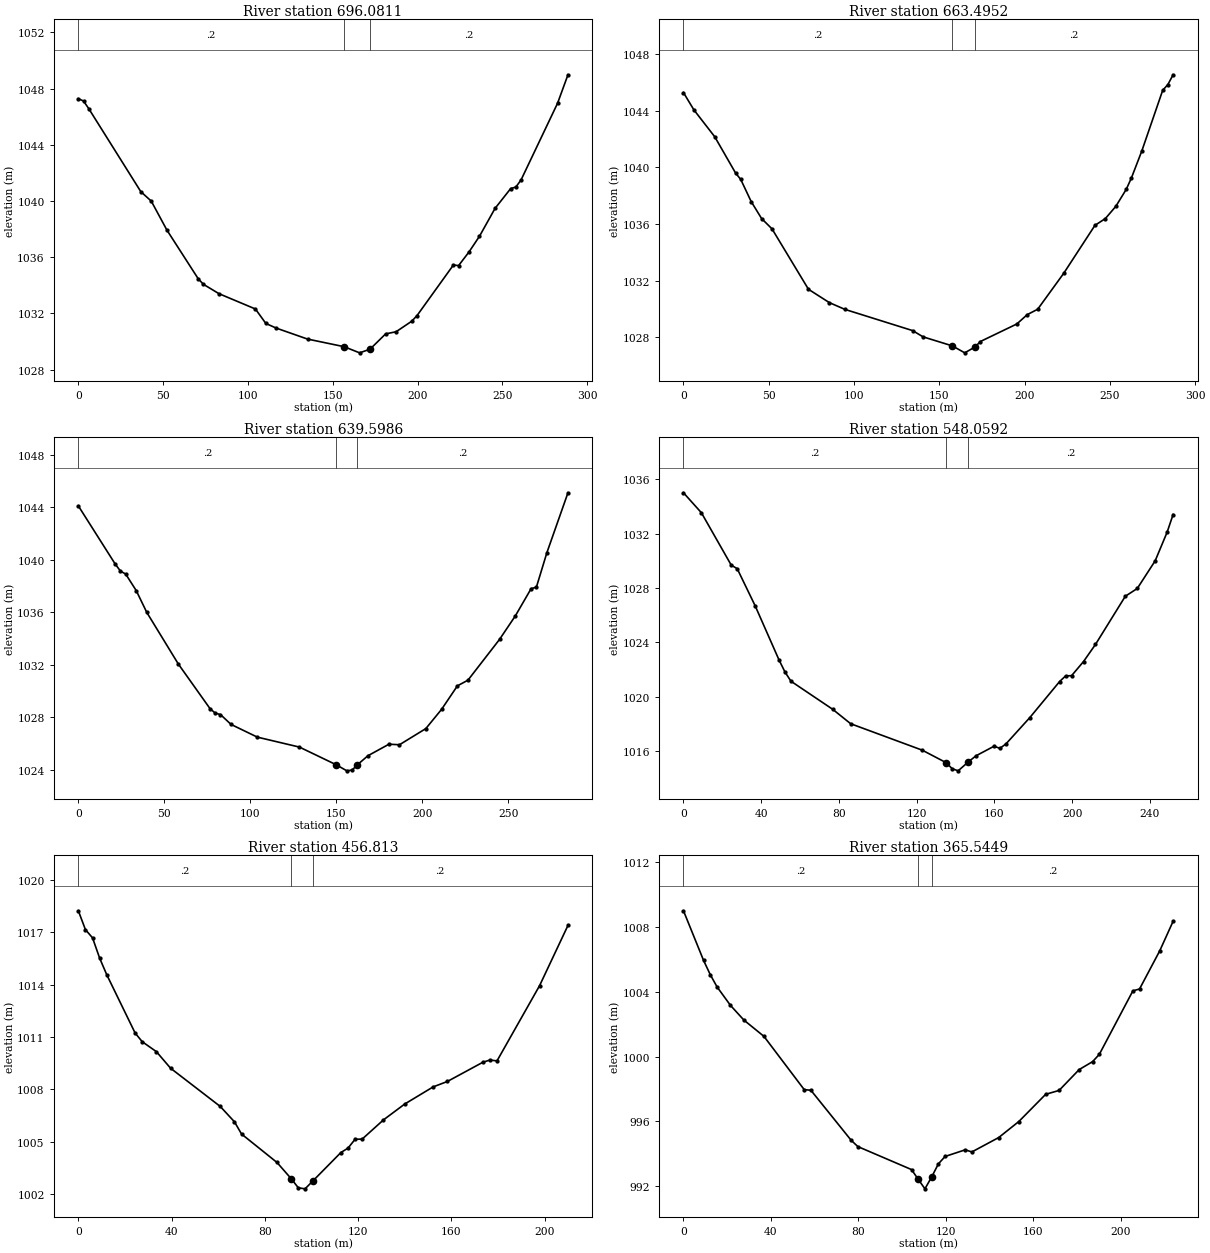
Type RM Length L Ch R = 1 ,696.0811,31.98,32.59,33.19
XS GIS Cut Line= 2
      643115.833    4317868.2632      642984.864    4318125.4387
#Sta/Elev= 30
       0 1047.29    3.07 1047.12    6.14 1046.58   36.84 1040.67   42.98    1040
   52.19 1037.94   70.62 1034.48   73.69 1034.08    82.9 1033.41  104.39 1032.32
  110.53 1031.29  116.67 1030.96  135.09 1030.18  156.58 1029.64  165.79  1029.2
  171.93 1029.46  181.14 1030.55  187.29  1030.7   196.5 1031.45  199.57 1031.84
  221.06 1035.45  224.13 1035.41  230.27 1036.38  236.41 1037.49  245.62 1039.48
  254.83 1040.89   257.9    1041  260.97 1041.51  282.46 1046.96   288.6 1048.99
#Mann= 3 , 0 , 0
       0      .2       0  156.58      .2       0  171.93      .2       0
Bank Sta=156.58,171.93
XS Rating Curve= 0 ,0
Exp/Cntr=0.3,0.1

Type RM Length L Ch R = 1 ,663.4952,23.62,23.9,24.17
XS GIS Cut Line= 2
     643095.1954    4317864.2944     642945.9701    4318109.5636
#Sta/Elev= 30
       0 1045.29    6.11 1044.07   18.33 1042.17   30.54 1039.61    33.6 1039.15
    39.7 1037.59   45.81 1036.39   51.92 1035.66    73.3 1031.39   85.52 1030.45
   94.68 1029.97  134.39 1028.47  140.49 1028.03  157.69 1027.39  164.93  1026.9
  171.04 1027.32  174.09  1027.7  195.47 1028.94  201.58  1029.6  207.69 1029.98
  222.96 1032.52  241.28 1035.91  247.39 1036.39   253.5 1037.25  259.61 1038.45
  262.66 1039.26  268.77 1041.17  280.99 1045.45  284.04 1045.86   287.1 1046.55
#Mann= 3 , 0 , 0
       0      .2       0  157.69      .2       0  171.04      .2       0
Bank Sta=157.69,171.04
XS Rating Curve= 0 ,0
Exp/Cntr=0.3,0.1

Type RM Length L Ch R = 1 ,639.5986,93.16,91.54,89.92
XS GIS Cut Line= 2
     643077.6509    4317857.7524     642921.2966    4318095.7637
#Sta/Elev= 30
       0 1044.11   21.43 1039.68    24.5 1039.14   27.56 1038.91   33.68 1037.65
   39.81 1035.99   58.18 1032.05   76.55 1028.66   79.61 1028.31   82.68  1028.2
    88.8 1027.45  104.11 1026.48  128.61 1025.72  150.04 1024.37  156.17 1023.91
  159.23 1023.97  162.29 1024.37  168.41 1025.06  180.66 1025.94  186.79  1025.9
   202.1 1027.13  211.28  1028.6  220.47 1030.39  226.59 1030.82  244.97 1033.93
  254.15 1035.72  263.34  1037.8   266.4 1037.91  272.53 1040.55  284.77 1045.11
#Mann= 3 , 0 , 0
       0      .2       0  150.04      .2       0  162.29      .2       0
Bank Sta=150.04,162.29
XS Rating Curve= 0 ,0
Exp/Cntr=0.3,0.1

Type RM Length L Ch R = 1 ,548.0592,87.22,91.25,95.27
XS GIS Cut Line= 2
      642964.409     4317812.244     642871.2146    4318046.3231
#Sta/Elev= 30
       0 1035.02    9.22 1033.55   24.58 1029.69   27.65 1029.43   36.87  1026.7
   49.16 1022.71   52.23 1021.82   55.31 1021.14   76.81 1019.07   86.03 1018.01
   122.9 1016.06  135.19 1015.14  138.26  1014.7  141.34 1014.54   146.5 1015.19
  150.55 1015.65  159.77 1016.35  162.84  1016.2  165.92 1016.52  178.21 1018.46
  193.57 1021.12  196.64 1021.53  199.72 1021.55  205.86 1022.59  212.01 1023.85
  227.37  1027.4  233.51 1027.97  242.73 1030.01  248.88 1032.12  251.95 1033.42
#Mann= 3 , 0 , 0
       0      .2       0  135.19      .2       0   146.5      .2       0
Bank Sta=135.19,146.5
XS Rating Curve= 0 ,0
Exp/Cntr=0.3,0.1

Type RM Length L Ch R = 1 ,456.813 ,94.43,91.27,88.11
XS GIS Cut Line= 2
     642903.7829    4317842.3615     642742.4266     4317976.715
#Sta/Elev= 30
       0 1018.23    3.04 1017.15    6.09 1016.68    9.13 1015.52   12.17 1014.57
   24.34 1011.23   27.39 1010.73   33.47 1010.16   39.56 1009.21   60.86 1007.02
   66.95 1006.14   69.99 1005.44    85.2 1003.81   91.29 1002.88   94.33 1002.36
   97.23  1002.3  100.42 1002.73  112.59 1004.38  115.63 1004.63  118.68 1005.14
  121.72 1005.15  130.85 1006.25  139.98 1007.16  152.15 1008.14  158.24 1008.45
  173.45 1009.55   176.5 1009.68  179.54 1009.63   197.8 1013.94  209.97 1017.39
#Mann= 3 , 0 , 0
       0      .2       0   91.29      .2       0  100.42      .2       0
Bank Sta=91.29,100.42
XS Rating Curve= 0 ,0
Exp/Cntr=0.3,0.1

Type RM Length L Ch R = 1 ,365.5449,29.51,29.71,29.92
XS GIS Cut Line= 2
     642812.0087    4317751.9189     642707.2335    4317949.8276
#Sta/Elev= 30
       0 1009.01     9.2 1005.94   12.27 1005.06   15.34 1004.31   21.47 1003.17
   27.61 1002.26   36.81 1001.25   55.22  997.96   58.28  997.92   76.69  994.83
   79.76  994.44   104.3  993.02  107.36  992.42  110.43  991.83   113.5  992.56
  116.57  993.37  119.64  993.83  128.84  994.24  131.91  994.11  144.18     995
  153.38  995.99  165.65  997.67  171.78  997.91  180.99   999.2  187.12  999.69
  190.19 1000.14  205.53 1004.06  208.59 1004.18   217.8 1006.53  223.93 1008.36
#Mann= 3 , 0 , 0
       0      .2       0  107.36      .2       0   113.5      .2       0
Bank Sta=107.36,113.5
XS Rating Curve= 0 ,0
Exp/Cntr=0.3,0.1