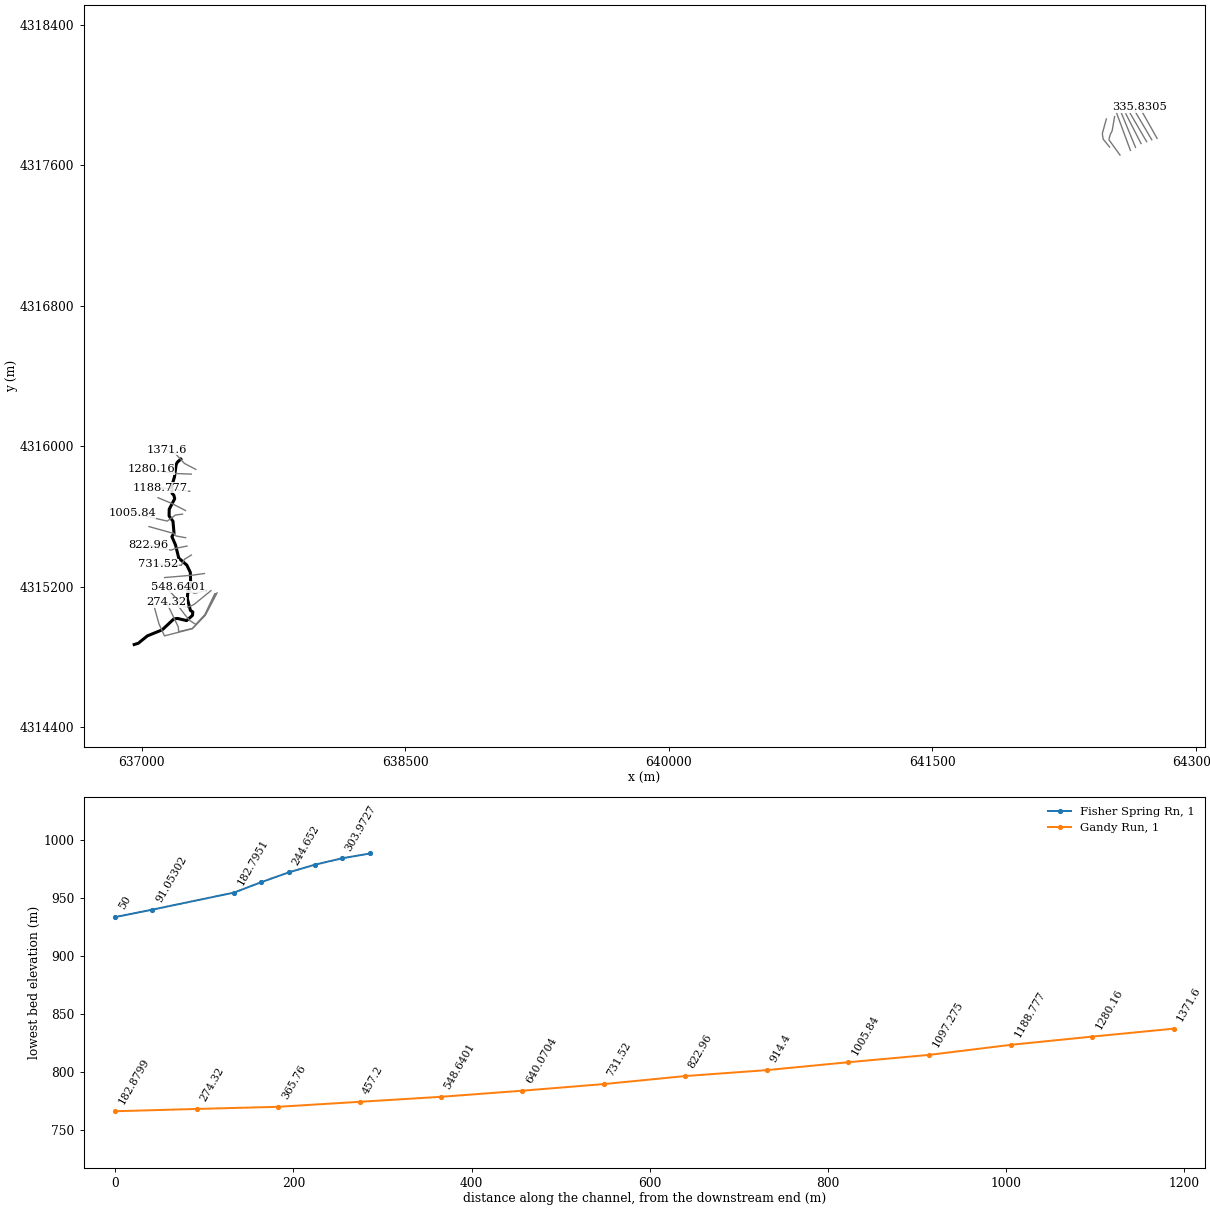
HEC-RAS study RedCreek.prj: RedCreek

--- RedCreek.g01 (geometry) --- (continued)

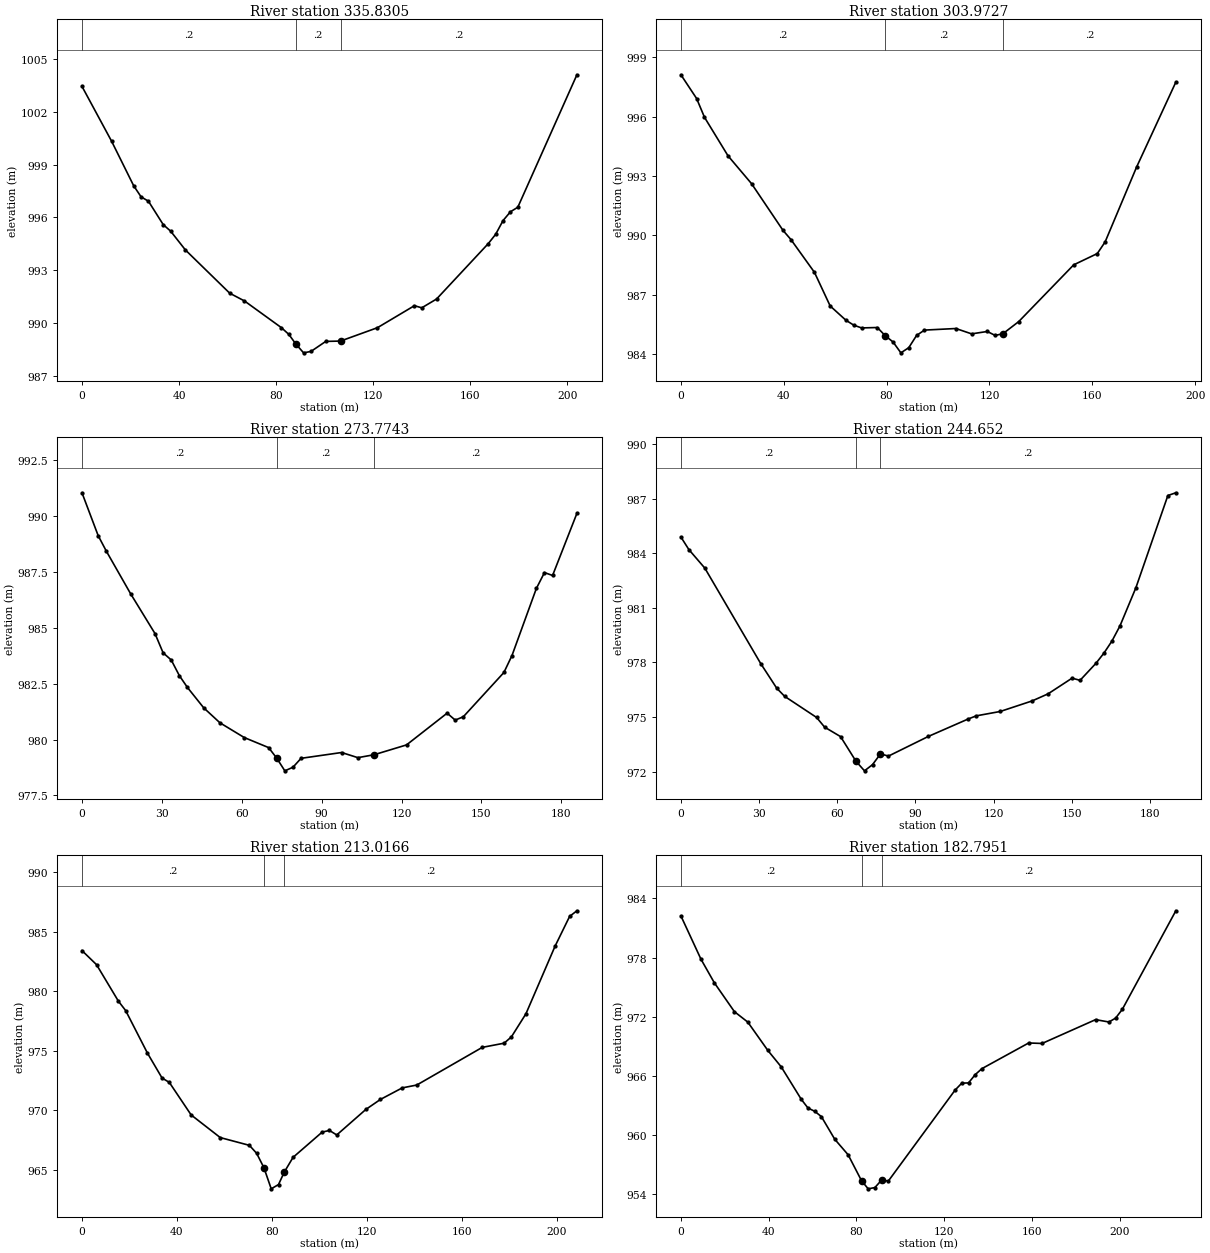
Type RM Length L Ch R = 1 ,335.8305,31.7,31.86,32.01
XS GIS Cut Line= 2
     642780.7904    4317752.4548     642680.7777    4317930.2552
#Sta/Elev= 27
       0 1003.45   12.18 1000.34   21.31   997.8   24.36  997.17    27.4  996.92
   33.49  995.59   36.54  995.22   42.63  994.15    60.9  991.69   66.98  991.25
   82.21  989.73   85.25  989.35   88.16   988.8   91.34   988.3   94.39  988.38
  100.48  988.95  106.57  988.97  121.79  989.73  137.01  990.98  140.06  990.86
  146.15  991.36  167.46  994.51  170.51  995.04  173.55  995.82   176.6  996.32
  179.64  996.58     204 1004.11
#Mann= 3 , 0 , 0
       0      .2       0   88.16      .2       0  106.57      .2       0
Bank Sta=88.16,106.57
XS Rating Curve= 0 ,0
Exp/Cntr=0.3,0.1

Type RM Length L Ch R = 1 ,303.9727,30.24,30.2,30.15
XS GIS Cut Line= 2
     642750.6279    4317744.5173     642652.9964    4317910.4114
#Sta/Elev= 30
       0  998.12    6.11  996.92    9.17  995.97   18.33  994.02    27.5  992.61
   39.72  990.25   42.78  989.79   51.94  988.13   58.05  986.43   64.16  985.71
   67.22  985.46   70.27  985.32   76.39  985.34   79.44  984.93    82.5  984.61
   85.55  984.06   88.61  984.32   91.66  984.94   94.72  985.21  106.94  985.29
  113.05  985.02  119.16  985.14  122.22  984.94  125.27  985.03  131.38  985.64
  152.77  988.51  161.94  989.08  164.99  989.67  177.21  993.45  192.49  997.75
#Mann= 3 , 0 , 0
       0      .2       0   79.44      .2       0  125.27      .2       0
Bank Sta=79.44,125.27
XS Rating Curve= 0 ,0
Exp/Cntr=0.3,0.1

Type RM Length L Ch R = 1 ,273.7743,29.55,29.12,28.69
XS GIS Cut Line= 2
     642721.2126    4317734.0548     642627.8584    4317894.7941
#Sta/Elev= 30
       0  991.04    6.09  989.12    9.14  988.43   18.28  986.52   27.43  984.74
   30.47  983.88   33.52  983.56   36.57  982.86   39.61  982.33   45.71  981.42
    51.8  980.75   60.94  980.09   70.09  979.64   73.13  979.17   76.18   978.6
   79.23  978.76   82.28  979.16   97.51  979.42  103.61  979.19   109.7  979.32
  121.89  979.76  137.13  981.18  140.17  980.87  143.22  981.02  158.46     983
   161.5  983.76  170.65  986.76  173.69  987.47  176.74  987.34  185.88  990.12
#Mann= 3 , 0 , 0
       0      .2       0   73.13      .2       0   109.7      .2       0
Bank Sta=73.13,109.7
XS Rating Curve= 0 ,0
Exp/Cntr=0.3,0.1

Type RM Length L Ch R = 1 ,244.652 ,32.3,31.64,30.97
XS GIS Cut Line= 2
      642689.509     4317723.086     642602.9901    4317892.1551
#Sta/Elev= 29
       0  984.89    3.06   984.2    9.19  983.18   30.63  977.94   36.76  976.59
   39.82  976.14   52.08  974.98   55.14  974.45   61.26  973.93   67.21  972.57
   70.45  972.05   73.52  972.39   76.58  972.98   79.64  972.86   94.96  973.94
  110.28   974.9  113.34  975.07  122.53  975.31  134.78  975.89  140.91  976.28
   150.1  977.14  153.16  977.02  159.29  977.96  162.35  978.52  165.41  979.18
  168.48  980.01   174.6  982.11  186.86  987.17  189.92  987.32
#Mann= 3 , 0 , 0
       0      .2       0   67.21      .2       0   76.58      .2       0
Bank Sta=67.21,76.58
XS Rating Curve= 0 ,0
Exp/Cntr=0.3,0.1

Type RM Length L Ch R = 1 ,213.0166,30.51,30.22,29.93
XS GIS Cut Line= 2
     642657.7589    4317701.6547     642578.3838    4317894.5363
#Sta/Elev= 30
       0   983.4    6.13  982.22   15.34  979.16    18.4  978.37   27.61  974.79
   33.74  972.71   36.81  972.34   46.01  969.61   58.28  967.71   70.55  967.06
   73.61  966.39   76.68  965.18   79.75  963.41   82.82  963.77   85.27  964.82
   88.95  966.05  101.22  968.17  104.29  968.31  107.36  967.93  119.62  970.07
  125.76  970.91  134.96  971.88   141.1  972.12   168.7  975.28   177.9  975.63
  180.97  976.16   187.1   978.1  199.37  983.77  205.51  986.27  208.58  986.74
#Mann= 3 , 0 , 0
       0      .2       0   76.68      .2       0   85.27      .2       0
Bank Sta=76.68,85.27
XS Rating Curve= 0 ,0
Exp/Cntr=0.3,0.1

Type RM Length L Ch R = 1 ,182.7951,101.25,91.74,91.18
XS GIS Cut Line= 2
     642628.9167    4317684.1854     642550.5999    4317895.8525
#Sta/Elev= 30
       0  982.23    9.15  977.83   15.25  975.43    24.4   972.5    30.5  971.44
   39.65  968.56   45.75  966.89    54.9  963.59   57.95  962.71      61  962.38
   64.05  961.84   70.15  959.54   76.25  957.96   82.35  955.33    85.4   954.5
   88.45  954.63   91.67  955.43   94.55  955.28  125.05  964.54  128.09  965.24
  131.14  965.26  134.19   966.1  137.24  966.71  158.59  969.32  164.69  969.27
  189.09  971.69  195.19  971.45  198.24  971.85  201.29  972.74  225.69  982.75
#Mann= 3 , 0 , 0
       0      .2       0   82.35      .2       0   91.67      .2       0
Bank Sta=82.35,91.67
XS Rating Curve= 0 ,0
Exp/Cntr=0.3,0.1

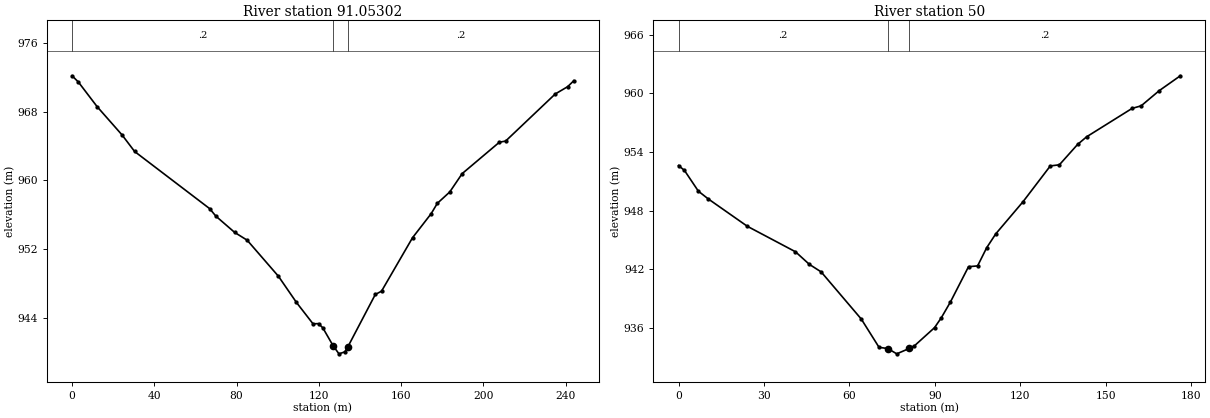
Type RM Length L Ch R = 1 ,91.05302,41.6,41.6,41.6
XS GIS Cut Line= 6
     642569.6499     4317657.727     642507.1709    4317743.8898
      642508.973    4317757.1786     642514.3894     4317774.912
     642525.1361    4317796.5155     642538.9582    4317876.8024
#Sta/Elev= 30
       0  972.19    3.04  971.47   12.16   968.6   24.33  965.29   30.41  963.37
    66.9  956.71   69.94  955.83   79.06  953.94   85.15  953.03  100.35  948.83
  109.11  945.78  117.16  943.29  119.84  943.31  121.93  942.82   126.9  940.75
  129.78  939.79  132.66  940.02  134.16  940.63  147.46  946.71  150.48  947.09
  165.56  953.32  174.61  956.12  177.63  957.33  183.66  958.65   189.7  960.79
   207.8  964.45  210.82  964.58  234.96  970.07  240.99  970.92  244.01  971.62
#Mann= 3 , 0 , 0
       0      .2       0   126.9      .2       0  134.16      .2       0
Bank Sta=126.9,134.16
XS Rating Curve= 0 ,0
Exp/Cntr=0.3,0.1

Type RM Length L Ch R = 1 ,50      ,41,50,38
XS GIS Cut Line= 4
642510.312868476 4317703.4604645642473.8450398814317748.25247136
642468.8901718654317779.96362666642491.9256720484317863.12856687
#Sta/Elev= 30
       0 952.625   2.093 952.116   6.962 949.999  10.418 949.209  24.164 946.404
  41.047   943.8  45.916 942.513  50.061 941.741  64.164 936.912  70.387 934.024
  73.498 933.897   76.61 933.357  80.972 933.907  82.833 934.184  89.856 936.032
  92.226 937.038  95.416 938.644 101.796 942.272 104.986 942.354 108.176 944.214
 111.366 945.634 120.936  948.92 130.507  952.58 133.697 952.697 140.077 954.776
 143.267 955.563 159.217 958.466 162.407  958.73 168.787 960.291 176.152 961.804
#Mann= 3 , 0 , 0
       0      .2       0  73.498      .2       0  80.972      .2       0
Bank Sta=73.498,80.972
XS Rating Curve= 0 ,0
Exp/Cntr(USF)=0,0
Exp/Cntr=0.3,0.1

River Reach=Gandy Run       ,1
Reach XY= 30
     637221.3776    4315926.2187     637200.8723    4315907.3671
     637194.5884     4315892.815     637185.9895    4315826.3383
     637170.1144    4315772.4293     637171.7681    4315731.0881
     637182.0207    4315720.5047     637186.9817    4315700.9917
     637155.5623    4315640.7988     637154.9009    4315602.4342
     637177.0598    4315572.3378     637183.0129     4315503.546
     637170.7759    4315485.0251     637191.6119    4315437.0693
      637209.802    4315362.9858     637256.1042     4315322.306
     637275.7565    4315281.4163     637278.2631    4315205.2276
     637260.7562    4315160.4174     637258.8144    4315130.9059
     637276.6094     4315064.006     637289.9214    4315055.9444
      637288.185    4315036.5554     637254.7813    4315006.7898
     637202.3913    4315018.9627     637182.2498    4315016.5319
     637115.9715    4314954.2224     637031.3941      4314919.77
     636979.4463    4314877.6254     636956.1954    4314870.4384

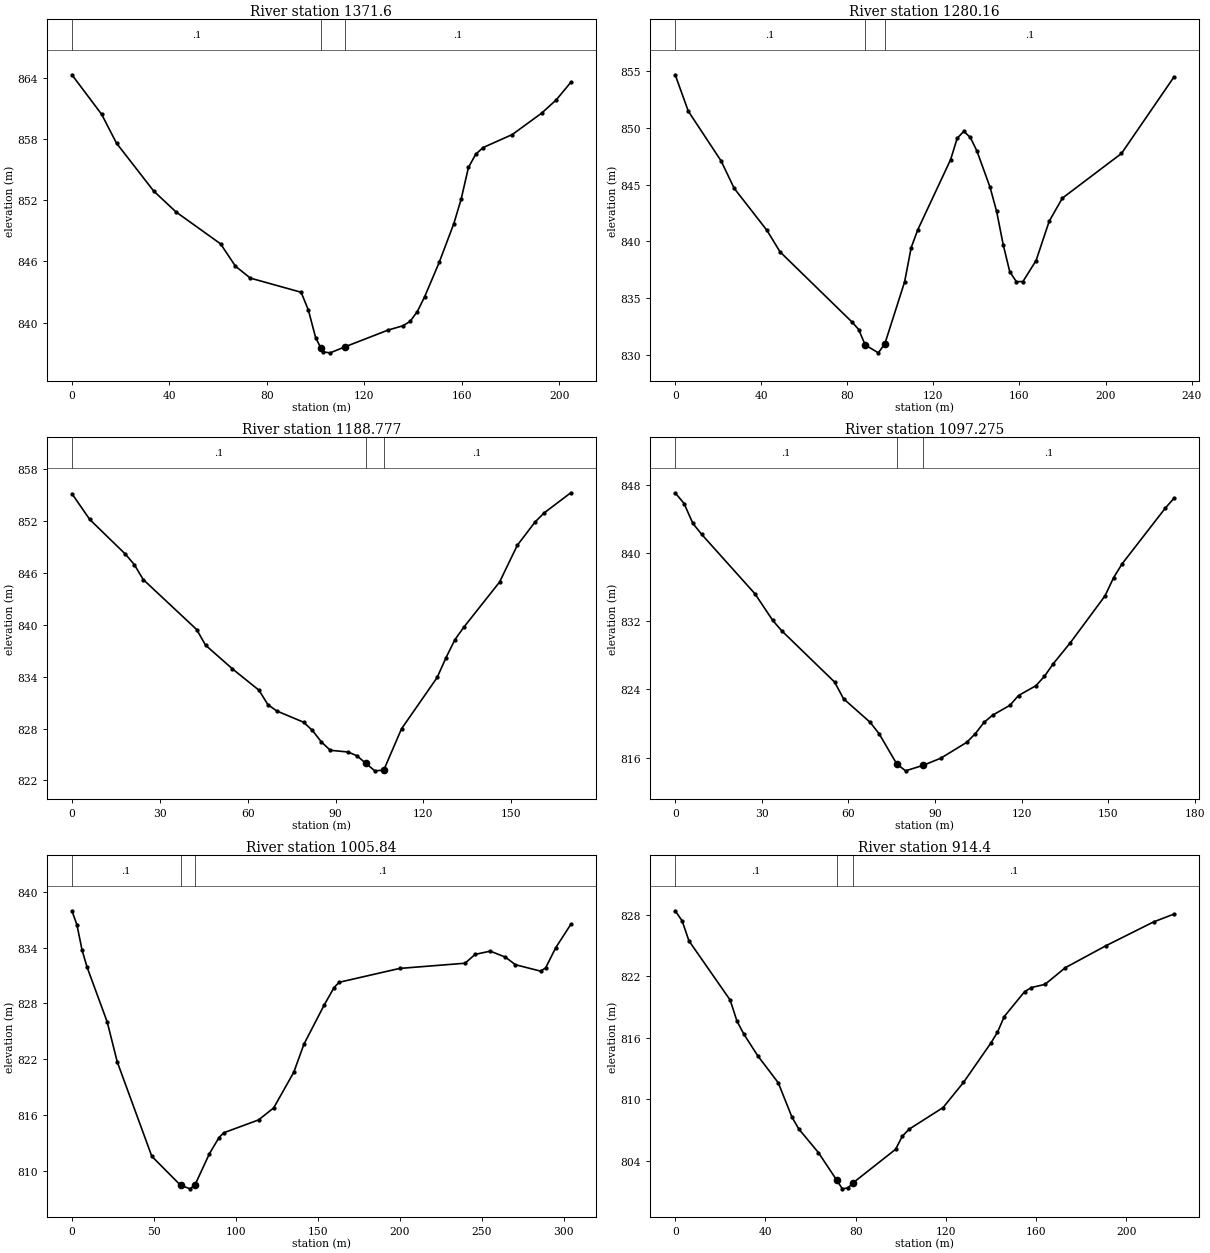
Type RM Length L Ch R = 1 ,1371.6  ,86.38,91.44,95.29
XS GIS Cut Line= 4
     637306.8057    4315867.8062     637241.9582     4315901.754
     637191.5243     4315956.612     637138.9689     4315978.719
#Sta/Elev= 30
       0   864.3    12.2  860.42    18.3  857.59   33.55   852.9    42.7  850.85
      61  847.72    67.1  845.53    73.2  844.36   94.06  842.97   97.04  841.22
  100.02  838.51  102.14  837.52     103  837.12  105.98  837.03  111.95  837.61
  129.83  839.27  135.79  839.68  138.77  840.11  141.75  841.08  144.73  842.52
  150.72   845.9  156.72   849.7  159.72  852.09  162.72  855.21  165.72  856.51
  168.72  857.16  180.72  858.44  192.73  860.53  198.73  861.83  204.73  863.56
#Mann= 3 , 0 , 0
       0      .1       0  102.14      .1       0  111.95      .1       0
Bank Sta=102.14,111.95
XS Rating Curve= 0 ,0
Exp/Cntr=0.3,0.1

Type RM Length L Ch R = 1 ,1280.16 ,91.85,91.38,92.13
XS GIS Cut Line= 3
     637281.6462    4315840.8834     637184.2562    4315844.4905
     637052.1437    4315869.1291
#Sta/Elev= 30
       0  854.65    6.09  851.45   21.32  847.08   27.41  844.67   42.64  840.97
   48.73  839.08   82.23   832.9   85.27  832.25   88.32  830.89   94.41   830.2
   97.46  831.01  106.62  836.44  109.67  839.45  112.73  841.02     128  847.19
  131.05  849.06  134.11  849.68  137.16  849.14  140.22  847.95  146.33  844.76
  149.38  842.64  152.43  839.72  155.49  837.33  158.54  836.46   161.6  836.47
  167.71  838.31  173.81  841.77  179.92   843.8  207.41  847.73  231.85  854.47
#Mann= 3 , 0 , 0
       0      .1       0   88.32      .1       0   97.46      .1       0
Bank Sta=88.32,97.46
XS Rating Curve= 0 ,0
Exp/Cntr=0.3,0.1

Type RM Length L Ch R = 1 ,1188.777,93.59,91.5,90.83
XS GIS Cut Line= 2
     637272.4098    4315742.7903     637103.3864    4315763.7478
#Sta/Elev= 30
       0   855.2    6.08  852.21   18.25   848.2   21.29  846.99   24.33  845.26
   42.58  839.47   45.62  837.66   54.75  834.93   63.87  832.44   66.91  830.77
   69.95  830.04   79.08  828.74   82.12  827.78   85.16  826.46    88.2  825.49
   94.28  825.29   97.32  824.85  100.37  823.97  103.41  823.11  106.45  823.19
  112.53  827.98   124.7  833.92  127.74  836.23  130.78  838.31  133.82  839.75
  145.99  844.96  152.07  849.23  158.15  851.93  161.19  852.96  170.32   855.3
#Mann= 3 , 0 , 0
       0      .1       0  100.37      .1       0  106.45      .1       0
Bank Sta=100.37,106.45
XS Rating Curve= 0 ,0
Exp/Cntr=0.3,0.1

Type RM Length L Ch R = 1 ,1097.275,84.7,91.43,97.49
XS GIS Cut Line= 3
     637248.4914     4315633.279     637169.4435    4315674.0651
     637092.1223    4315706.3042
#Sta/Elev= 30
       0  847.07    3.07  845.81    6.13  843.47     9.2  842.18   27.61  835.22
   33.74  832.11   36.81   830.9   55.21  824.85   58.28   822.9   67.48  820.14
   70.55  818.82   76.68  815.27   79.75  814.44   85.88  815.09   91.94  815.92
  100.92  817.78  103.91   818.8   106.9  820.12  109.89  820.97  115.88  822.13
  118.87  823.28  124.85  824.42  127.84  825.53  130.84  826.99  136.82  829.48
  148.79  834.96  151.78  837.11  154.77  838.75  169.73  845.29  172.72  846.44
#Mann= 3 , 0 , 0
       0      .1       0   76.68      .1       0   85.88      .1       0
Bank Sta=76.68,85.88
XS Rating Curve= 0 ,0
Exp/Cntr=0.3,0.1

Type RM Length L Ch R = 1 ,1005.84 ,101.14,91.44,83.95
XS GIS Cut Line= 4
     637231.1157    4315612.6931     637191.4276    4315608.0508
      637144.284    4315573.3406     636943.6908    4315619.7852
#Sta/Elev= 30
       0  837.96    3.07  836.44    6.15  833.76    9.22  831.91   21.52  826.01
   27.66  821.71   48.74  811.56    66.3  808.44   72.16  808.06   75.08  808.48
   83.87  811.83   89.72  813.57   92.65  814.09  113.87  815.47  123.09  816.76
  135.38   820.6  141.53   823.6  153.82  827.79  159.96  829.71  163.04  830.27
  199.92  831.76  239.87  832.32  246.01  833.27  255.23  833.62  264.45  832.98
   270.6  832.16  285.96  831.47  289.04  831.82  295.18  833.98   304.4   836.5
#Mann= 3 , 0 , 0
       0      .1       0    66.3      .1       0   75.08      .1       0
Bank Sta=66.3,75.08
XS Rating Curve= 0 ,0
Exp/Cntr=0.3,0.1

Type RM Length L Ch R = 1 ,914.4   ,86.34,91.44,102.73
XS GIS Cut Line= 6
     637248.6773    4315478.7277     637194.7414    4315488.5168
     637185.0259    4315499.1869     637177.6225    4315505.5057
     637174.0311    4315505.0202     637040.5285    4315541.9976
#Sta/Elev= 30
       0  828.39    3.05  827.42    6.09  825.46   24.36  819.68   27.41  817.61
   30.45  816.35   36.54  814.26   45.68  811.61   51.77  808.25   54.82  807.09
   63.48   804.8   71.68  802.08   74.11  801.26   76.55  801.35   78.98  801.87
   97.66  805.11  100.67  806.39  103.69  807.08  118.74  809.19  127.78  811.64
  139.82  815.45  142.83  816.53  145.85  818.07  154.88   820.5  157.89   820.9
  163.92  821.21  172.95  822.84  191.02  824.99   212.1  827.31  221.13  828.07
#Mann= 3 , 0 , 0
       0      .1       0   71.68      .1       0   78.98      .1       0
Bank Sta=71.68,78.98
XS Rating Curve= 0 ,0
Exp/Cntr=0.3,0.1

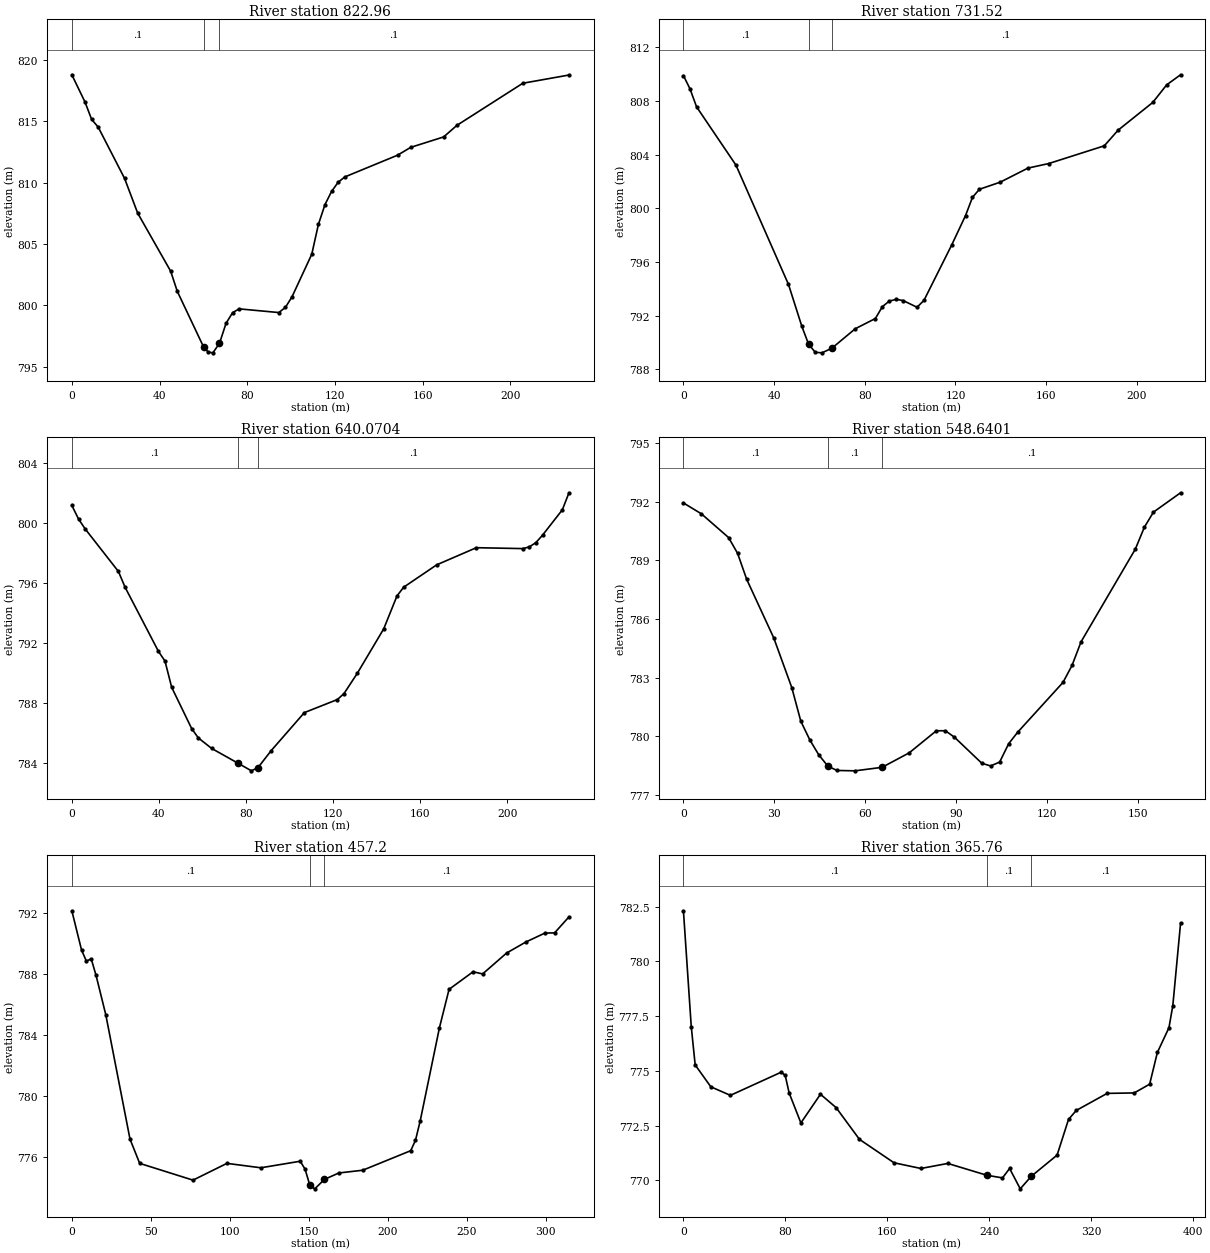
Type RM Length L Ch R = 1 ,822.96  ,86.45,91.44,99.46
XS GIS Cut Line= 5
     637256.9916    4315431.0865     637198.0266    4315419.4414
     637193.9291    4315418.3513     637165.8467    4315407.5851
     637036.5068    4315435.7407
#Sta/Elev= 30
       0  818.78    6.01  816.56    9.02  815.15   12.02  814.52   24.04  810.35
   30.05  807.51   45.08  802.79   48.08  801.16    60.1  796.62   62.22   796.2
   64.34  796.14   67.35  796.91   70.36  798.55   73.37  799.42   76.37  799.72
   94.42  799.42   97.43  799.84  100.44   800.7  109.46  804.17  112.47  806.59
  115.48  808.21  118.49  809.28  121.49  810.03   124.5  810.46  148.57  812.23
  154.59  812.87  169.63  813.72  175.65  814.66  205.73  818.09  226.79  818.76
#Mann= 3 , 0 , 0
       0      .1       0    60.1      .1       0   67.35      .1       0
Bank Sta=60.1,67.35
XS Rating Curve= 0 ,0
Exp/Cntr=0.3,0.1

Type RM Length L Ch R = 1 ,731.52  ,98.24,91.45,84.47
XS GIS Cut Line= 4
      637281.776    4315380.1781     637242.3265    4315355.8412
     637224.9622     4315321.673     637090.4819    4315327.7905
#Sta/Elev= 30
       0   809.9     2.9  808.91    5.79  807.57   23.18  803.22   46.35  794.32
   52.25  791.19    55.2  789.87   58.15  789.26   61.09  789.22   65.45  789.56
   75.83  791.02   84.68  791.78   87.74  792.66    90.8  793.08   93.86  793.21
   96.92  793.12  103.04  792.62   106.1  793.13  118.33  797.26  124.45  799.46
  127.51  800.82  130.57  801.42  139.75  801.95  151.99     803  161.17  803.34
  185.64  804.66  191.76  805.83  207.06   807.9  213.18  809.21   219.3  809.96
#Mann= 3 , 0 , 0
       0      .1       0    55.2      .1       0   65.45      .1       0
Bank Sta=55.2,65.45
XS Rating Curve= 0 ,0
Exp/Cntr=0.3,0.1

Type RM Length L Ch R = 1 ,640.0704,95.21,91.43,88.88
XS GIS Cut Line= 3
     637355.9918    4315274.8076     637283.3243    4315264.8694
     637128.9789    4315251.7888
#Sta/Elev= 30
       0  801.15    3.06  800.25    6.11  799.59   21.39  796.76   24.45  795.71
   39.73  791.46   42.78   790.8   45.84  789.06   55.01  786.32   58.06   785.7
   64.18     785   76.38  784.01   82.46  783.51   85.49  783.73   91.57  784.86
  106.75  787.38  121.94  788.25  124.98  788.65  131.05  789.99   143.2  792.95
  149.27  795.13  152.31  795.71   167.5   797.2  185.72  798.34  206.98  798.28
  210.02  798.39  213.06  798.68  216.09  799.17  225.21  800.86  228.24  801.99
#Mann= 3 , 0 , 0
       0      .1       0   76.38      .1       0   85.49      .1       0
Bank Sta=76.38,85.49
XS Rating Curve= 0 ,0
Exp/Cntr=0.3,0.1

Type RM Length L Ch R = 1 ,548.6401,88.11,91.44,94.97
XS GIS Cut Line= 3
     637363.9293    4315177.1761     637300.0662    4315162.4036
     637208.3261    4315198.2455
#Sta/Elev= 30
       0  791.93    5.96  791.37    14.9  790.16   17.88  789.35   20.86  788.03
    29.8  785.03   35.75  782.49   38.73  780.77   41.71  779.81   44.69  779.04
   47.67  778.47   50.65  778.25   56.61  778.23   65.55  778.41    74.5  779.15
   83.46  780.28   86.44  780.28   89.43  779.95   98.44  778.62  101.36  778.48
  104.35  778.68  107.33  779.62  110.32  780.21  125.24  782.75  128.23  783.62
  131.21  784.83  149.12  789.57   152.1  790.69  155.09  791.46  164.04  792.45
#Mann= 3 , 0 , 0
       0      .1       0   47.67      .1       0   65.55      .1       0
Bank Sta=47.67,65.55
XS Rating Curve= 0 ,0
Exp/Cntr=0.3,0.1

Type RM Length L Ch R = 1 ,457.2   ,119.54,91.44,54.83
XS GIS Cut Line= 6
     637393.2981    4315177.1761     637298.2008    4315099.6069
     637278.7721    4315089.6251     637261.2897    4315083.8645
     637243.1673    4315084.2611     637151.2039    4315181.1449
#Sta/Elev= 30
       0  792.14    6.14  789.57     9.2  788.84   12.27  788.99   15.34   787.9
   21.48  785.33   36.82  777.17   42.95  775.58    76.7  774.48   98.18  775.58
  119.65  775.29  144.56  775.72  147.63   775.2   150.7  774.13  153.77  773.91
   159.9  774.53  169.01  774.95  184.13  775.13  214.49  776.41  217.53  777.09
  220.56  778.39  232.71  784.48  238.78  786.99  253.96  788.14  260.03     788
  275.21  789.37  287.35  790.09   299.5  790.68  305.57  790.69  314.68  791.74
#Mann= 3 , 0 , 0
       0      .1       0   150.7      .1       0   159.9      .1       0
Bank Sta=150.7,159.9
XS Rating Curve= 0 ,0
Exp/Cntr=0.3,0.1

Type RM Length L Ch R = 1 ,365.76  ,102.85,91.44,75.79
XS GIS Cut Line= 6
     637414.8271    4315159.1824     637358.2115    4315039.8392
     637306.7764    4314984.8058     637270.9693    4315008.4857
     637242.0063    4315043.8609     637185.3889    4315118.8624
#Sta/Elev= 30
       0  782.31    6.14  777.02    9.22  775.27    21.5  774.27   36.86  773.88
    76.8  774.94   79.87  774.79   82.94  773.99   92.16  772.62  107.52  773.93
   119.8  773.32  138.12  771.87  165.24   770.8  186.33  770.54  207.42  770.77
  238.08  770.23  250.35  770.11  255.92  770.54  264.28  769.61  272.87  770.18
  293.18  771.15  302.15  772.78  308.21  773.19  332.46  773.97  353.68  773.99
  365.81  774.39  371.87  775.84  380.96  776.97  383.99  777.98  390.06  781.74
#Mann= 3 , 0 , 0
       0      .1       0  238.08      .1       0  272.87      .1       0
Bank Sta=238.08,272.87
XS Rating Curve= 0 ,0
Exp/Cntr=0.3,0.1

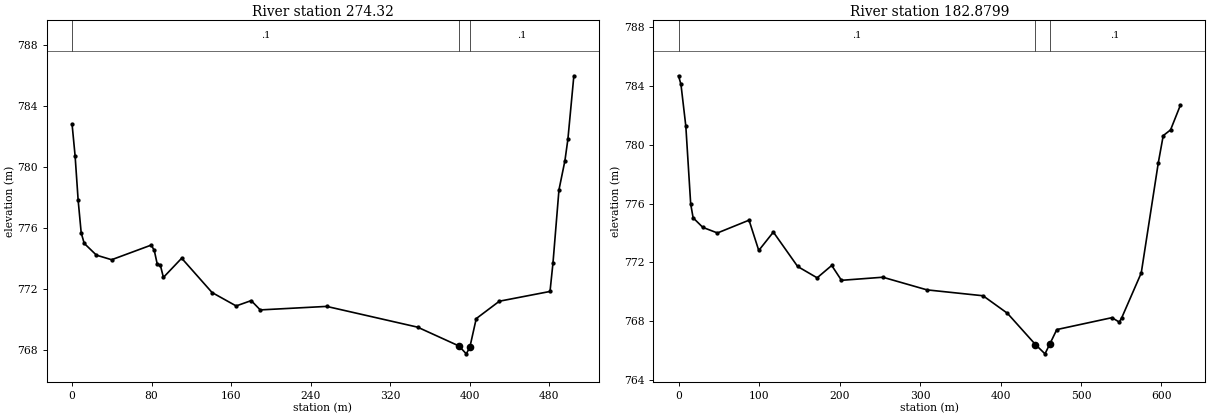
Type RM Length L Ch R = 1 ,274.32  ,90.94,91.44,88.76
XS GIS Cut Line= 6
     637419.3947    4315159.6394     637359.6142    4315038.8404
     637286.8272    4314961.7142      637209.357    4314943.5108
      637207.505    4314969.9692     637139.8003    4315111.2551
#Sta/Elev= 30
       0  782.82    3.06  780.73    6.13  777.82    9.19  775.69   12.25     775
   24.51  774.23   39.82  773.93   79.64  774.89   82.71  774.54   85.77  773.62
   88.83  773.57    91.9  772.77  110.28  774.03  140.84  771.78  165.08   770.9
  180.23  771.25  189.32  770.64  256.13  770.87  347.61  769.51  389.11  768.28
  396.62  767.76  400.16  768.18  406.64  770.07  429.89  771.21  480.87  771.85
  483.87  773.73  489.87  778.51  495.86  780.42  498.86  781.83  504.86  785.99
#Mann= 3 , 0 , 0
       0      .1       0  389.11      .1       0  400.16      .1       0
Bank Sta=389.11,400.16
XS Rating Curve= 0 ,0
Exp/Cntr=0.3,0.1

Type RM Length L Ch R = 1 ,182.8799,95.83,91.44,78.99
XS GIS Cut Line= 6
     637428.2768    4315164.7423     637360.8079    4315036.4191
     637287.3032    4314960.3513     637128.6356    4314919.6715
     637097.2824    4314987.9341     637061.4835    4315116.5467
#Sta/Elev= 30
       0  784.69    3.02   784.1    9.06  781.26    15.1  775.97   18.12  775.03
    30.2  774.38   48.33     774   87.59  774.87   99.67  772.81   117.8  774.06
     148  771.72  172.18  770.95  190.31  771.79   202.4  770.78  253.81  770.99
  308.67  770.13  378.28  769.73  408.55  768.54  443.44  766.41  455.25  765.78
  461.11  766.43  469.91  767.43  538.43  768.24  547.54  767.94  550.57  768.23
  574.84  771.28  596.08  778.79  602.15  780.62  611.25  781.01  623.39  782.68
#Mann= 3 , 0 , 0
       0      .1       0  443.44      .1       0  461.11      .1       0
Bank Sta=443.44,461.11
XS Rating Curve= 0 ,0
Exp/Cntr=0.3,0.1