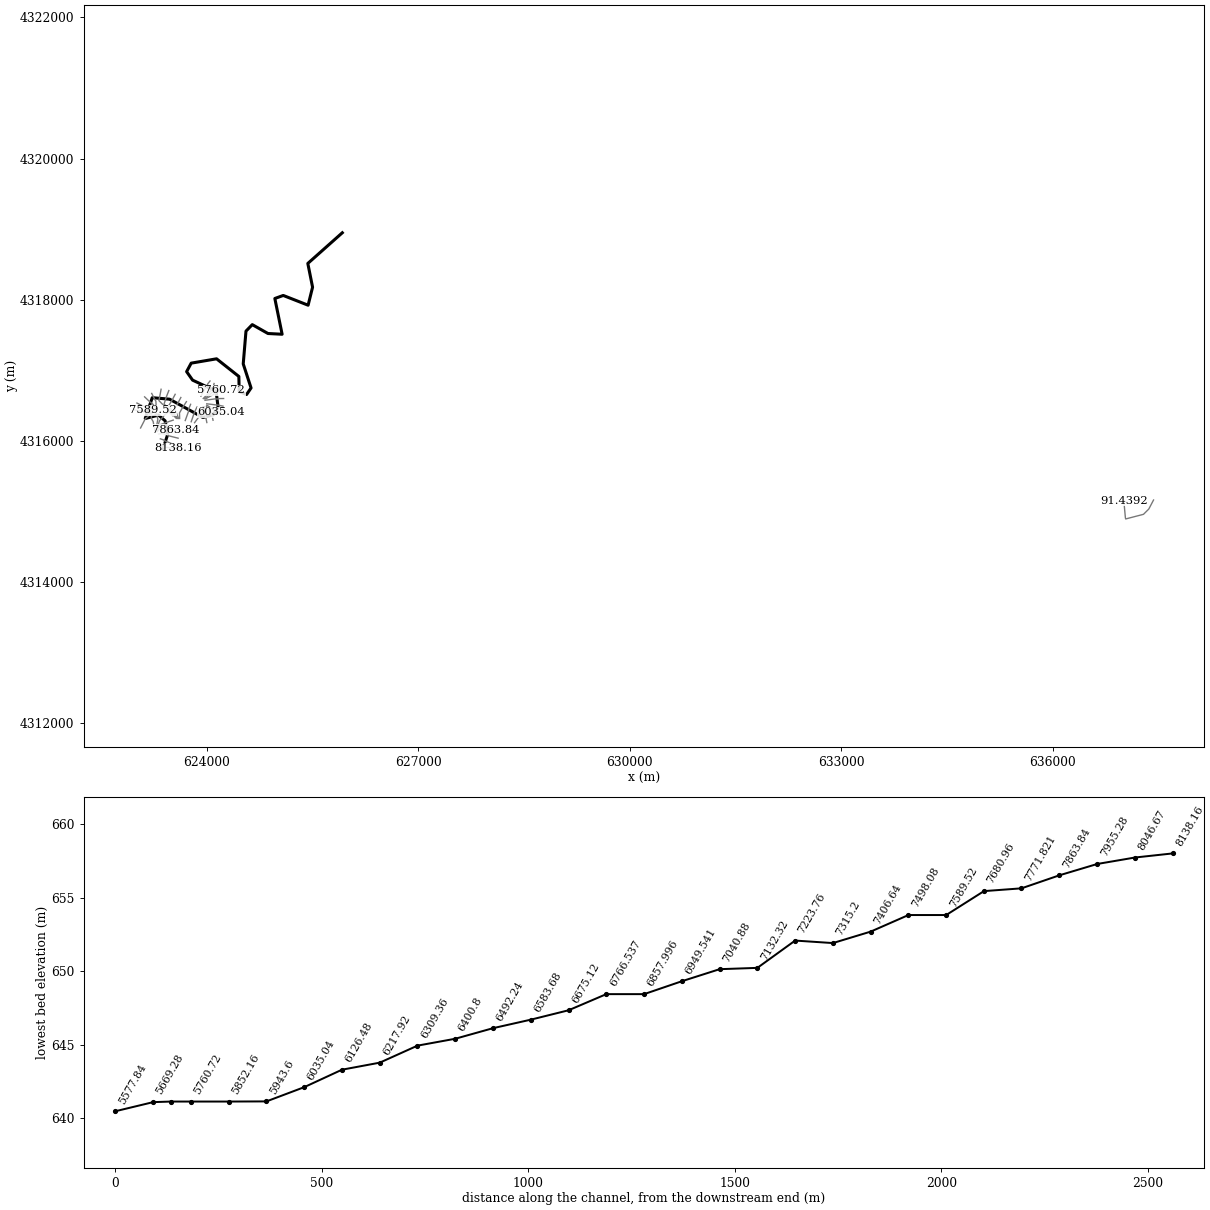
HEC-RAS study RedCreek.prj: RedCreek

--- RedCreek.g01 (geometry) --- (continued)

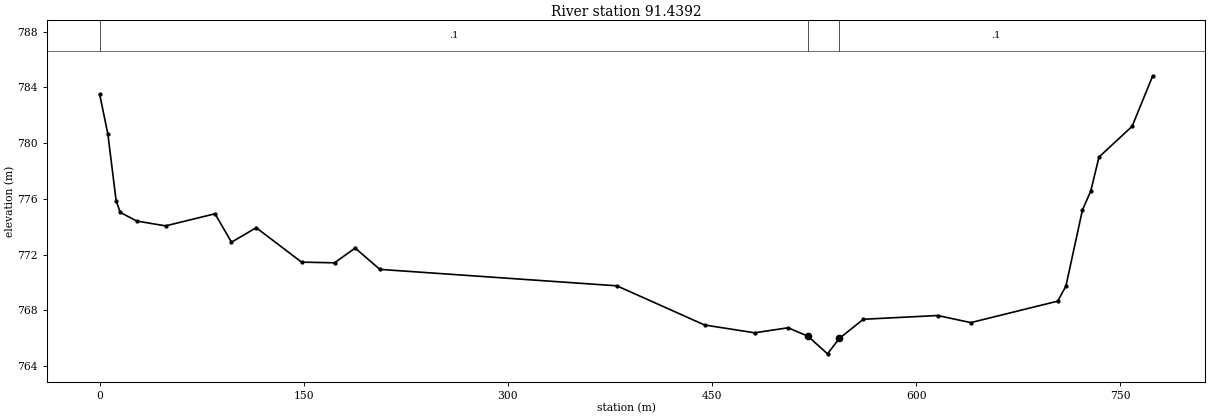
Type RM Length L Ch R = 1 ,91.4392 ,44.54,91.44,84.76
XS GIS Cut Line= 6
     637431.3553     4315161.835     637363.6218    4315033.2472
      637288.226    4314958.7404     637035.9677    4314893.2891
     637031.9744    4314909.8049     637009.6251    4315153.5885
#Sta/Elev= 30
       0  783.52    6.06  780.65   12.11  775.88   15.14  775.04   27.25  774.42
   48.45  774.07   84.78  774.94   96.89   772.9  115.06  773.94  148.36  771.47
  172.59  771.42  187.74  772.48  205.91  770.95  380.04  769.77  444.48  766.96
  481.31   766.4  505.86  766.76  520.49  766.15  534.83  764.89  543.59     766
  561.11  767.37   615.8  767.64  640.11  767.13  703.93  768.67     710  769.75
  722.16  775.22  728.23  776.56  734.31  779.01  758.62  781.21  773.81  784.84
#Mann= 3 , 0 , 0
       0      .1       0  520.49      .1       0  543.59      .1       0
Bank Sta=520.49,543.59
XS Rating Curve= 0 ,0
Exp/Cntr=0.3,0.1

River Reach=Glady Fork      ,1
Reach XY= 30
     623380.2353    4315886.3767     623446.3944    4316087.7306
     623411.3239    4316283.2525     623316.7352    4316364.6121
     623128.2192    4316316.3255     623227.9024    4316611.3353
      623473.735    4316590.2503     623946.4701    4316331.2833
      624090.643     4316365.935     624162.0806    4316474.4144
     624133.6378    4316704.6023     623800.2622    4316860.0454
     623715.5953     4316980.431     623780.4184    4317100.8167
     624140.2524    4317162.3324     624456.4302    4316912.3007
     624461.7218    4316699.3107     624565.7121    4316655.8804
     624629.6273    4316749.1464     624518.6074    4317090.2333
     624557.6335     4317554.578     624646.9305    4317646.5209
     624869.5692    4317520.7357     625070.2647    4317510.2602
     624966.8798    4318016.9371     625086.1397    4318059.9332
     625438.9138    4317921.6656     625502.1979    4318177.0115
      625434.729    4318513.6945     625923.9652     4318948.156

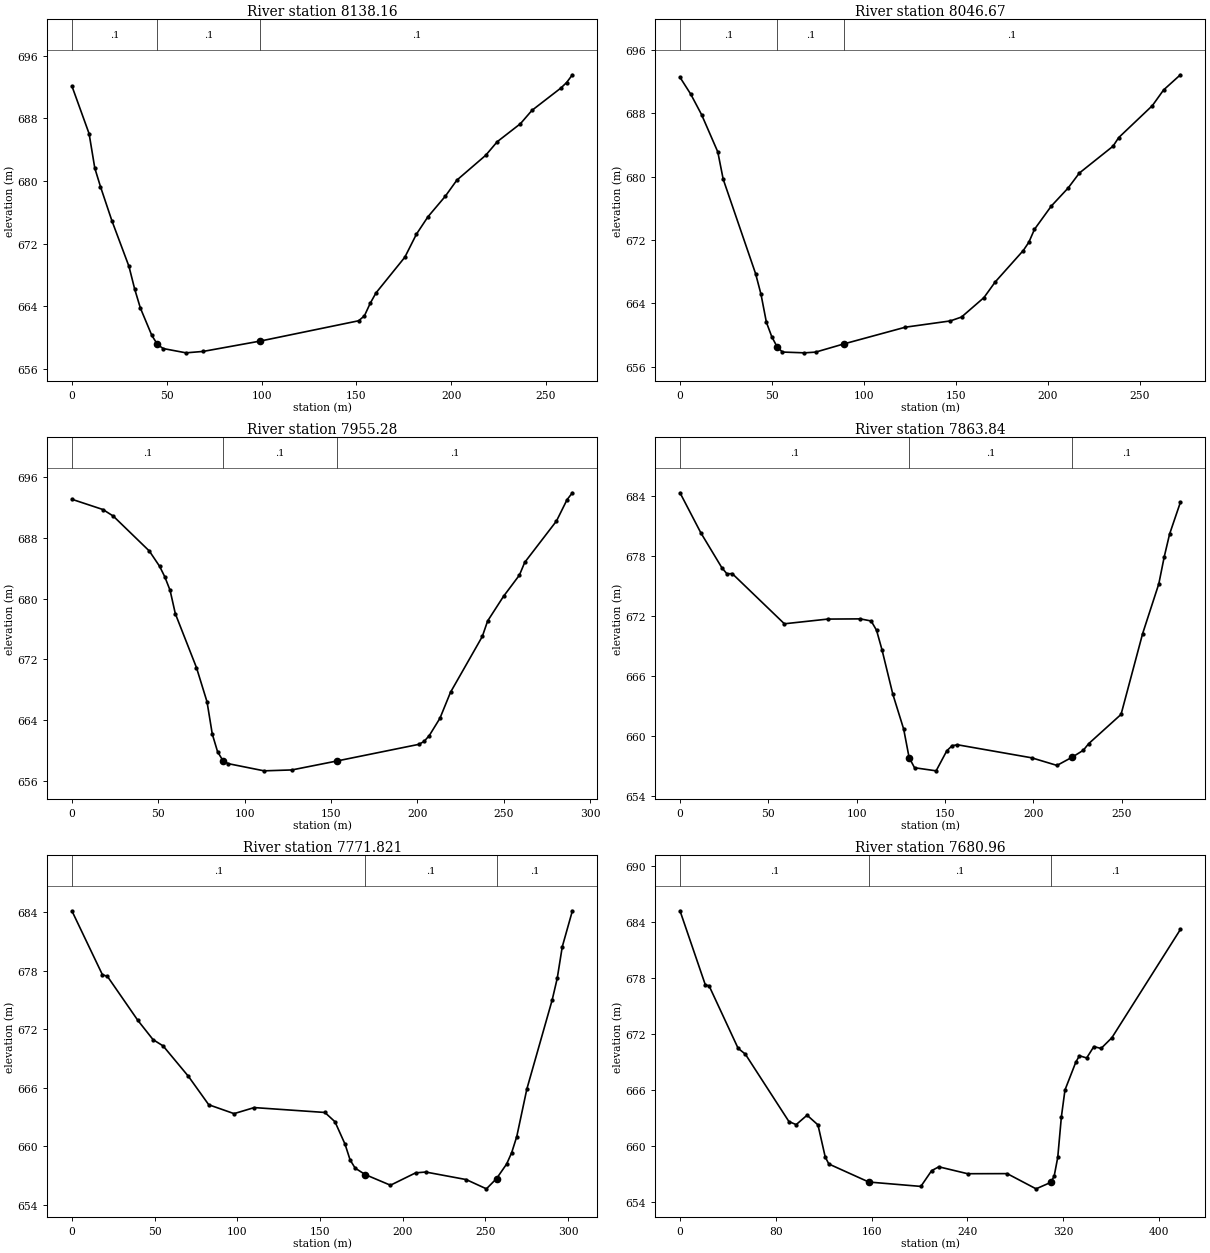
Type RM Length L Ch R = 1 ,8138.16 ,97.4,91.49,83.14
XS GIS Cut Line= 3
     623325.8644    4315925.0516     623408.3811    4315908.5483
     623587.5645    4315893.9555
#Sta/Elev= 30
       0  692.11    9.02  686.05   12.02  681.65   15.03  679.27   21.04  674.92
   30.05  669.08   33.06  666.18   36.06  663.76   42.08  660.27   45.08   659.1
   48.09  658.58   60.11  658.03   69.12  658.21   99.39  659.54  151.19  662.13
  154.23  662.76  157.28  664.36  160.33  665.69  175.56  670.26  181.66   673.2
  187.75  675.43  196.89  678.05  202.99  680.11  218.22  683.29  224.32  685.03
   236.5  687.32   242.6  689.03  257.83  691.88  260.88  692.59  263.93  693.58
#Mann= 3 , 0 , 0
       0      .1       0   45.08      .1       0   99.39      .1       0
Bank Sta=45.08,99.39
XS Rating Curve= 0 ,0
Exp/Cntr=0.3,0.1

Type RM Length L Ch R = 1 ,8046.67 ,86.06,91.39,92.25
XS GIS Cut Line= 4
     623342.8988    4316028.4591     623387.5087    4316013.8029
     623398.3686     4316004.137      623592.733    4315923.3799
#Sta/Elev= 30
       0  692.55    5.87  690.41   11.74  687.83   20.54  683.13   23.48  679.68
   41.09  667.75   44.02  665.15   46.96  661.61   49.86   659.8   52.77  658.51
   55.68  657.85    67.6  657.75    73.7  657.84   88.95  658.87   122.5  660.99
   146.9  661.78     153  662.27  165.21  664.73  171.31   666.7  186.56  670.67
  189.61  671.72  192.66  673.35  201.81  676.29  210.96  678.57  217.06  680.46
  235.36  683.85  238.41  684.93  256.72  688.97  262.82  690.95  271.97  692.87
#Mann= 3 , 0 , 0
       0      .1       0   52.77      .1       0   88.95      .1       0
Bank Sta=52.77,88.95
XS Rating Curve= 0 ,0
Exp/Cntr=0.3,0.1

Type RM Length L Ch R = 1 ,7955.28 ,79.76,91.44,97.66
XS GIS Cut Line= 6
     623318.9404    4316096.8068     623372.2159    4316103.6887
     623418.3945     4316089.884     623433.4758    4316090.0428
     623449.0037    4316074.4532     623594.7661    4316037.6155
#Sta/Elev= 30
       0  693.12   17.91  691.77   23.87  690.91   44.77   686.3   50.73  684.28
   53.72   682.9   56.78  681.12   59.83  678.03   72.06  670.93   78.17  666.42
   81.23  662.15   84.29  659.83   87.35  658.67    90.4  658.26   111.2  657.31
  127.34  657.43  153.62  658.62  200.74   660.8  203.81  661.18  206.88  661.97
  213.02  664.24  219.15  667.67  237.56  675.03  240.63  677.07  249.83  680.32
  259.04  683.12  262.11   684.8  280.51  690.26  286.65  693.08  289.72  693.98
#Mann= 3 , 0 , 0
       0      .1       0   87.35      .1       0  153.62      .1       0
Bank Sta=87.35,153.62
XS Rating Curve= 0 ,0
Exp/Cntr=0.3,0.1

Type RM Length L Ch R = 1 ,7863.84 ,85.63,92.02,121.66
XS GIS Cut Line= 6
     623301.9629    4316133.0768     623341.2111    4316177.2248
     623423.4053    4316166.8462     623474.7461    4316165.8555
     623500.2374    4316162.0484     623564.0509    4316155.7676
#Sta/Elev= 30
       0  684.28   11.81  680.28   23.63  676.82   26.58  676.19   29.54  676.22
   59.07  671.21   83.62  671.68  102.03   671.7  108.17  671.49  111.23  670.56
   114.3  668.62  120.44  664.18  126.58   660.7  129.64  657.87  132.71  656.85
  144.94  656.54  150.98  658.54     154  659.05  157.02  659.14     199  657.84
  213.32  657.08   222.1  657.92   228.2  658.59  231.26  659.25  249.58  662.17
  261.79  670.23  270.95   675.2     274  677.88  277.06  680.17  283.16  683.33
#Mann= 3 , 0 , 0
       0      .1       0  129.64      .1       0   222.1      .1       0
Bank Sta=129.64,222.1
XS Rating Curve= 0 ,0
Exp/Cntr=0.3,0.1

Type RM Length L Ch R = 1 ,7771.821,87.64,90.86,120.6
XS GIS Cut Line= 4
     623294.0254    4316135.7227     623332.3183    4316225.9302
     623458.6578    4316271.3301     623525.4235    4316293.4898
#Sta/Elev= 30
       0  684.09   18.37  677.58   21.44   677.4   39.81   672.9      49  670.93
   55.12  670.28   70.44  667.16   82.69  664.26      98  663.35   110.2  663.97
  152.92  663.47  159.02  662.52  165.12  660.22  168.17  658.61  171.23  657.77
  177.33  657.11  192.58  656.02  207.84  657.29  213.94  657.37  238.36   656.6
   250.6  655.65  256.72   656.7  262.83  658.19  265.89  659.36  268.95     661
  275.07  665.88  290.36  674.98  293.42   677.2  296.48  680.44   302.6  684.12
#Mann= 3 , 0 , 0
       0      .1       0  177.33      .1       0  256.72      .1       0
Bank Sta=177.33,256.72
XS Rating Curve= 0 ,0
Exp/Cntr=0.3,0.1

Type RM Length L Ch R = 1 ,7680.96 ,42.77,91.44,208.08
XS GIS Cut Line= 6
      623283.442    4316135.7227     623331.3997    4316285.8956
      623353.625    4316307.7903     623403.5924     4316367.751
     623460.8977    4316411.9738     623516.2758    4316356.6502
#Sta/Elev= 30
       0  685.25   21.22  677.29   24.25  677.22   48.51  670.52   54.57  669.89
   90.95  662.67   97.01  662.34  106.11  663.35   115.2  662.31  121.27  658.87
   124.3  658.12  157.64  656.19  201.12  655.72  210.13  657.41  216.13  657.82
  240.15  657.08  273.19  657.09  297.32  655.46  309.39  656.14   312.4   656.8
  315.42  658.83  318.44  663.16  321.45  666.05   330.5  669.03  333.52  669.72
  339.55  669.48  345.57   670.7  351.59   670.5  360.62  671.65  417.83  683.25
#Mann= 3 , 0 , 0
       0      .1       0  157.64      .1       0  309.39      .1       0
Bank Sta=157.64,309.39
XS Rating Curve= 0 ,0
Exp/Cntr=0.3,0.1

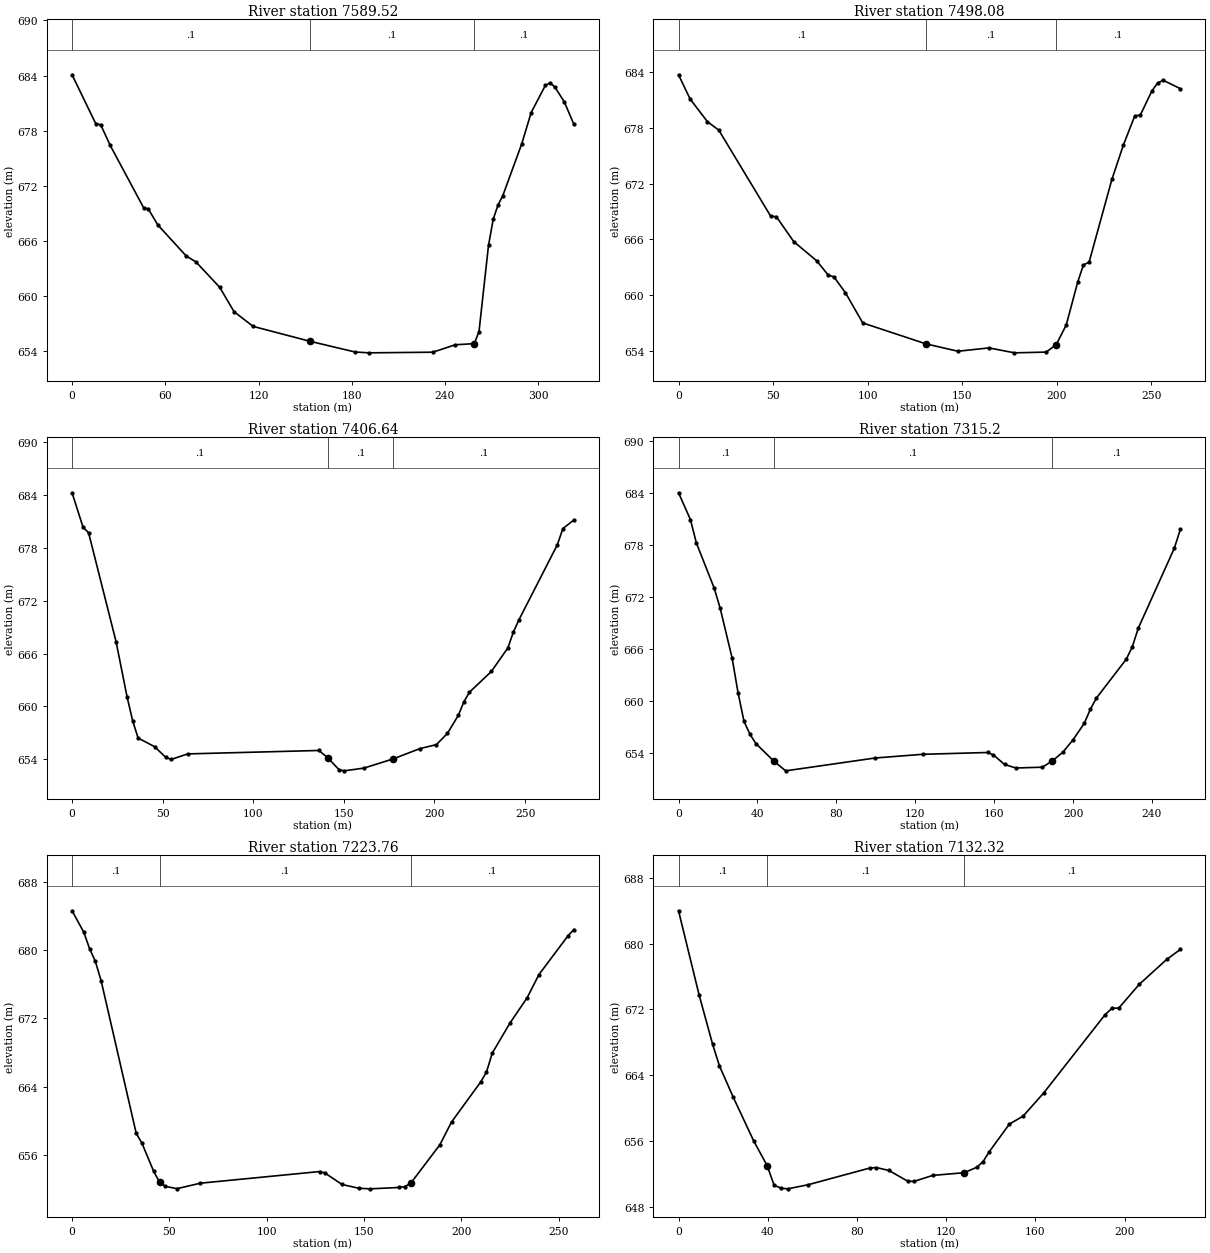
Type RM Length L Ch R = 1 ,7589.52 ,76.85,91.44,102.98
XS GIS Cut Line= 6
     623276.8274    4316141.0143     623307.2207    4316306.8803
     623303.0813    4316319.7852     623296.8956    4316351.8956
     623292.5104    4316383.3229     623232.0789    4316429.9118
#Sta/Elev= 30
       0  684.09   15.33  678.74    18.4  678.66   24.53  676.41   45.99  669.64
   49.06  669.49   55.19  667.75   73.58  664.35   79.71  663.73   95.04  660.96
  104.24  658.31  116.51  656.71   153.3  655.08  182.18  653.92  191.29  653.83
  232.25   653.9  246.67  654.71  258.88  654.83  261.93  656.15  268.04  665.52
  271.09  668.38  274.14  669.91  277.19  670.91   289.4  676.56  295.51  679.98
  304.66  682.94  307.72  683.22  310.77  682.75  316.87  681.13  322.98   678.7
#Mann= 3 , 0 , 0
       0      .1       0   153.3      .1       0  258.88      .1       0
Bank Sta=153.3,258.88
XS Rating Curve= 0 ,0
Exp/Cntr=0.3,0.1

Type RM Length L Ch R = 1 ,7498.08 ,134.3,91.44,75.96
XS GIS Cut Line= 6
     623265.5441    4316142.2052     623240.7044    4316273.8293
     623228.0043    4316295.2606     623221.0617    4316306.4482
     623214.1589    4316324.9602      623223.771    4316397.9192
#Sta/Elev= 30
       0  683.68    6.09  681.09   15.22  678.66   21.31  677.73   48.71  668.51
   51.75  668.44   60.89  665.78   73.06  663.71   79.15  662.18   82.19  661.98
   88.28  660.28   97.42  657.04   130.9  654.79  147.79     654  164.13  654.36
  177.67  653.83  194.44  653.91  199.74  654.71  205.05  656.83  211.08  661.41
   214.1  663.26  217.12  663.56  229.18  672.45  235.21  676.11  241.24  679.25
  244.26  679.37  250.29  681.93  253.31  682.79  256.32  683.09  265.37  682.19
#Mann= 3 , 0 , 0
       0      .1       0   130.9      .1       0  199.74      .1       0
Bank Sta=130.9,199.74
XS Rating Curve= 0 ,0
Exp/Cntr=0.3,0.1

Type RM Length L Ch R = 1 ,7406.64 ,142.91,91.44,60.67
XS GIS Cut Line= 6
     623062.5145    4316182.0248     623121.9024    4316298.3323
     623134.2616     4316316.993     623147.3747     4316330.473
     623154.7146    4316332.1965     623221.9189    4316402.3113
#Sta/Elev= 30
       0  684.23    6.07  680.32    9.11   679.7    24.3  667.33   30.37  661.07
   33.41   658.4   36.44  656.42   45.56  655.44   51.63  654.24   54.67  653.99
   63.78  654.62  136.19  655.01  141.08  654.19  147.38  652.82  150.18   652.7
  161.05  653.01   177.3  654.06  191.95  655.22  201.06  655.67  207.13  656.94
   213.2     659  216.23  660.52  219.27  661.61  231.41  663.97  240.51  666.64
  243.55  668.43  246.58  669.81  267.83  678.34  270.86  680.17  276.93  681.14
#Mann= 3 , 0 , 0
       0      .1       0  141.08      .1       0   177.3      .1       0
Bank Sta=141.08,177.3
XS Rating Curve= 0 ,0
Exp/Cntr=0.3,0.1

Type RM Length L Ch R = 1 ,7315.2  ,81.39,91.44,89.03
XS GIS Cut Line= 6
     622977.8477    4316438.6712     623128.7229    4316408.4583
     623149.7932    4316393.9148     623156.6396    4316390.8902
     623171.3921    4316385.5269     623218.3691     4316407.162
#Sta/Elev= 30
       0  684.04    6.03  680.94    9.05  678.24    18.1  673.01   21.12  670.69
   27.15  664.96   30.17  660.94   33.19  657.64    36.2  656.15   39.22  655.07
   48.27  653.05   54.31  651.92   99.56   653.4   123.7  653.83  156.72  654.04
  159.56  653.77  165.25  652.66  170.94  652.25  184.46  652.34  189.57  653.08
  194.81  654.07  200.04  655.52   205.7  657.42  208.74  659.02  211.78  660.31
  226.99  664.82  230.04  666.26  233.08  668.41  251.33  677.64  254.37   679.8
#Mann= 3 , 0 , 0
       0      .1       0   48.27      .1       0  189.57      .1       0
Bank Sta=48.27,189.57
XS Rating Curve= 0 ,0
Exp/Cntr=0.3,0.1

Type RM Length L Ch R = 1 ,7223.76 ,108.1,91.44,84.81
XS GIS Cut Line= 5
      623010.399    4316535.6329     623071.6505    4316504.0735
     623115.7271    4316488.3223     623151.7173    4316478.3444
     623251.6202    4316446.8577
#Sta/Elev= 30
       0  684.58    5.99  682.09    8.99  680.16   11.98  678.66   14.98  676.36
   32.95  658.58   35.95   657.4   41.94  654.13   44.94  652.87   47.93  652.38
   53.92  652.11   65.91  652.75   127.2  654.11  130.07  653.92  138.69   652.6
  147.31  652.16  153.06  652.09  168.02  652.25  171.01  652.36  174.01  652.75
  188.97  657.24  194.96   659.9  209.92  664.57  212.91  665.73  215.91  667.96
  224.88  671.42  233.86  674.44  239.85  677.12  254.81  681.66  257.81  682.38
#Mann= 3 , 0 , 0
       0      .1       0   44.94      .1       0  174.01      .1       0
Bank Sta=44.94,174.01
XS Rating Curve= 0 ,0
Exp/Cntr=0.3,0.1

Type RM Length L Ch R = 1 ,7132.32 ,92.14,91.44,75.08
XS GIS Cut Line= 5
      623119.525    4316623.4041     623183.5196    4316561.9316
     623200.6345    4316547.4497     623226.6814    4316530.5352
     623279.4015    4316466.7015
#Sta/Elev= 30
       0  683.98    9.18  673.81    15.3  667.76   18.36  665.14   24.48  661.38
   33.66  656.07   39.78  653.02   42.84  650.68    45.9  650.31   48.96  650.23
   58.14  650.73   85.68  652.75   88.74  652.81   94.34  652.46  102.75  651.16
  105.55  651.13  113.98  651.86   128.1  652.19  133.74  652.85  136.57  653.54
  139.39  654.76  148.35  658.09  154.48  659.05  163.68  661.85  191.27  671.37
  194.34  672.15  197.41  672.17  206.61  675.06  218.87  678.07     225  679.29
#Mann= 3 , 0 , 0
       0      .1       0   39.78      .1       0   128.1      .1       0
Bank Sta=39.78,128.1
XS Rating Curve= 0 ,0
Exp/Cntr=0.3,0.1

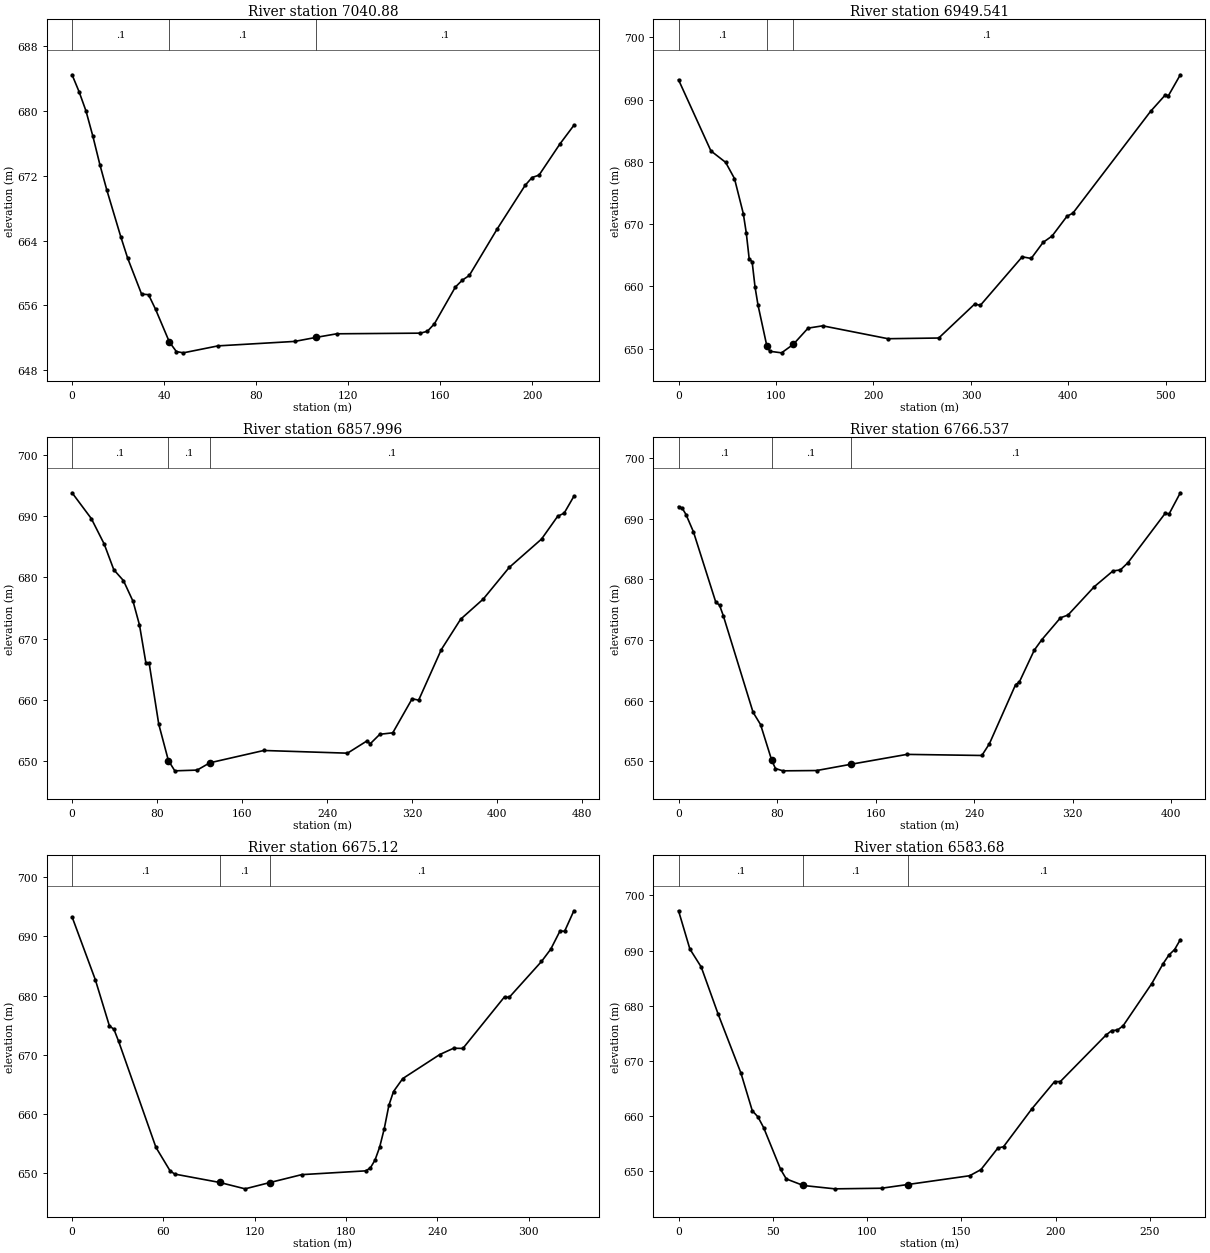
Type RM Length L Ch R = 1 ,7040.88 ,100.51,91.34,65.81
XS GIS Cut Line= 4
     623220.5148    4316671.7914     623259.6876    4316593.4463
     623279.5982    4316562.8144     623284.9578    4316469.0828
#Sta/Elev= 30
       0  684.46    3.02  682.39    6.04     680    9.06  676.85   12.08  673.37
    15.1  670.23   21.14  664.49   24.16  661.82    30.2  657.39   33.22  657.32
   36.25  655.53   42.29  651.47   45.31   650.3   48.33  650.14   63.43     651
   96.73  651.55  105.86  652.04  114.99  652.49  151.38  652.57  154.41  652.81
  157.44  653.73  166.53  658.26  169.55  659.11  172.58  659.69   184.7  665.43
  196.81   670.8  199.84  671.78  202.87  672.07  211.95  675.92  218.01  678.22
#Mann= 3 , 0 , 0
       0      .1       0   42.29      .1       0  105.86      .1       0
Bank Sta=42.29,105.86
XS Rating Curve= 0 ,0
Exp/Cntr=0.3,0.1

Type RM Length L Ch R = 1 ,6949.541,95.34,91.55,86.82
XS GIS Cut Line= 4
     623353.5568    4316731.0364     623328.9969    4316600.4248
     623321.8677    4316571.2996     623567.8697    4316319.6085
#Sta/Elev= 30
       0  693.18   33.23  681.76   48.33  679.92   57.39  677.32   66.45  671.69
   69.47  668.62   72.49  664.43   75.51  663.95   78.53  659.85   81.55  656.98
   90.61  650.42   93.63  649.57  105.72  649.32   117.8  650.69   132.9  653.29
  147.89  653.66  214.91  651.59  266.94   651.7  303.66  657.13  309.78  656.97
  352.63  664.75  361.81  664.48  374.05  667.07  383.23  668.08  398.54  671.26
  404.66  671.77  484.23   688.1  499.53  690.77  502.59  690.63  514.83  693.99
#Mann= 3 , 0 , 0
       0      .1       0   90.61      .1       0   117.8      .1       0
Bank Sta=90.61,117.8
XS Rating Curve= 0 ,0
Exp/Cntr=0.3,0.1

Type RM Length L Ch R = 1 ,6857.996,94.38,91.46,80.43
XS GIS Cut Line= 4
     623463.0945    4316712.2509     623425.9496     4316616.461
     623396.1346     4316522.428     623576.8655    4316320.6668
#Sta/Elev= 30
       0  693.78   18.13  689.57   30.22  685.43   39.28  681.23   48.35  679.46
   57.41  676.07   63.46  672.21    69.5  666.02   72.52  666.03   81.59  656.04
   90.65  650.12    96.7  648.44  117.69  648.56  129.64  649.75  180.46  651.76
  259.21  651.32  277.47  653.31  280.52  652.84  289.65   654.4  301.82  654.64
  320.08   660.2  326.17  659.96  347.47   668.2  365.73  673.17  387.04  676.46
  411.39   681.6  441.82  686.23  457.04  689.95  463.13  690.46  472.26   693.2
#Mann= 3 , 0 , 0
       0      .1       0   90.65      .1       0  129.64      .1       0
Bank Sta=90.65,129.64
XS Rating Curve= 0 ,0
Exp/Cntr=0.3,0.1

Type RM Length L Ch R = 1 ,6766.537,92.2,91.42,93.11
XS GIS Cut Line= 4
      623553.053    4316659.3341     623509.7002    4316576.1557
     623459.7284    4316495.7397     623587.4489     4316318.021
#Sta/Elev= 30
       0  691.97    3.03  691.69    6.05  690.66    12.1  687.81   30.26  676.21
   33.28  675.73   36.31  674.01   60.51  658.08   66.57  656.07   75.64  650.18
   78.67  648.82   84.72  648.44  112.12  648.49  139.61  649.51  185.42  651.15
  246.23  650.97  252.31  652.89  273.59  662.63  276.63  663.06  288.78  668.32
  294.86  670.03  310.06  673.65  316.14   674.1  337.42  678.76  352.62  681.36
   358.7  681.54  364.77  682.71  395.17  690.89  398.21  690.76  407.33  694.24
#Mann= 3 , 0 , 0
       0      .1       0   75.64      .1       0  139.61      .1       0
Bank Sta=75.64,139.61
XS Rating Curve= 0 ,0
Exp/Cntr=0.3,0.1

Type RM Length L Ch R = 1 ,6675.12 ,92.4,91.44,90.1
XS GIS Cut Line= 6
     623633.7511    4316614.3549      623593.978    4316538.4541
     623580.5398    4316516.9881     623571.4181    4316504.0115
     623547.9824    4316452.1335      623602.001     4316316.698
#Sta/Elev= 30
       0  693.31    15.3  682.67   24.48  674.92   27.54  674.28    30.6  672.26
   55.09  654.35   64.27  650.43   67.33  649.84   96.95  648.42  113.66  647.34
  129.87   648.4  150.85  649.74  192.92  650.38  195.95  650.88  198.99   652.2
  202.03  654.38  205.07  657.51  208.11  661.46  211.14  663.79  217.22  665.98
  241.52  670.04  250.63  671.11  256.71  671.07  284.05  679.79  287.09  679.69
  308.35  685.77  314.43  687.85   320.5  690.92  323.54  690.88  329.61  694.34
#Mann= 3 , 0 , 0
       0      .1       0   96.95      .1       0  129.87      .1       0
Bank Sta=96.95,129.87
XS Rating Curve= 0 ,0
Exp/Cntr=0.3,0.1

Type RM Length L Ch R = 1 ,6583.68 ,82.12,91.44,108.78
XS GIS Cut Line= 5
     623712.4639    4316555.3959      623658.175    4316468.6754
     623648.7783    4316455.5045     623614.8972    4316395.5141
     623616.5531     4316316.698
#Sta/Elev= 30
       0  697.22    6.02  690.27   12.04     687   21.06   678.4    33.1  667.74
   39.12   660.9   42.13  659.77   45.14  657.83   54.17  650.23   57.17   648.5
    66.2  647.31   82.94   646.7  107.71  646.81  121.49  647.48  154.44  649.08
  160.43  650.19  169.42  654.11  172.41  654.35  187.39  661.21  199.52  666.19
  202.55  666.19   226.8  674.64  229.84  675.46  232.87  675.54   235.9  676.34
  251.06  683.99  257.13  687.63  260.16  689.18  263.19  690.18  266.22  691.97
#Mann= 3 , 0 , 0
       0      .1       0    66.2      .1       0  121.49      .1       0
Bank Sta=66.2,121.49
XS Rating Curve= 0 ,0
Exp/Cntr=0.3,0.1

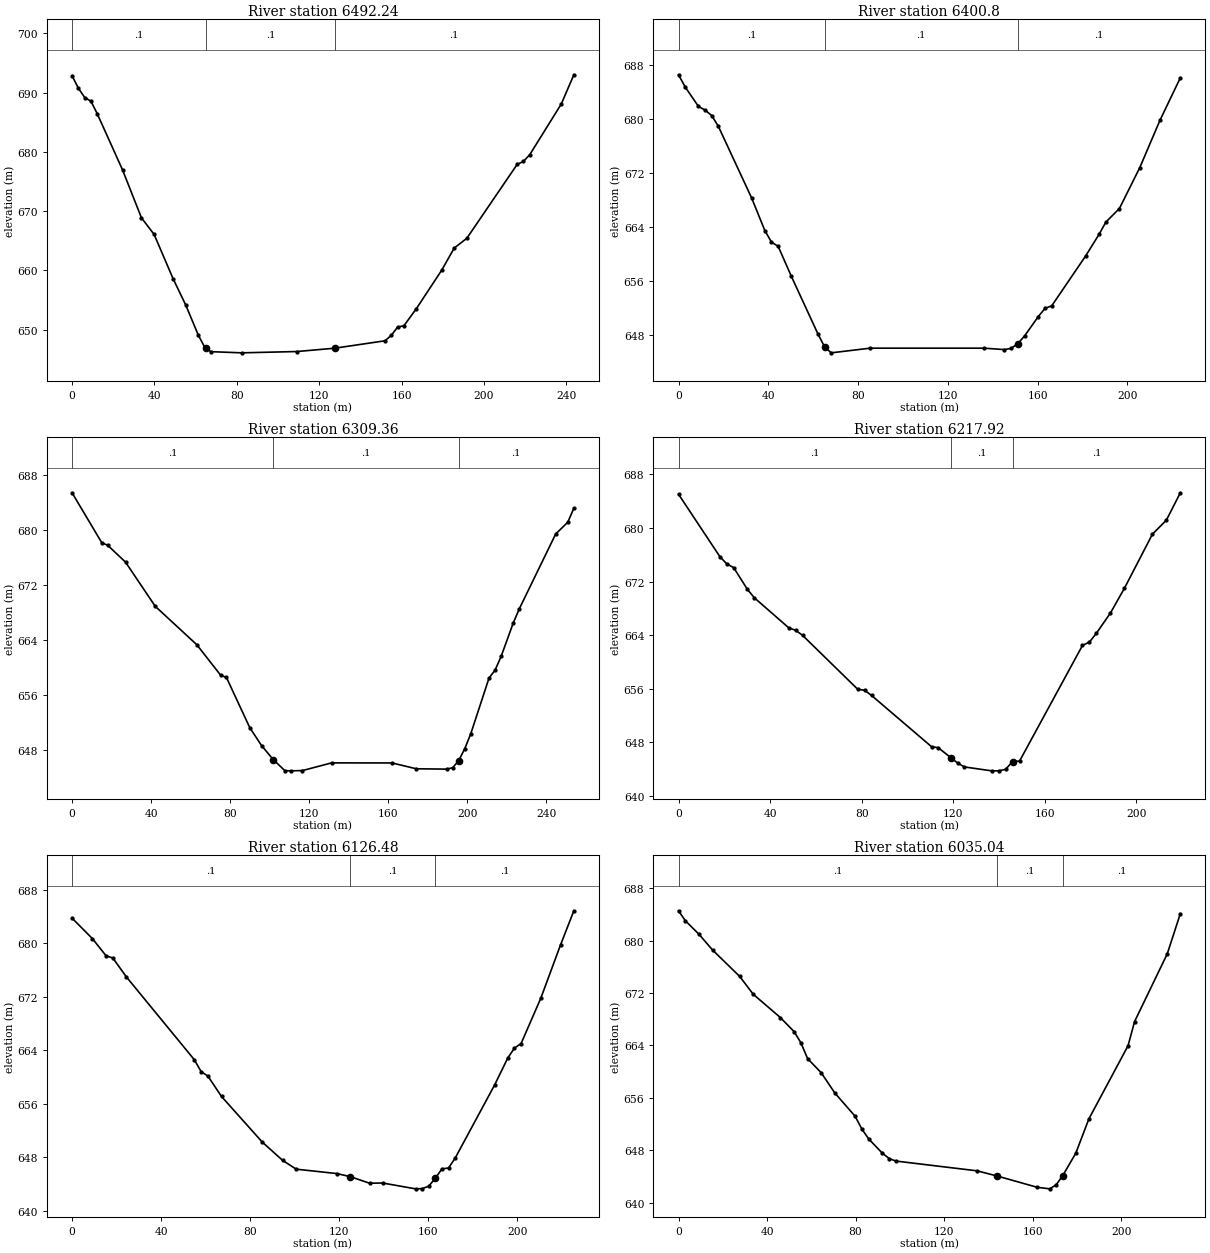
Type RM Length L Ch R = 1 ,6492.24 ,94.6,91.44,83.32
XS GIS Cut Line= 4
     623772.1675    4316517.4383      623744.142    4316449.4812
      623742.604    4316416.9538     623695.9283    4316287.5938
#Sta/Elev= 30
       0  692.82    3.06  690.73    6.13  689.16    9.19  688.52   12.25   686.4
    24.5  676.96   33.69  668.87   39.82  666.09   49.01  658.64   55.13  654.22
   61.26  649.12   64.32   647.1   65.17  646.89   67.38  646.32   82.39  646.12
  109.13  646.34  127.47   646.9  151.91  648.15  154.97  649.07  158.03  650.46
  161.08  650.68  167.19  653.59  179.42  660.04  185.53  663.78  191.64  665.43
  216.09  677.89  219.15  678.39   222.2  679.53  237.48  688.06   243.6  692.99
#Mann= 3 , 0 , 0
       0      .1       0   65.17      .1       0  127.47      .1       0
Bank Sta=65.17,127.47
XS Rating Curve= 0 ,0
Exp/Cntr=0.3,0.1

Type RM Length L Ch R = 1 ,6400.8  ,96.68,91.44,83.69
XS GIS Cut Line= 4
     623861.7893    4316478.4214      623831.308     4316414.274
     623822.3816    4316393.1596     623780.5951    4316270.3959
#Sta/Elev= 30
       0  686.55    2.96  684.74    8.88  681.87   11.84  681.32    14.8  680.51
   17.76  678.91   32.55  668.34   38.47  663.49   41.43  661.78   44.39  661.17
   50.31   656.7   62.14  648.19    65.1  646.27   68.06   645.4   85.35  646.09
  136.17  646.09  145.21  645.88  148.23  646.06  151.25  646.77  154.26  647.92
  160.29  650.75  163.31  651.98  166.32  652.36   181.4  659.72  187.44  662.95
  190.45  664.75  196.48  666.76  205.53  672.79  214.58  679.83  223.63   686.1
#Mann= 3 , 0 , 0
       0      .1       0    65.1      .1       0  151.25      .1       0
Bank Sta=65.1,151.25
XS Rating Curve= 0 ,0
Exp/Cntr=0.3,0.1

Type RM Length L Ch R = 1 ,6309.36 ,72.26,91.44,105.14
XS GIS Cut Line= 4
      623947.283    4316472.8025     623937.2569    4316398.3206
     623898.9314    4316353.2685     623828.2274    4316256.8082
#Sta/Elev= 30
       0  685.46   15.03  678.18   18.04   677.8   27.06  675.35   42.09  668.91
   63.13  663.31   75.15  658.88   78.11  658.54   89.94  651.21   95.86  648.62
  101.77  646.58  107.69  644.95  110.64  644.93  116.56  644.97  131.34  646.09
   161.9  646.08  174.17  645.23   189.5  645.18  192.57  645.38  195.63  646.41
   198.7  648.16  201.77  650.36  210.97  658.45  214.03   659.6   217.1  661.61
  223.23  666.48   226.3  668.55   244.7  679.45  250.83  681.17   253.9  683.21
#Mann= 3 , 0 , 0
       0      .1       0  101.77      .1       0  195.63      .1       0
Bank Sta=101.77,195.63
XS Rating Curve= 0 ,0
Exp/Cntr=0.3,0.1

Type RM Length L Ch R = 1 ,6217.92 ,95.92,91.44,91.83
XS GIS Cut Line= 4
     623964.4809    4316474.1254     623972.5935    4316381.1545
     623985.3444    4316346.0849     624002.2484    4316259.1817
#Sta/Elev= 30
       0  685.04   18.06  675.73   21.07  674.65   24.08  674.09    30.1  670.84
   33.12  669.59   48.17   665.1   51.18  664.74   54.19  663.98   78.27  655.94
   81.28  655.79   84.29  655.02  110.55  647.36  113.42  647.23  119.16  645.67
  122.03   644.9   124.9  644.35  136.75  643.77   139.8  643.77  142.85  643.99
   145.9  645.16  148.96  645.23  176.43  662.48  179.49  662.99  182.54  664.31
  188.64  667.32  194.75  671.01  206.96  679.07  213.07  681.17  219.17  685.26
#Mann= 3 , 0 , 0
       0      .1       0  119.16      .1       0   145.9      .1       0
Bank Sta=119.16,145.9
XS Rating Curve= 0 ,0
Exp/Cntr=0.3,0.1

Type RM Length L Ch R = 1 ,6126.48 ,65.93,91.44,106.74
XS GIS Cut Line= 5
     623996.4956    4316490.8604     624068.3795    4316395.9513
     624072.4011    4316378.8063     624073.6943    4316367.1225
     624090.4842    4316291.8786
#Sta/Elev= 30
       0  683.76    9.16  680.69   15.26  678.14   18.32   677.8   24.42  674.97
   54.95  662.59      58  660.82   61.06  660.14   67.16   657.1   85.48  650.28
   94.64  647.54  100.74  646.23  119.06  645.57  124.93  645.12  133.73  644.13
  139.61  644.16  154.35  643.29  157.32  643.32  160.29  643.68  163.25  644.86
  166.22  646.28  169.18   646.4  172.15  647.87  189.94  658.84  195.87  662.89
  198.83  664.33   201.8  665.01  210.69  671.81  219.59  679.81  225.52  684.86
#Mann= 3 , 0 , 0
       0      .1       0  124.93      .1       0  163.25      .1       0
Bank Sta=124.93,163.25
XS Rating Curve= 0 ,0
Exp/Cntr=0.3,0.1

Type RM Length L Ch R = 1 ,6035.04 ,79.16,91.44,91.08
XS GIS Cut Line= 5
     624002.8456    4316505.1479     624102.3101    4316438.5074
      624137.503    4316420.7912     624151.3868    4316416.7212
     624203.0371    4316404.1449
#Sta/Elev= 30
       0  684.55    3.07  683.03    9.21  680.98   15.35  678.57   27.63  674.53
   33.77   671.8   46.05  668.24   52.19  666.11   55.26  664.42   58.33  661.98
   64.47  659.83   70.61  656.74   79.82  653.17   82.89   651.2   85.96  649.71
    92.1  647.54   95.17  646.73   98.24  646.34  134.88  644.85  143.97  644.06
  162.02  642.34  167.81   642.1   170.7  642.74  173.59  644.11   179.5  647.53
  185.41  652.77  203.13  663.95  206.08  667.64  220.85  677.98  226.75  684.11
#Mann= 3 , 0 , 0
       0      .1       0  143.97      .1       0  173.59      .1       0
Bank Sta=143.97,173.59
XS Rating Curve= 0 ,0
Exp/Cntr=0.3,0.1

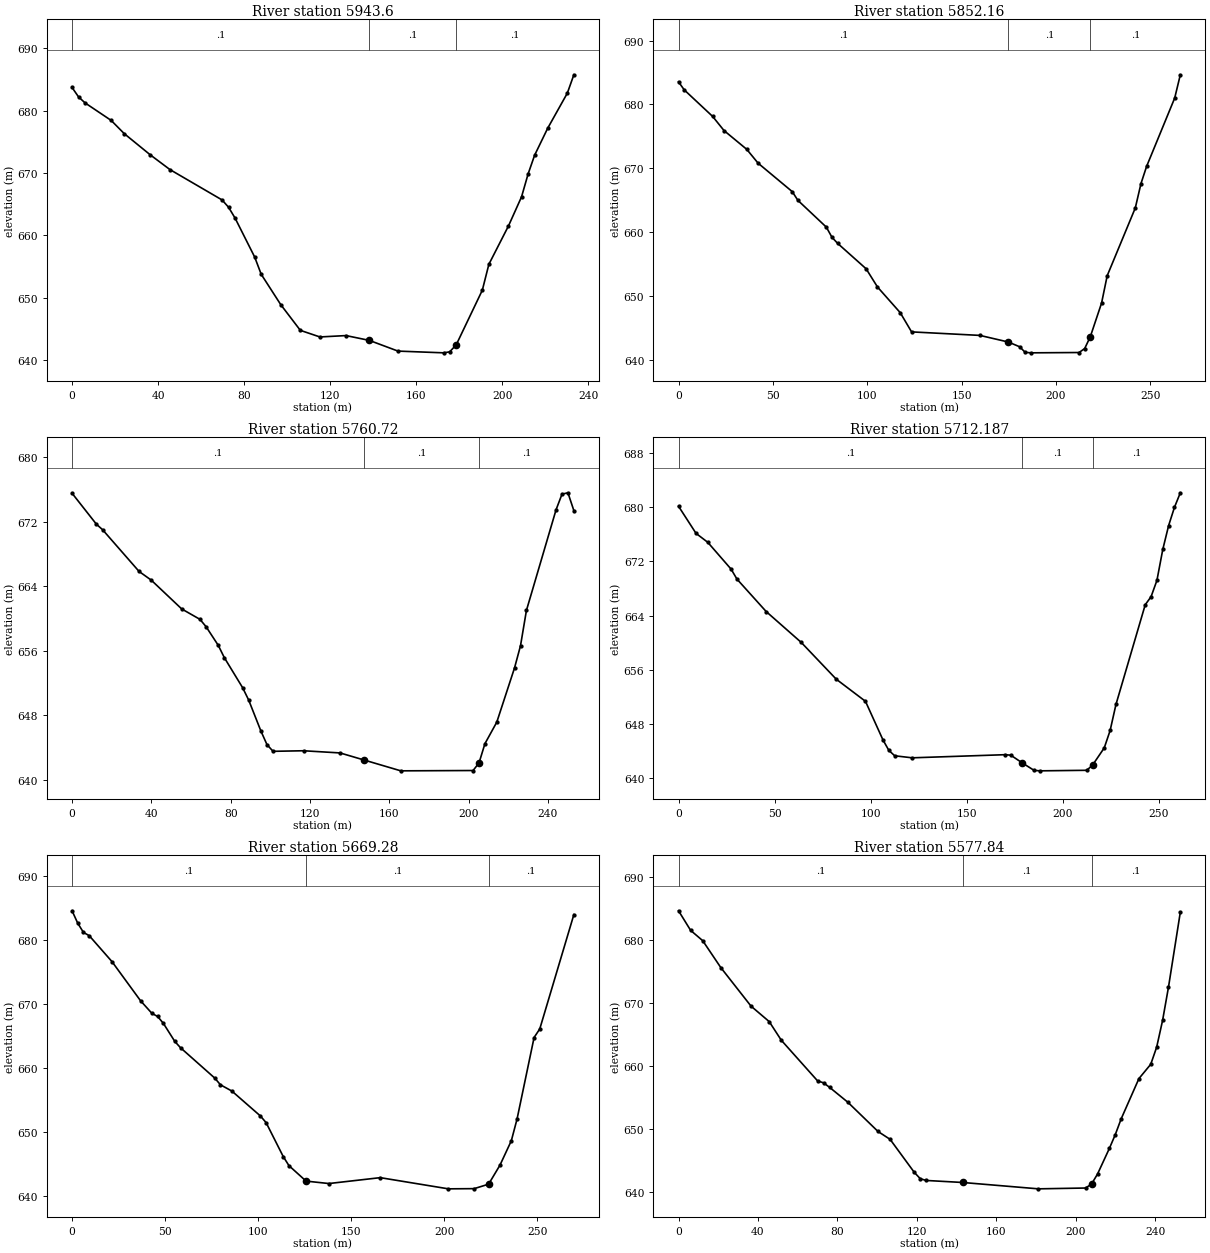
Type RM Length L Ch R = 1 ,5943.6  ,85.36,91.44,97.75
XS GIS Cut Line= 6
     624001.2581    4316524.9917     624127.7102    4316509.4159
     624149.1415    4316506.2409      624158.989    4316508.2739
     624174.6902    4316503.2494     624231.3568    4316491.9986
#Sta/Elev= 30
       0  683.72    3.03   682.2    6.07  681.24    18.2  678.43   24.27  676.31
    36.4   672.9    45.5  670.55   69.77  665.67    72.8  664.49   75.84  662.74
   84.94   656.5   87.97  653.74   97.07  648.86  106.17  644.74  115.27  643.68
  127.41   643.9  138.24  643.13  151.59  641.41  172.87  641.13  175.61  641.29
  178.65   642.4  190.82  651.19  193.86  655.34  202.98   661.5  209.06  666.17
   212.1  669.83  215.14  672.85  221.22  677.18  230.35  682.81  233.39  685.76
#Mann= 3 , 0 , 0
       0      .1       0  138.24      .1       0  178.65      .1       0
Bank Sta=138.24,178.65
XS Rating Curve= 0 ,0
Exp/Cntr=0.3,0.1

Type RM Length L Ch R = 1 ,5852.16 ,77.86,91.44,98.14
XS GIS Cut Line= 6
     623976.4136    4316574.5306     624119.5853     4316594.548
     624152.8033    4316593.0367     624172.9024    4316597.0048
     624186.6721    4316599.0451      624240.328    4316599.6805
#Sta/Elev= 30
       0  683.54    3.01  682.29   18.07  678.13   24.09  675.92   36.14  672.98
   42.16  670.81   60.24  666.36   63.25  664.99   78.31   660.8   81.32   659.2
   84.33  658.25   99.39  654.28  105.41  651.43  117.46  647.41  123.48   644.4
  159.68  643.85  174.79  642.81  180.74  642.07  183.67   641.2   186.6  641.12
  212.22  641.17   215.2  641.79  218.19  643.65  224.15  648.91  227.13  653.19
  242.03  663.81  245.02  667.61     248   670.3   262.9  681.01  265.88  684.65
#Mann= 3 , 0 , 0
       0      .1       0  174.79      .1       0  218.19      .1       0
Bank Sta=174.79,218.19
XS Rating Curve= 0 ,0
Exp/Cntr=0.3,0.1

Type RM Length L Ch R = 1 ,5760.72 ,36.29,48.53,55.61
XS GIS Cut Line= 4
     623985.0126    4316595.0358     624121.7801    4316671.4756
     624160.3936    4316689.4623      624206.698    4316716.9008
#Sta/Elev= 30
       0  675.53   12.29  671.69   15.36  671.02   33.79  665.84   39.94  664.76
    55.3  661.19   64.51   659.9   67.59  658.99   73.73  656.68    76.8  655.15
   86.02  651.43   89.09  649.89   95.24  646.06   98.31  644.37  101.38  643.54
  116.74  643.61  135.17  643.34  147.46  642.45  165.81  641.12  202.27  641.16
  205.26   642.1  208.25  644.49  214.23  647.16   223.2   653.9  226.19  656.63
  229.18  661.01  244.13  673.49  247.12  675.42  250.11  675.59   253.1  673.38
#Mann= 3 , 0 , 0
       0      .1       0  147.46      .1       0  205.26      .1       0
Bank Sta=147.46,205.26
XS Rating Curve= 0 ,0
Exp/Cntr=0.3,0.1

Type RM Length L Ch R = 1 ,5712.187,32.52,42.91,51.8
XS GIS Cut Line= 4
      623968.607    4316596.0743     624085.0239    4316689.2078
      624104.074    4316708.2578     624164.3991     4316768.583
#Sta/Elev= 30
       0  680.13    9.13  676.13   15.21  674.82   27.38  670.86   30.43  669.39
   45.64  664.61   63.89  660.06   82.15  654.63   97.36  651.37  106.49  645.67
  109.53  644.14  112.58  643.34   121.7  643.04  170.04   643.5  173.03  643.43
  179.07  642.28  185.17  641.19  188.21  641.12  212.59   641.2  215.64  641.97
  221.73  644.51  224.78  647.07  227.82  650.91  243.06  665.61  246.11   666.8
  249.15   669.2   252.2  673.76  255.25  677.29  258.29  679.98  261.34  682.12
#Mann= 3 , 0 , 0
       0      .1       0  179.07      .1       0  215.64      .1       0
Bank Sta=179.07,215.64
XS Rating Curve= 0 ,0
Exp/Cntr=0.3,0.1

Type RM Length L Ch R = 1 ,5669.28 ,93.83,91.44,87.32
XS GIS Cut Line= 5
     623951.3912    4316599.6495     624082.5847    4316732.9659
     624089.2443    4316756.2355     624092.5959    4316765.1141
     624105.0042    4316812.3639
#Sta/Elev= 30
       0  684.59    3.07  682.63    6.13   681.2     9.2   680.7   21.46  676.63
    36.8  670.51   42.93  668.53   45.99  668.05   49.06  666.97   55.19  664.15
   58.26  663.16   76.66  658.41   79.72  657.36   85.86  656.38  101.19  652.48
  104.25  651.44  113.45  646.13  116.52  644.71  125.72  642.29  137.98  641.91
  165.58  642.83  202.17  641.08  216.02  641.11  223.79  641.81   229.9  644.79
     236  648.61  239.06  651.99  248.22  664.76  251.27   666.1  269.59  683.99
#Mann= 3 , 0 , 0
       0      .1       0  125.72      .1       0  223.79      .1       0
Bank Sta=125.72,223.79
XS Rating Curve= 0 ,0
Exp/Cntr=0.3,0.1

Type RM Length L Ch R = 1 ,5577.84 ,79.63,91.44,97.81
XS GIS Cut Line= 5
     623918.3182     4316632.061     623998.1317    4316779.2612
     624011.7338    4316796.6173     624014.3426    4316805.8711
     624047.4589     4316848.037
#Sta/Elev= 30
       0  684.62    6.09  681.51   12.18  679.87   21.31  675.59   36.53  669.47
   45.67  667.02   51.76  664.06   70.02  657.61   73.07  657.29   76.11  656.57
   85.25  654.22  100.47  649.57  106.56  648.32  118.73  643.08  121.78  642.06
  124.82  641.79  143.09  641.47  181.23  640.46  205.07  640.59  208.05  641.24
  211.03  642.81  216.98  646.87  219.96  649.06  222.94  651.58  231.88  657.97
  237.83  660.24  240.81  662.96  243.79   667.2  246.77   672.5  252.73  684.41
#Mann= 3 , 0 , 0
       0      .1       0  143.09      .1       0  208.05      .1       0
Bank Sta=143.09,208.05
XS Rating Curve= 0 ,0
Exp/Cntr=0.3,0.1