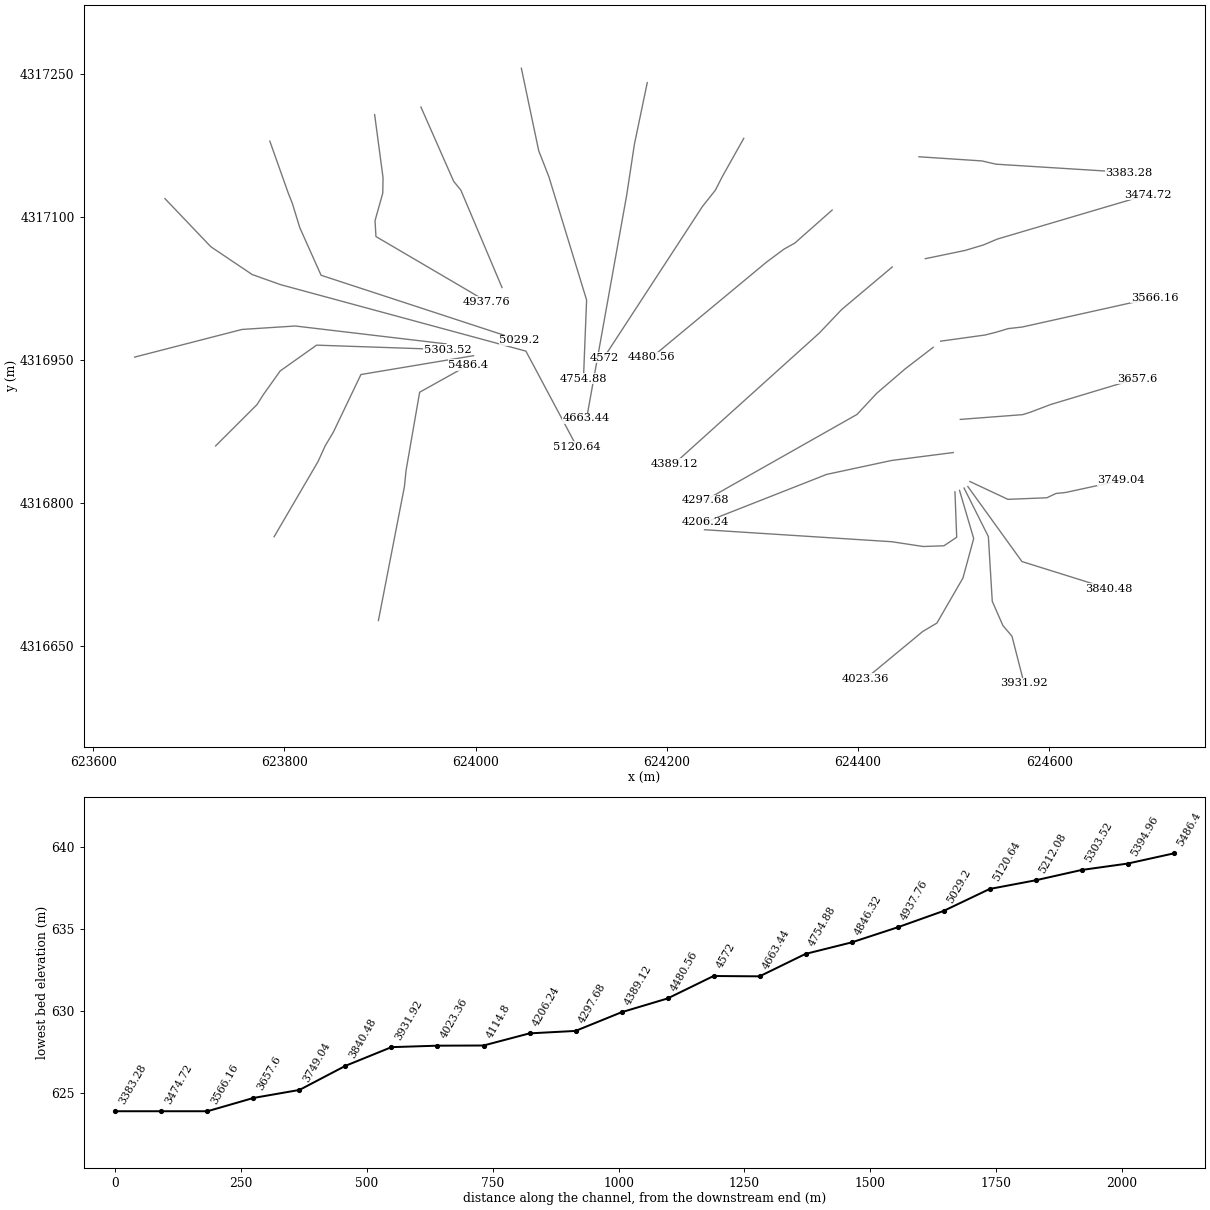
HEC-RAS study RedCreek.prj: RedCreek

--- RedCreek.g01 (geometry) --- (continued)

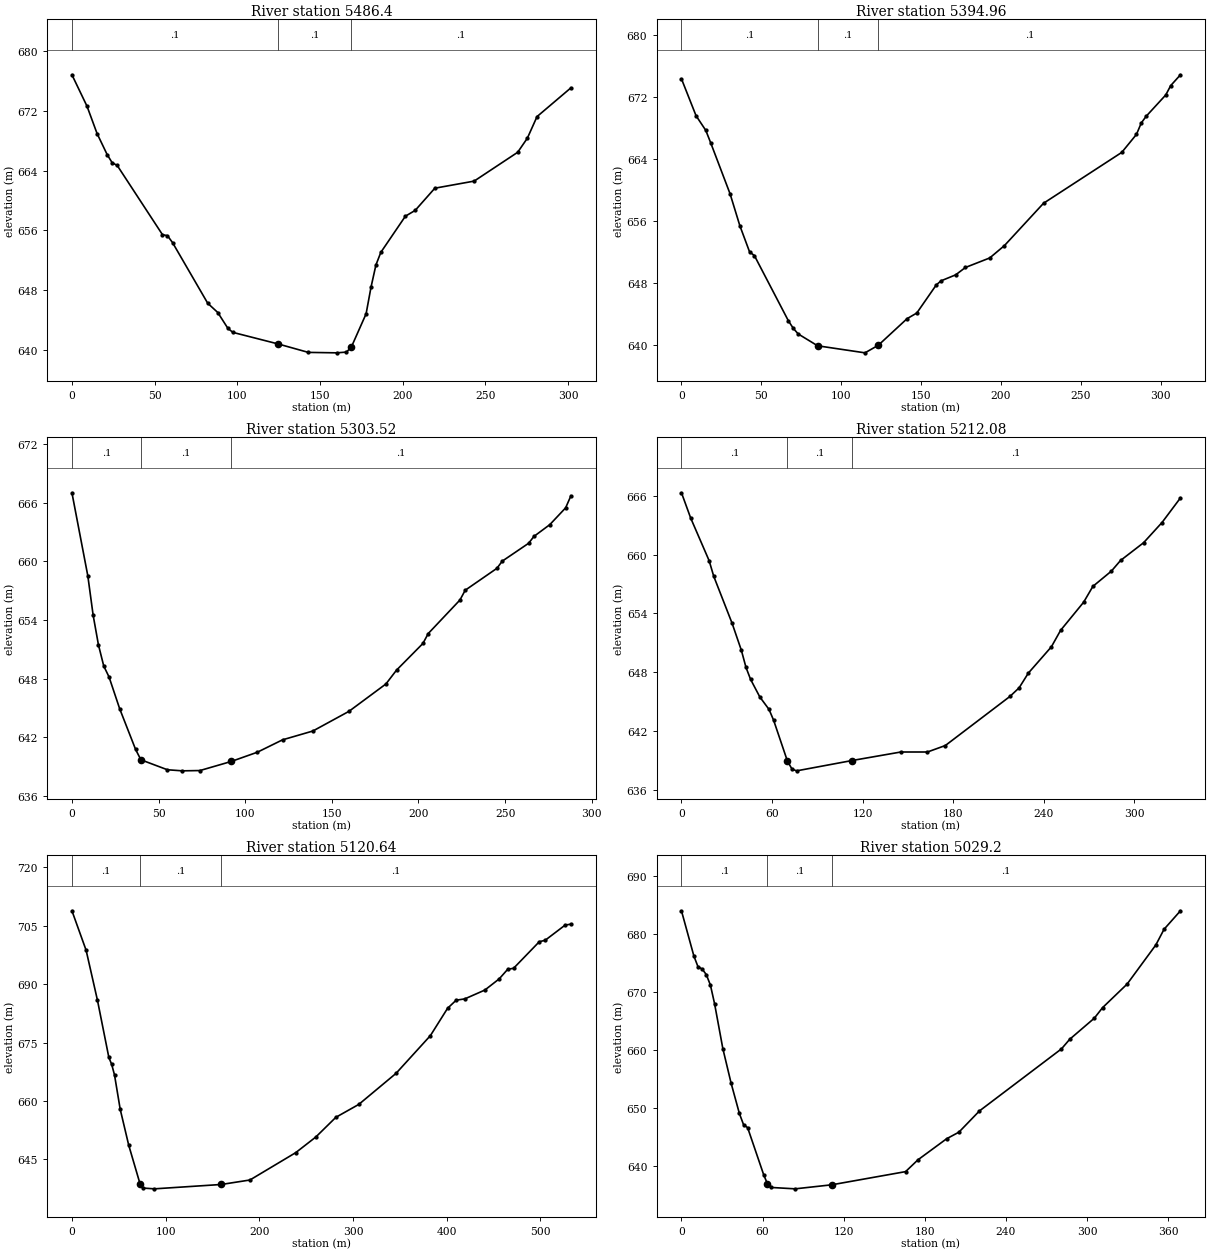
Type RM Length L Ch R = 1 ,5486.4  ,97.34,91.44,83.03
XS GIS Cut Line= 5
     623898.4347    4316676.9345     623925.6204    4316817.2362
     623927.3458    4316834.2745     623941.5427     4316916.182
     623992.6266    4316944.6933
#Sta/Elev= 30
       0  676.84    9.12  672.63    15.2  668.97   21.28  666.16   24.33  665.06
   27.37   664.7   54.73  655.43   57.77  655.29   60.81  654.37    82.1  646.24
   88.18     645   94.26  642.89    97.3  642.34  124.67  640.79  142.91  639.66
  160.04   639.6  165.97   639.7  168.94  640.38  177.85  644.83  180.82   648.4
  183.79  651.37  186.76  653.06   201.6   657.9  207.54  658.68  219.41  661.65
  243.17   662.6  269.49  666.46  275.34  668.35  281.19  671.24  301.67  675.09
#Mann= 3 , 0 , 0
       0      .1       0  124.67      .1       0  168.94      .1       0
Bank Sta=124.67,168.94
XS Rating Curve= 0 ,0
Exp/Cntr=0.3,0.1

Type RM Length L Ch R = 1 ,5394.96 ,96.68,91.44,82.82
XS GIS Cut Line= 6
     623789.3083    4316764.6907     623835.3191    4316843.5745
     623842.7328    4316859.9763     623851.2786     4316874.317
     623880.1336    4316934.7373     623997.9182    4316954.4829
#Sta/Elev= 30
       0  674.35    9.13  669.59   15.22   667.7   18.26  666.11   30.44   659.5
   36.53   655.4   42.62  652.02   45.66  651.53   66.97   643.1   70.01  642.14
   73.06  641.42   85.23  639.89  114.89  638.98  123.23  639.96  141.23  643.39
  147.32  644.12  159.49  647.74  162.54  648.28  171.67  649.05  177.75     650
  192.97  651.23  202.16  652.82  226.66  658.29  275.65  664.86  284.84  667.18
   287.9  668.67  290.96  669.53  303.21  672.28  306.28  673.48   312.4  674.88
#Mann= 3 , 0 , 0
       0      .1       0   85.23      .1       0  123.23      .1       0
Bank Sta=85.23,123.23
XS Rating Curve= 0 ,0
Exp/Cntr=0.3,0.1

Type RM Length L Ch R = 1 ,5303.52 ,99.05,91.44,58.09
XS GIS Cut Line= 6
     623728.1494    4316859.9198     623771.4446     4316903.215
     623778.2324    4316913.8897     623795.6949     4316938.496
     623833.7541    4316965.5245     623970.9307     4316960.833
#Sta/Elev= 30
       0  667.01    9.18  658.51   12.25  654.49   15.31  651.46   18.37   649.3
   21.43  648.18   27.55  644.94   36.74  640.78    39.8  639.72   55.11   638.7
   63.76  638.59   73.88  638.62   91.98  639.55  106.97  640.49  121.56  641.76
  139.06  642.66  159.88  644.67  181.23  647.47  187.33  648.88  202.58  651.61
  205.63  652.62  223.94  656.05  226.99  657.05  245.29  659.29  248.34  660.02
  263.59  661.85  266.64  662.55  275.79  663.75  284.94  665.47  287.99   666.7
#Mann= 3 , 0 , 0
       0      .1       0    39.8      .1       0   91.98      .1       0
Bank Sta=39.8,91.98
XS Rating Curve= 0 ,0
Exp/Cntr=0.3,0.1

Type RM Length L Ch R = 1 ,5212.08 ,118.8,91.44,53.44
XS GIS Cut Line= 4
     623643.4679    4316953.0017     623755.8124     4316981.994
     623811.4707    4316985.5919      623969.209    4316966.8477
#Sta/Elev= 30
       0   666.3    6.11  663.72   18.32  659.38   21.37  657.79   33.59  652.98
   39.69  650.24   42.75   648.5    45.8  647.28   51.91  645.49   58.01  644.22
   61.07  643.11   70.23  638.94   73.28  638.13   76.33  637.96  112.97  639.01
  145.38  639.88  162.99  639.88  174.85  640.54  217.62  645.54  223.73  646.42
  229.84  647.92  245.11   650.6  251.22  652.28   266.5  655.15  272.61  656.76
  284.83  658.31  290.94   659.4  306.21  661.21  318.43  663.27  330.65  665.78
#Mann= 3 , 0 , 0
       0      .1       0   70.23      .1       0  112.97      .1       0
Bank Sta=70.23,112.97
XS Rating Curve= 0 ,0
Exp/Cntr=0.3,0.1

Type RM Length L Ch R = 1 ,5120.64 ,102.72,91.44,58.31
XS GIS Cut Line= 6
     623675.1372    4317119.1289     623723.1744    4317068.6464
     623766.3912    4317039.5411     623796.0367    4317028.9395
     624052.6871    4316959.2455     624105.8685    4316859.2328
#Sta/Elev= 30
       0  708.84   15.15  698.69   27.27  685.83   39.39  671.19   42.42  669.39
   45.45  666.67   51.51  657.87    60.6  648.64   72.75  638.66   75.82  637.63
   88.08  637.43  159.39  638.55  189.96   639.7  238.86  646.73  260.26  650.74
  281.66   655.8  306.11  659.11  345.85  667.08  382.54  676.78  400.88   683.8
  410.05  685.88  419.22  686.21  440.65  688.48  455.95  691.35  465.14  693.84
  471.26  694.06  498.81  700.91  504.94  701.25  526.37  705.17  532.49   705.4
#Mann= 3 , 0 , 0
       0      .1       0   72.75      .1       0  159.39      .1       0
Bank Sta=72.75,159.39
XS Rating Curve= 0 ,0
Exp/Cntr=0.3,0.1

Type RM Length L Ch R = 1 ,5029.2  ,102.19,91.44,74.66
XS GIS Cut Line= 6
     623784.8515    4317179.3521     623804.2399     4317124.563
     623808.2765    4317114.4325     623816.2512    4317088.5148
     623838.4627    4317038.7688     624046.0725    4316970.6226
#Sta/Elev= 30
       0  684.04    9.18  676.25   12.24  674.39   15.29  674.02   18.35  673.05
   21.41  671.24   24.47  668.04   30.59  660.29   36.71  654.32   42.82   649.1
   45.88  647.18   48.94  646.64   60.84   638.5   63.57  636.97    66.3  636.33
   84.09  636.09  111.27  636.79  165.79  639.06   174.9  641.09  196.14  644.73
  205.25  645.87  220.42  649.53  281.12  660.24  287.19  661.89   305.4  665.53
  311.47  667.34  329.68  671.42  350.92  678.17  356.99  680.87  369.13  684.06
#Mann= 3 , 0 , 0
       0      .1       0   63.57      .1       0  111.27      .1       0
Bank Sta=63.57,111.27
XS Rating Curve= 0 ,0
Exp/Cntr=0.3,0.1

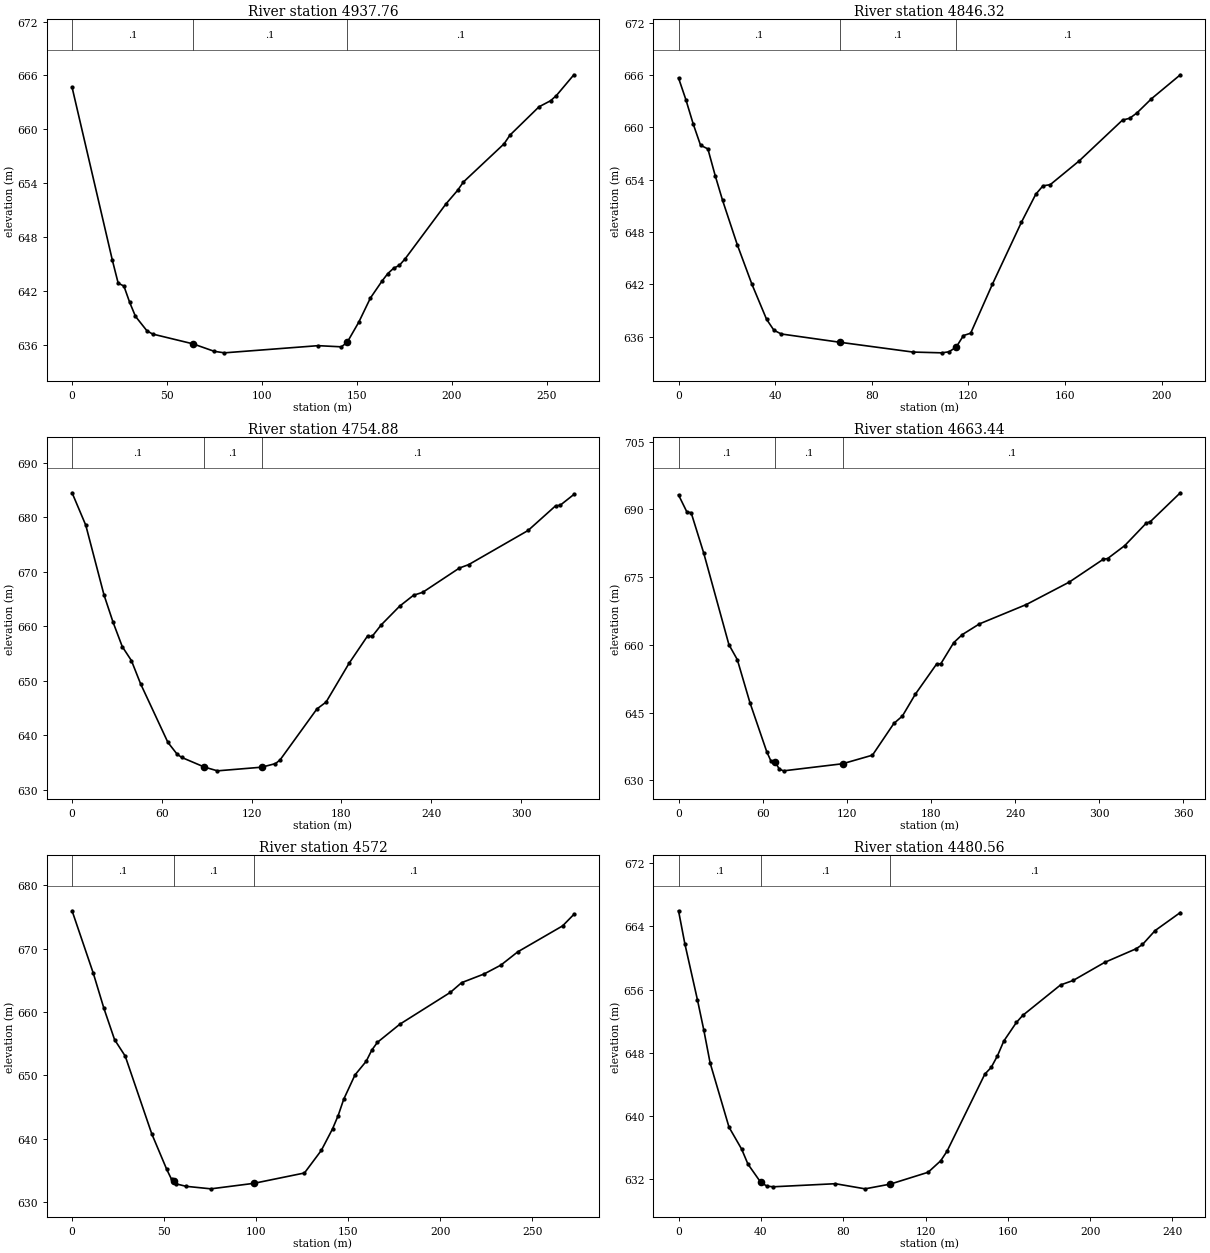
Type RM Length L Ch R = 1 ,4937.76 ,70.72,91.44,109.78
XS GIS Cut Line= 6
      623894.466    4317207.1605     623903.2681     4317141.004
     623902.9692    4317124.8323      623894.877    4317096.0036
     623895.8486    4317079.3546     624011.9412    4317011.1039
#Sta/Elev= 30
       0  664.69   21.24  645.39   24.27  642.86    27.3  642.53   30.34  640.71
   33.37  639.16   39.44  637.54   42.47  637.18   63.71  636.09   74.83  635.26
   80.22  635.09  129.53  635.89  141.78  635.76  144.84  636.26  150.96  638.51
  157.08   641.2   163.2  643.09  166.26  643.93  169.32  644.52  172.38  644.85
  175.44  645.59  196.87  651.69  202.99   653.2  206.05  654.13  227.48  658.39
  230.54  659.35  245.84  662.51  251.96  663.19  255.02  663.77   264.2  666.08
#Mann= 3 , 0 , 0
       0      .1       0   63.71      .1       0  144.84      .1       0
Bank Sta=63.71,144.84
XS Rating Curve= 0 ,0
Exp/Cntr=0.3,0.1

Type RM Length L Ch R = 1 ,4846.32 ,97.45,91.44,90.33
XS GIS Cut Line= 4
     623942.8848     4317215.098     623977.1311    4317137.2447
     623984.6506    4317127.9475     624027.6964     4317025.913
#Sta/Elev= 30
       0  665.65    3.04  663.17    6.08  660.38    9.11  657.95   12.15  657.53
   15.19  654.46   18.23  651.64    24.3  646.57   30.38  642.03   36.45  638.01
   39.49  636.76   42.53  636.33   66.83  635.38   97.01  634.26  108.98  634.17
  111.98  634.29  114.97  634.83  117.96  636.15  120.95  636.42  129.93  642.02
  141.91   649.1  147.89  652.33  150.88   653.3  153.88  653.43  165.85  656.15
  183.81  660.83   186.8  661.04  189.79  661.65  195.78  663.27  207.75  666.02
#Mann= 3 , 0 , 0
       0      .1       0   66.83      .1       0  114.97      .1       0
Bank Sta=66.83,114.97
XS Rating Curve= 0 ,0
Exp/Cntr=0.3,0.1

Type RM Length L Ch R = 1 ,4754.88 ,105.39,91.44,82.56
XS GIS Cut Line= 5
     624047.9269    4317255.7505     624066.0957    4317169.2097
     624076.6649    4317142.1649     624116.1688    4317012.8145
     624112.8799    4316930.3397
#Sta/Elev= 30
       0  684.53    9.15  678.58   21.34  665.77   27.44  660.72   33.54  656.28
   39.64  653.72   45.74  649.48   64.03  638.69   70.13  636.55   73.18  635.94
   88.43  634.16   97.14  633.47  126.69  634.14  135.91   634.8  138.98  635.48
  163.57  644.83  169.72   646.1  185.09  653.23  197.38  658.22  200.46  658.15
  206.61  660.29   218.9  663.72  228.12  665.71  234.27  666.25  258.83  670.72
  264.94  671.33  304.68  677.61  323.02  682.13  326.08  682.23  335.25  684.22
#Mann= 3 , 0 , 0
       0      .1       0   88.43      .1       0  126.69      .1       0
Bank Sta=88.43,126.69
XS Rating Curve= 0 ,0
Exp/Cntr=0.3,0.1

Type RM Length L Ch R = 1 ,4663.44 ,99.73,91.44,82.31
XS GIS Cut Line= 4
     624179.6286    4317240.7143      624166.196    4317176.2408
     624158.0896    4317122.7383     624116.1872    4316888.6677
#Sta/Elev= 30
       0  693.19    5.99   689.4    8.98  689.27   17.96  680.32   35.92  660.04
   41.91  656.72   50.89  647.22   62.86  636.36   65.86  634.28   68.86  634.07
   71.87  632.47   74.88   632.1  116.96  633.67  138.26  635.57  153.51  642.59
   159.6  644.23  168.75  649.03  183.99  655.75  187.04  655.83  196.19  660.48
  202.28  662.26  214.48  664.63  248.01  668.93   278.5  673.88  302.89  678.96
  305.94  679.11  318.13  681.97  333.37  686.92  336.42  687.29  357.76  693.67
#Mann= 3 , 0 , 0
       0      .1       0   68.86      .1       0  116.96      .1       0
Bank Sta=68.86,116.96
XS Rating Curve= 0 ,0
Exp/Cntr=0.3,0.1

Type RM Length L Ch R = 1 ,4572    ,108.2,91.44,87.68
XS GIS Cut Line= 5
     624280.5501    4317182.2869     624257.9758    4317141.9907
     624250.8967    4317128.0131     624237.4303    4317111.0029
     624134.3112    4316952.5647
#Sta/Elev= 30
       0  675.98   11.55  666.11   17.32  660.57   23.09  655.65   28.87  653.06
    43.3  640.79   51.41   635.2   54.02  633.63   55.17  633.31   56.63   632.9
   61.86  632.52   75.42  632.12    98.8  632.99  126.24  634.62  135.39  638.18
  141.48  641.57  144.53  643.66  147.58  646.26  153.68  650.08  159.78  652.24
  162.83  654.01  165.88  655.23  178.07  658.09  205.51  663.11  211.61  664.64
  223.81  666.01  232.95  667.41   242.1   669.5  266.49   673.6  272.59  675.41
#Mann= 3 , 0 , 0
       0      .1       0   55.17      .1       0    98.8      .1       0
Bank Sta=55.17,98.8
XS Rating Curve= 0 ,0
Exp/Cntr=0.3,0.1

Type RM Length L Ch R = 1 ,4480.56 ,85.49,91.44,93
XS GIS Cut Line= 5
     624372.9659    4317107.0817     624333.9508    4317072.5053
      624322.867    4317066.3248      624304.597    4317052.7578
     624184.4695    4316952.8771
#Sta/Elev= 30
       0  665.98    3.07   661.8     9.2  654.68   12.27  650.88   15.33  646.72
   24.53  638.56   30.67  635.78   33.73  633.88   39.87   631.6   42.93  631.09
      46  631.01    76.2   631.4   90.64  630.75  102.89  631.35  121.27  632.85
   127.4  634.31  130.46  635.52  148.84  645.29  151.91  646.13  154.97  647.61
  158.03  649.47  164.16  651.83  167.22  652.72   185.6  656.58  191.73  657.15
  207.05  659.44  222.36  661.17  225.43  661.71  231.55  663.47  243.81  665.76
#Mann= 3 , 0 , 0
       0      .1       0   39.87      .1       0  102.89      .1       0
Bank Sta=39.87,102.89
XS Rating Curve= 0 ,0
Exp/Cntr=0.3,0.1

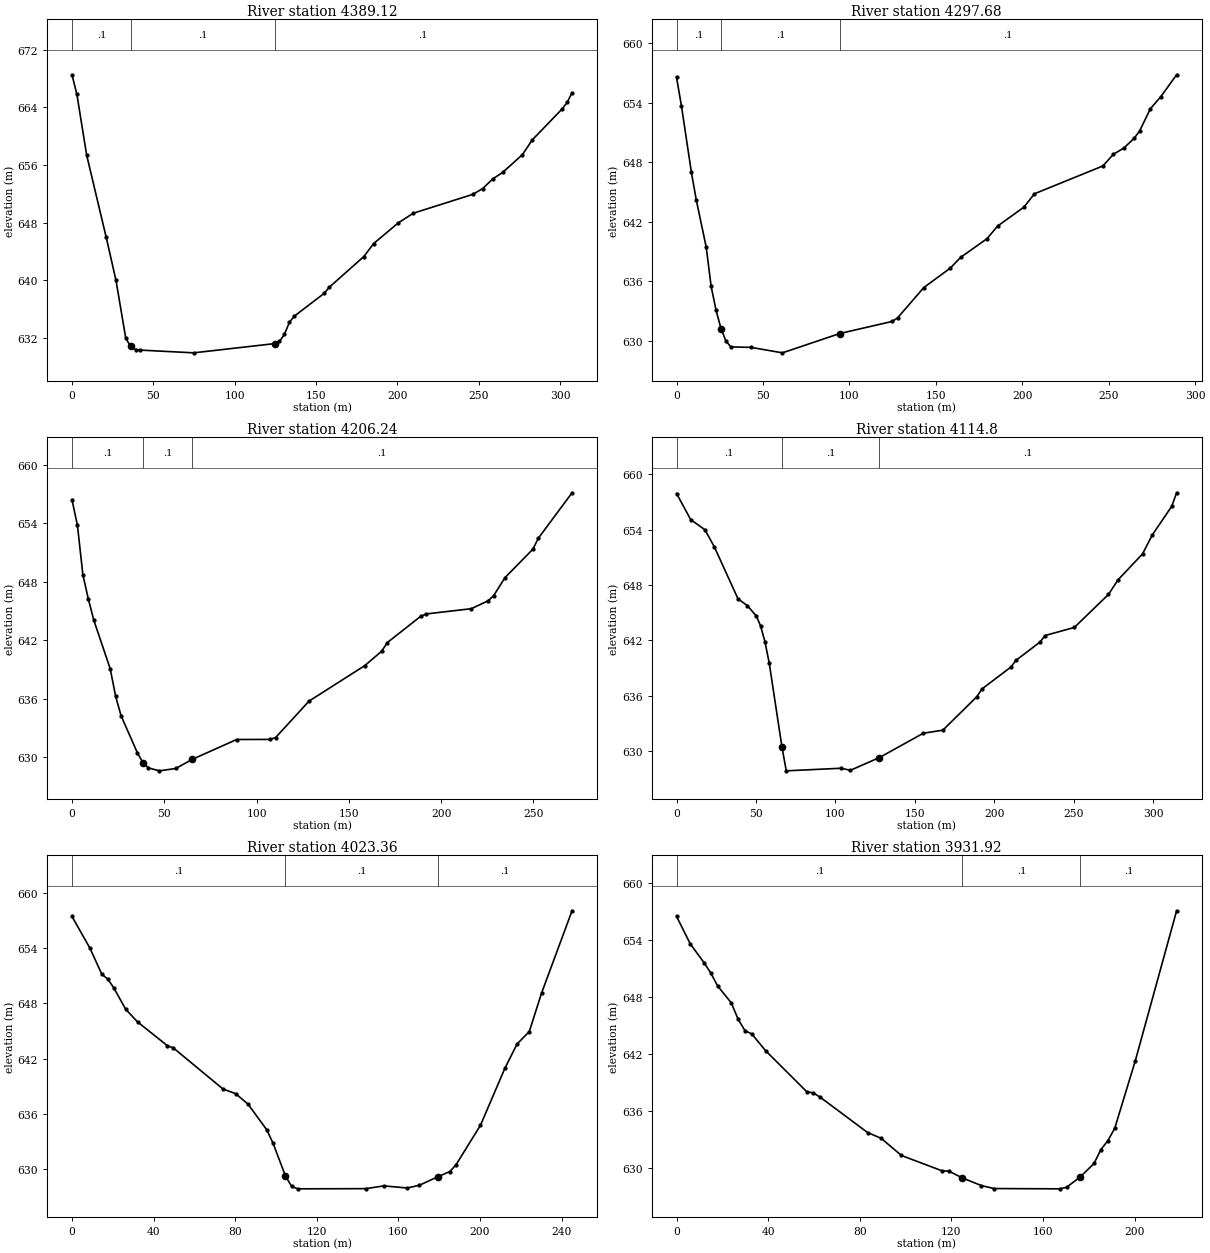
Type RM Length L Ch R = 1 ,4389.12 ,92.5,91.44,88.42
XS GIS Cut Line= 4
     624435.8501    4317047.4641     624382.9996    4317002.9124
      624359.579    4316978.2259     624208.0419    4316841.4042
#Sta/Elev= 30
       0  668.54    3.01  665.83    9.02  657.38   21.04  645.95   27.05  639.97
   33.06  631.93   36.06   630.8   39.07  630.36   42.08  630.29   74.79  629.91
  124.48  631.19  127.53  631.49  130.58  632.49  133.62  634.15  136.67  635.01
  154.96  638.17     158     639  179.33  643.28  185.43   645.1  200.66  647.99
  209.81  649.31  246.37  651.93  252.47  652.74  258.56  654.07  264.66  654.97
  276.85  657.45  282.94  659.51  301.22  663.79  304.27  664.69  307.32  666.04
#Mann= 3 , 0 , 0
       0      .1       0   36.06      .1       0  124.48      .1       0
Bank Sta=36.06,124.48
XS Rating Curve= 0 ,0
Exp/Cntr=0.3,0.1

Type RM Length L Ch R = 1 ,4297.68 ,99.75,91.44,66.64
XS GIS Cut Line= 5
     624478.6803    4316963.2498      624449.255    4316940.5804
     624419.5712    4316915.0192       624399.02    4316892.9137
     624240.0102     4316802.721
#Sta/Elev= 30
       0  656.56    2.86  653.66    8.57     647   11.43  644.18   17.14  639.46
      20  635.49   22.86  633.06   25.72  631.22   28.57  629.96   31.43  629.37
   43.17  629.32   61.25  628.77   94.43  630.72  124.78  631.94  127.83  632.29
  143.06  635.36   158.3  637.31  164.39  638.41  179.62  640.29  185.72  641.56
  200.95  643.47  207.05  644.82  246.65  647.63  252.75  648.81  258.84  649.44
  264.93  650.46  267.98  651.18  274.07  653.39  280.17  654.62  289.31  656.83
#Mann= 3 , 0 , 0
       0      .1       0   25.72      .1       0   94.43      .1       0
Bank Sta=25.72,94.43
XS Rating Curve= 0 ,0
Exp/Cntr=0.3,0.1

Type RM Length L Ch R = 1 ,4206.24 ,94.8,91.44,83.39
XS GIS Cut Line= 4
     624499.6539    4316852.9634     624435.1007    4316844.6341
     624367.2826    4316830.0579     624240.2947    4316779.9943
#Sta/Elev= 30
       0   656.4    2.96  653.77    5.92  648.69    8.88  646.21   11.83  644.05
   20.71  639.08   23.67  636.24   26.63  634.25    35.5  630.44   38.46  629.46
   41.42  628.92   47.34  628.62   56.21  628.86   65.09  629.79   89.22  631.83
  107.31  631.84  110.33  632.03  128.42  635.76  158.72  639.41  167.82  640.88
  170.86  641.76  189.06  644.47  192.09   644.7  216.36  645.23  225.46  646.04
  228.49  646.57  234.56   648.4  249.72  651.33  252.76  652.47  270.96  657.11
#Mann= 3 , 0 , 0
       0      .1       0   38.46      .1       0   65.09      .1       0
Bank Sta=38.46,65.09
XS Rating Curve= 0 ,0
Exp/Cntr=0.3,0.1

Type RM Length L Ch R = 1 ,4114.8  ,62.68,91.44,105.11
XS GIS Cut Line= 6
      624501.439    4316811.7444     624503.2603    4316764.1622
     624489.9046    4316755.2242     624468.2546    4316754.4672
      624435.403    4316759.4754     624239.5009    4316772.0568
#Sta/Elev= 30
       0   657.9    8.93  655.07   17.86  653.98   23.81  652.12   38.69   646.5
   44.64  645.76    50.3  644.62   52.97  643.54   55.65  641.86   58.33  639.58
    66.4  630.42    69.1  627.88  103.48  628.16  109.52  627.94  127.78  629.32
  155.39  631.95  167.66  632.28  189.13  635.91   192.2  636.73   210.6  639.12
  213.67  639.83     229  641.84  232.07  642.53  250.47   643.4  271.95  646.97
  278.08  648.57  293.42  651.36  299.55  653.41  311.82  656.52  314.89  657.98
#Mann= 3 , 0 , 0
       0      .1       0    66.4      .1       0  127.78      .1       0
Bank Sta=66.4,127.78
XS Rating Curve= 0 ,0
Exp/Cntr=0.3,0.1

Type RM Length L Ch R = 1 ,4023.36 ,53.9,91.44,109.66
XS GIS Cut Line= 6
     624506.2015    4316813.3319     624521.0231    4316762.8174
     624509.8013    4316721.4369     624482.5261    4316674.1997
      624467.711    4316665.3812     624407.7763    4316615.6877
#Sta/Elev= 30
       0  657.41    8.77  653.99   14.62  651.15   17.55  650.62   20.47  649.68
   26.32  647.35   32.17  645.97   46.79  643.39   49.72  643.15   74.08  638.69
   80.21   638.2   86.33  637.05   95.52  634.26   98.55  632.83  104.61  629.29
  107.64  628.14  110.67  627.87     144  627.89  152.94  628.19  164.43  627.96
   170.3  628.26  179.28  629.17  185.27  629.75  188.27  630.48  200.25  634.76
  212.22  640.94  218.21  643.58   224.2  644.93  230.19  649.09  245.16  658.03
#Mann= 3 , 0 , 0
       0      .1       0  104.61      .1       0  179.28      .1       0
Bank Sta=104.61,179.28
XS Rating Curve= 0 ,0
Exp/Cntr=0.3,0.1

Type RM Length L Ch R = 1 ,3931.92 ,66.67,91.44,105.88
XS GIS Cut Line= 6
      624510.964    4316815.7131      624536.364     4316764.913
     624540.4577    4316697.0422     624551.5702    4316671.6422
     624561.0889    4316660.3928     624573.7372    4316610.9242
#Sta/Elev= 30
       0  656.53    5.98  653.63   11.96  651.66   14.95  650.55   17.94  649.19
   23.91   647.4    26.9  645.66   29.89  644.47   32.88  644.12   38.86  642.36
    56.8  638.04   59.75  637.89   62.71  637.45    83.4  633.72   89.32  633.11
   98.18   631.3  115.92  629.68  118.88  629.65  124.79  628.93  133.11  628.12
  138.65  627.81  167.25  627.78  170.25  627.94  176.26  629.04  182.27  630.46
  185.27  631.93  188.28  632.86  191.28  634.16  200.29  641.31  218.31  657.12
#Mann= 3 , 0 , 0
       0      .1       0  124.79      .1       0  176.26      .1       0
Bank Sta=124.79,176.26
XS Rating Curve= 0 ,0
Exp/Cntr=0.3,0.1

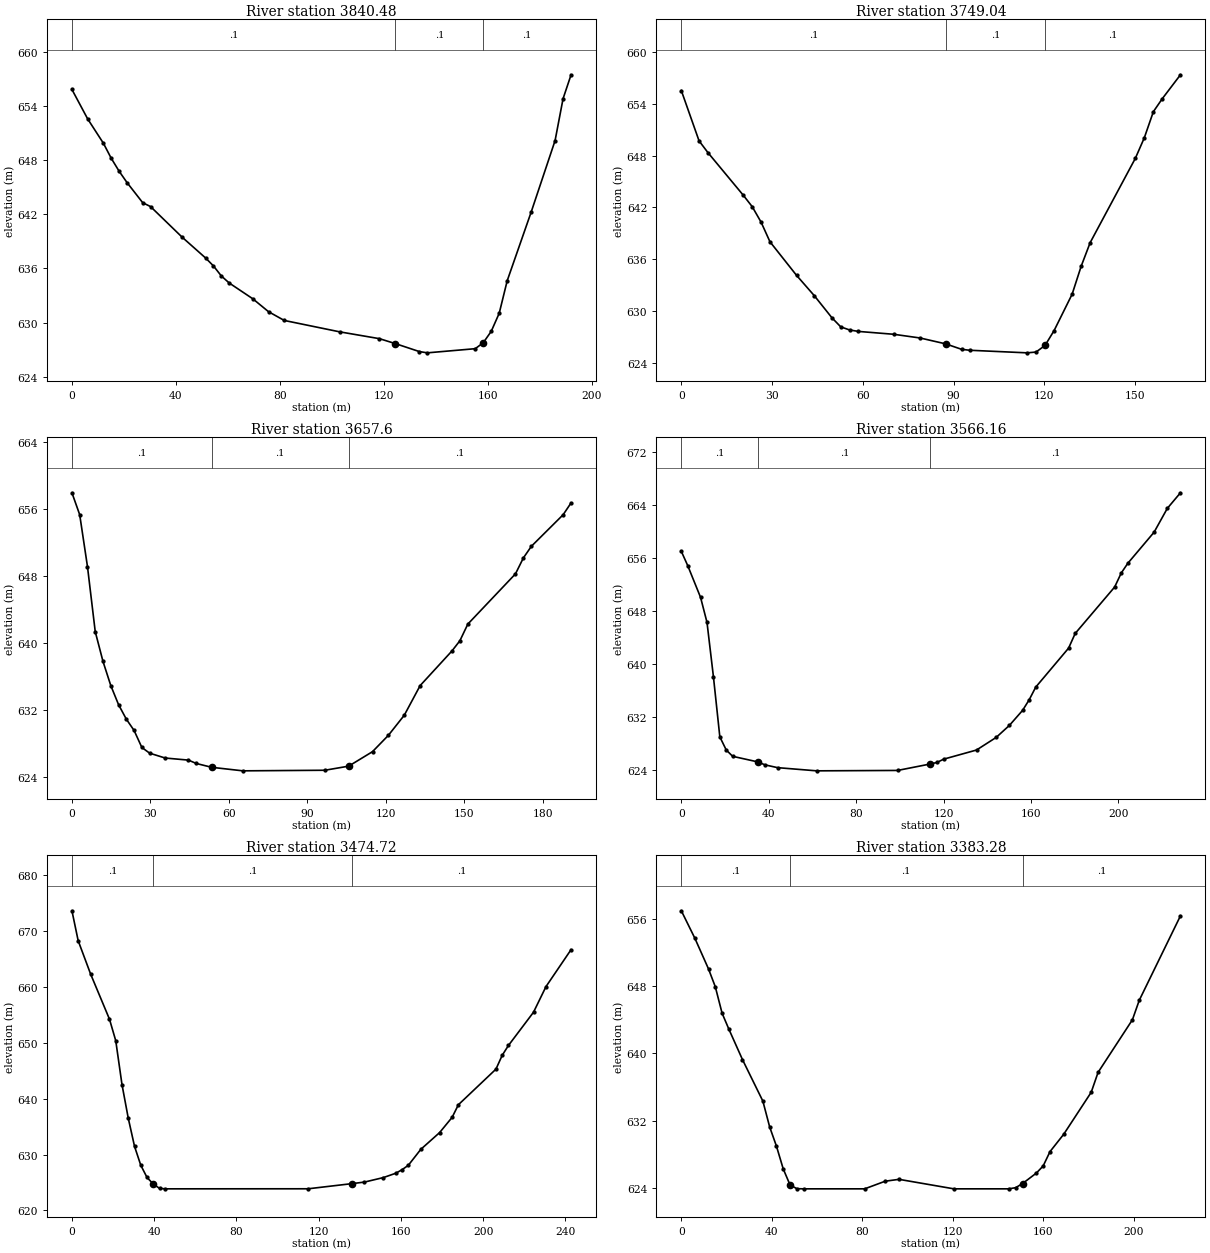
Type RM Length L Ch R = 1 ,3840.48 ,73.12,91.44,98.01
XS GIS Cut Line= 3
     624514.9328    4316817.3006     624571.5094    4316738.7009
     624662.3901    4316710.2116
#Sta/Elev= 30
       0  655.83    6.05  652.57   12.11  649.87   15.13   648.2   18.16  646.77
   21.18  645.52   27.24  643.28   30.26  642.85   42.37  639.47   51.45  637.15
   54.47  636.27    57.5  635.16   60.53  634.38   69.61  632.63   75.66   631.2
   81.71  630.23  102.99  628.97  118.35  628.21   124.5  627.66  133.71  626.78
  136.78  626.64  155.22   627.1  158.29  627.76  161.36  629.02  164.44  631.03
  167.51  634.63  176.72  642.23  185.94  650.17  189.01  654.81  192.09  657.46
#Mann= 3 , 0 , 0
       0      .1       0   124.5      .1       0  158.29      .1       0
Bank Sta=124.5,158.29
XS Rating Curve= 0 ,0
Exp/Cntr=0.3,0.1

Type RM Length L Ch R = 1 ,3749.04 ,91.59,91.44,93.88
XS GIS Cut Line= 6
     624517.0494    4316822.5923     624556.8181    4316803.9072
     624597.5747    4316805.5459     624607.0726    4316810.0423
     624617.0748     4316811.075     624675.3793     4316823.735
#Sta/Elev= 30
       0  655.53    5.86  649.71    8.79  648.35   20.51   643.4   23.43  642.09
   26.36   640.3   29.29  638.03   38.08  634.14   43.94  631.79   49.77  629.23
   52.68  628.18   55.59  627.82   58.51  627.65   70.16  627.32    78.9  626.89
   87.36  626.21   92.61  625.58   95.24  625.47  114.24  625.17  117.23  625.26
  120.21  626.03  123.19  627.74  129.16  631.96  132.14  635.19  135.12  637.93
  150.04  647.68  153.02  650.07  156.01  653.09  158.99  654.61  164.96  657.36
#Mann= 3 , 0 , 0
       0      .1       0   87.36      .1       0  120.21      .1       0
Bank Sta=87.36,120.21
XS Rating Curve= 0 ,0
Exp/Cntr=0.3,0.1

Type RM Length L Ch R = 1 ,3657.6  ,93.77,91.44,85.73
XS GIS Cut Line= 5
     624506.9952    4316887.6799     624572.1667    4316892.6724
     624579.8652    4316895.0774      624601.642    4316903.3305
     624691.7848    4316930.5333
#Sta/Elev= 30
       0  657.88    2.97  655.26    5.94  649.07    8.91   641.3   11.88  637.74
   14.86  634.86   17.83  632.58    20.8  630.85   23.77   629.5   26.74  627.47
   29.71  626.79   35.65  626.21   44.57  625.96   47.54  625.56   53.48   625.1
   65.36  624.68   96.72  624.75  105.83  625.24  114.94  626.97  121.01  628.92
  127.09  631.32  133.16  634.86  145.31  638.99  148.35  640.21  151.39   642.2
  169.61   648.2  172.65  650.11  175.69  651.49  187.84  655.26  190.87  656.67
#Mann= 3 , 0 , 0
       0      .1       0   53.48      .1       0  105.83      .1       0
Bank Sta=53.48,105.83
XS Rating Curve= 0 ,0
Exp/Cntr=0.3,0.1

Type RM Length L Ch R = 1 ,3566.16 ,91.28,91.44,96.55
XS GIS Cut Line= 6
       624486.49    4316969.7009     624533.0367    4316976.1692
     624545.0681    4316979.2364     624557.2049    4316982.8775
     624571.9498    4316984.5501     624710.0633    4317015.3416
#Sta/Elev= 30
       0  656.99    2.94  654.83    8.81  650.04   11.75  646.27   14.69  638.08
   17.62     629   20.56  627.01    23.5  626.06   35.25   625.2   38.18  624.78
   44.06  624.35   61.94  623.87   98.96  623.93  114.02  624.91  117.03  625.14
  120.04  625.63  135.09  627.01  144.12  628.92  150.15  630.73  156.17  632.99
  159.18  634.58  162.19   636.5  177.24  642.39  180.25   644.6  198.32  651.61
  201.33  653.72  204.34  655.19  216.38  659.89   222.4  663.47  228.43  665.83
#Mann= 3 , 0 , 0
       0      .1       0   35.25      .1       0  114.02      .1       0
Bank Sta=35.25,114.02
XS Rating Curve= 0 ,0
Exp/Cntr=0.3,0.1

Type RM Length L Ch R = 1 ,3474.72 ,96.4,91.44,75.76
XS GIS Cut Line= 5
     624470.4649    4317056.1466     624512.1814    4317064.8366
     624531.1149    4317070.5166     624545.8221    4317076.7245
     624703.4488    4317123.4242
#Sta/Elev= 30
       0   673.6    3.04  668.24    9.13  662.24   18.26  654.21   21.31  650.36
   24.35   642.5   27.39  636.51   30.44  631.47   33.48  628.09   36.52   625.9
   39.57  624.73   42.61  623.95   45.44  623.87  114.88  623.88  136.19   624.8
  142.28  625.08  151.41  625.88   157.5  626.66  160.54  627.29  163.59  628.08
  169.68  630.94  178.81  633.93   184.9  636.66  187.94  638.91  206.21  645.28
  209.25  647.75   212.3  649.52  224.48  655.46  230.56  660.05  242.74  666.65
#Mann= 3 , 0 , 0
       0      .1       0   39.57      .1       0  136.19      .1       0
Bank Sta=39.57,136.19
XS Rating Curve= 0 ,0
Exp/Cntr=0.3,0.1

Type RM Length L Ch R = 1 ,3383.28 ,91.76,91.44,90.88
XS GIS Cut Line= 4
     624463.7966    4317162.9639     624529.7002    4317158.6118
     624544.2677    4317155.2067     624683.5383    4317146.4775
#Sta/Elev= 30
       0  656.96       6  653.68   12.01  650.04   15.01  647.92   18.01  644.77
   21.01  642.87   27.02  639.25   36.03  634.31   39.03  631.24   42.03  628.95
   45.03  626.24   48.03  624.34   51.04  623.89   54.04  623.87   81.01  623.87
   90.11  624.78   96.18     625  120.44  623.87  144.71  623.87  147.75  624.01
  150.78   624.5  156.85  625.74  159.88  626.59  162.91   628.3  168.98  630.37
  181.11  635.36  184.15  637.73  199.32  643.99  202.35  646.31  220.55  656.36
#Mann= 3 , 0 , 0
       0      .1       0   48.03      .1       0  150.78      .1       0
Bank Sta=48.03,150.78
XS Rating Curve= 0 ,0
Exp/Cntr=0.3,0.1