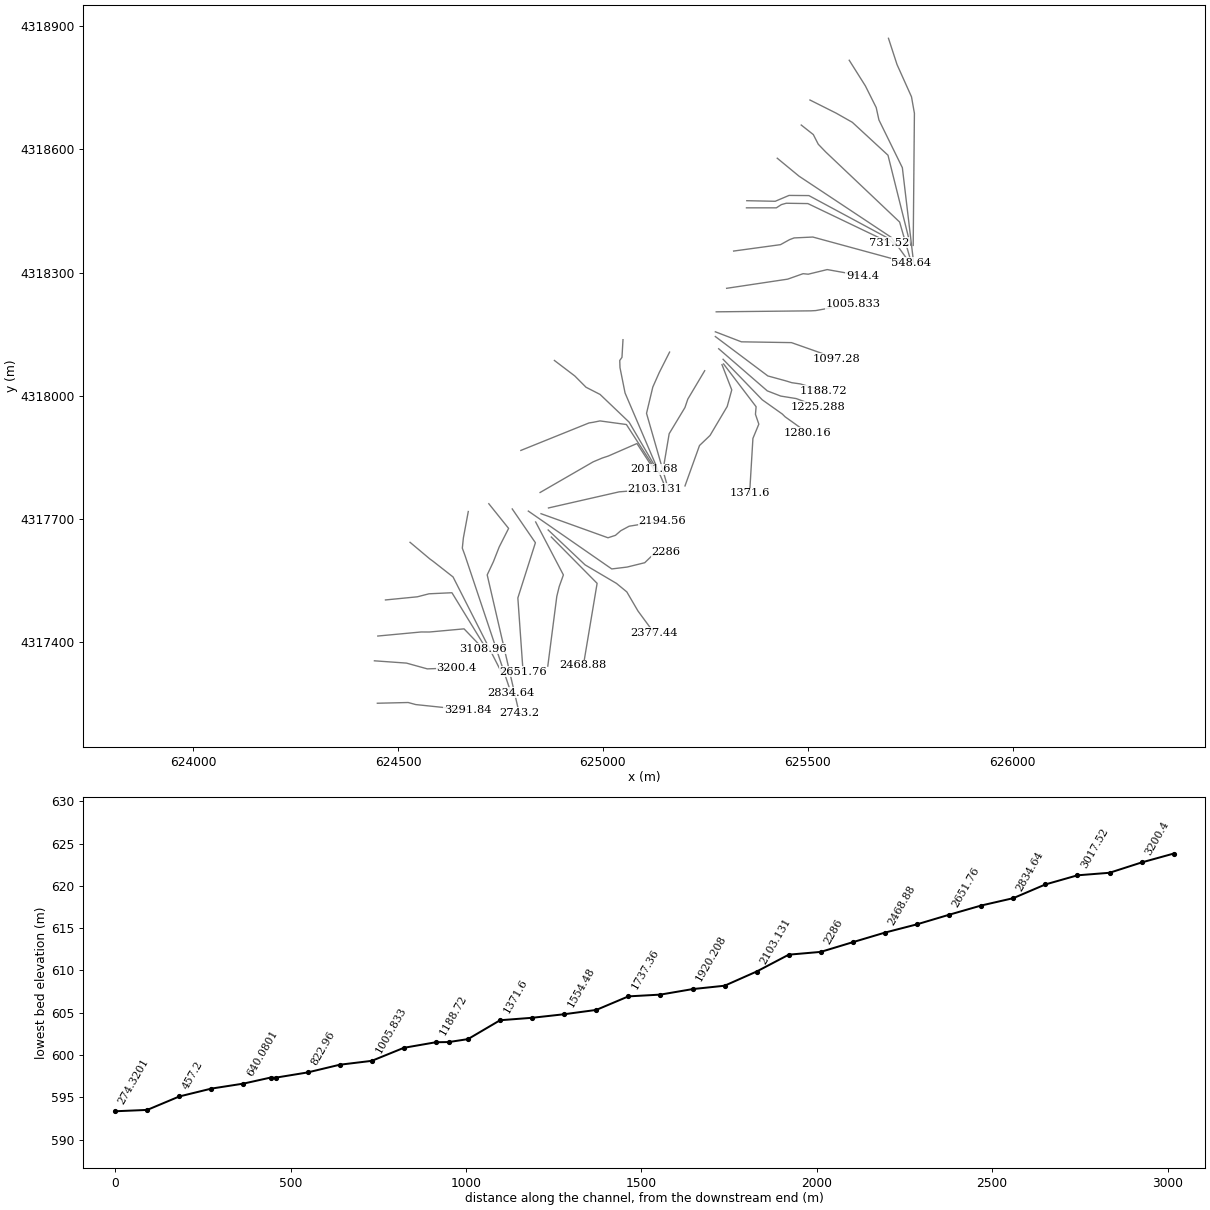
HEC-RAS study RedCreek.prj: RedCreek

--- RedCreek.g01 (geometry) --- (continued)

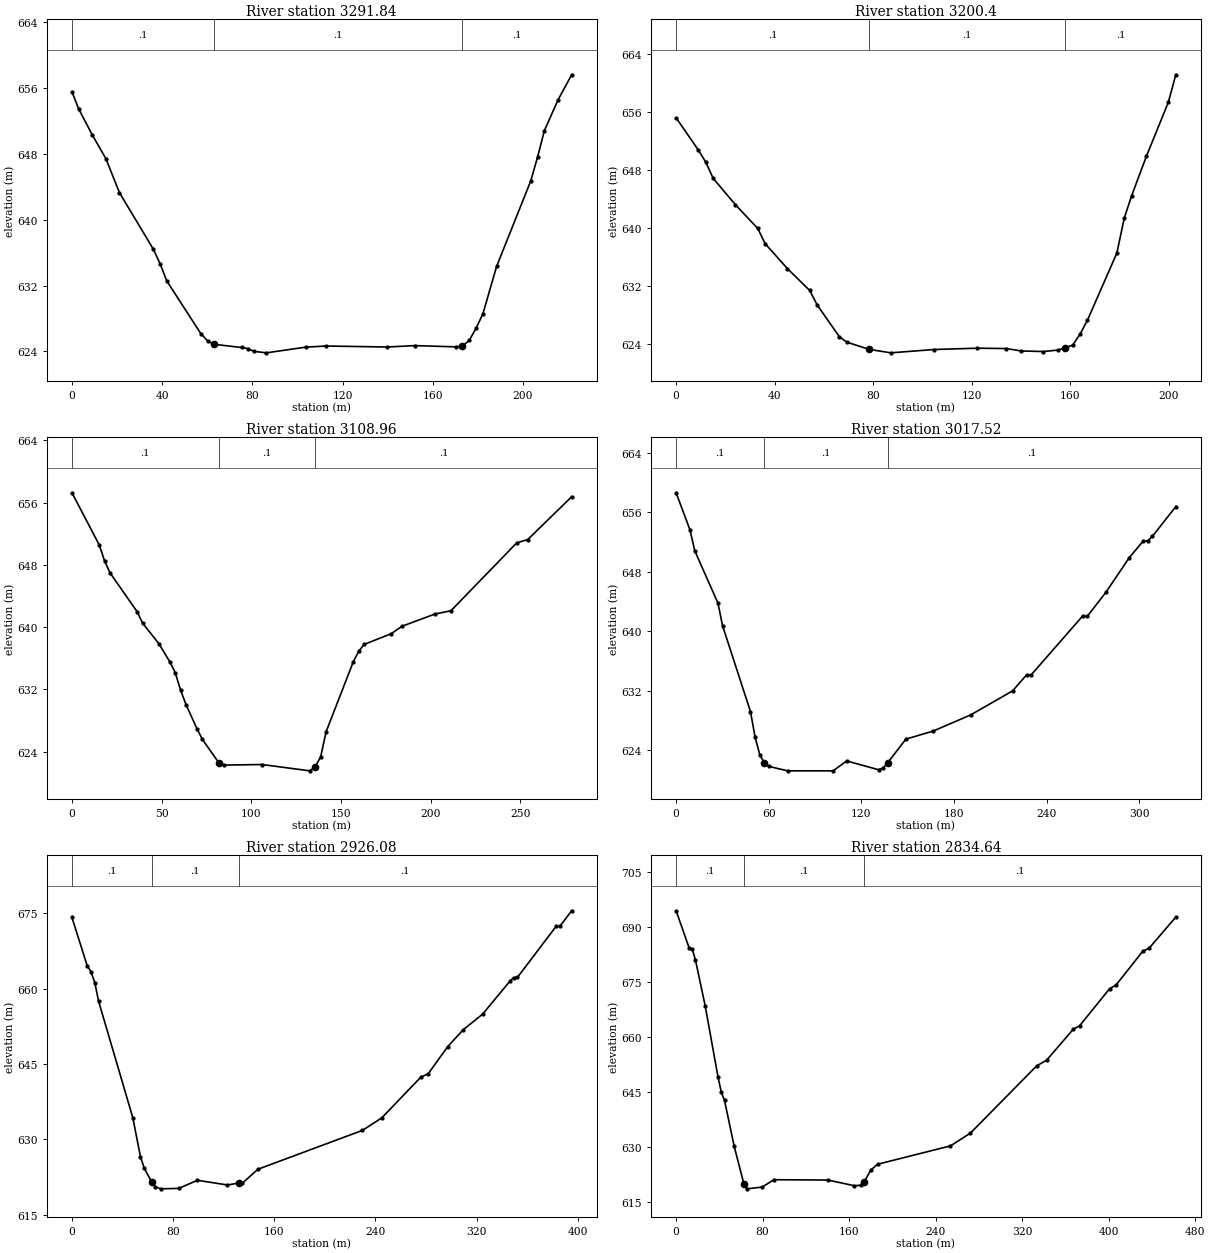
Type RM Length L Ch R = 1 ,3291.84 ,98.2,91.44,91.51
XS GIS Cut Line= 4
      624449.746     4317250.077     624524.9339    4317251.8345
     624543.5468    4317246.8039     624669.9436    4317233.5881
#Sta/Elev= 30
       0  655.57    3.01  653.47    9.02  650.32   15.04  647.44   21.06   643.3
    36.1  636.42   39.11  634.63   42.12  632.53   57.16  626.15   60.17  625.27
   62.92  624.86   75.21  624.47   77.96  624.33   80.72     624   86.23  623.82
  103.57  624.51  112.64  624.65  139.88  624.53  151.98   624.7  170.14  624.55
  173.16  624.64  176.19  625.35  179.21  626.81  182.24  628.58  188.29  634.33
  203.42  644.72  206.45  647.62  209.47  650.84  215.52  654.58  221.57  657.64
#Mann= 3 , 0 , 0
       0      .1       0   62.92      .1       0  173.16      .1       0
Bank Sta=62.92,173.16
XS Rating Curve= 0 ,0
Exp/Cntr=0.3,0.1

Type RM Length L Ch R = 1 ,3200.4  ,88.3,91.44,95.03
XS GIS Cut Line= 4
     624442.6014    4317353.4991     624520.7776    4317347.9129
      624571.637    4317333.8394     624643.3708    4317336.3463
#Sta/Elev= 30
       0  655.18    9.04  650.73   12.06  649.05   15.07  646.82   24.12  643.18
   33.16  639.92   36.17  637.82   45.22  634.38   54.26  631.37   57.27  629.38
   66.32  624.98   69.33  624.24   78.38  623.25   87.17  622.77  104.76  623.23
  122.35  623.41  134.14  623.36  140.12  623.03  149.09  622.95  155.07  623.15
  158.06  623.48  161.05  623.83  164.04  625.34  167.03  627.26     179  636.53
  181.99  641.34  184.98  644.42  190.96  649.85  199.93  657.35  202.92  661.11
#Mann= 3 , 0 , 0
       0      .1       0   78.38      .1       0  158.06      .1       0
Bank Sta=78.38,158.06
XS Rating Curve= 0 ,0
Exp/Cntr=0.3,0.1

Type RM Length L Ch R = 1 ,3108.96 ,86.19,91.44,92.9
XS GIS Cut Line= 5
     624450.8474    4317413.8986     624556.3857    4317423.7725
     624576.9253    4317423.7254     624661.2937    4317431.3952
     624707.9379    4317382.9192
#Sta/Elev= 30
       0  657.27   15.14   650.6   18.17  648.53    21.2  646.99   36.34  641.99
   39.37  640.53   48.46  637.88   54.51  635.57   57.54  634.18   60.57   631.9
    63.6  630.04   69.66  626.97   72.69  625.59   81.77  622.62    84.8  622.29
     106  622.36  132.59  621.55  135.62  622.08  138.64  623.36  141.67  626.58
  156.79  635.54  159.82  636.91  162.85  637.79  177.97  639.17  184.02  640.13
  202.18  641.68  211.26  642.12  247.95  650.84  254.07  651.26  278.53  656.76
#Mann= 3 , 0 , 0
       0      .1       0   81.77      .1       0  135.62      .1       0
Bank Sta=81.77,135.62
XS Rating Curve= 0 ,0
Exp/Cntr=0.3,0.1

Type RM Length L Ch R = 1 ,3017.52 ,107.64,91.44,71.87
XS GIS Cut Line= 5
     624469.5637     4317501.856     624547.4631    4317509.5428
     624575.8023    4317516.8561     624631.7377    4317519.4445
     624715.3462    4317382.9192
#Sta/Elev= 30
       0  658.62    9.03  653.61   12.04  650.85    27.1  643.79   30.11  640.73
   48.17  629.22   51.18  625.77   54.19  623.41    57.2   622.3   60.21  621.84
   72.26  621.25  101.69  621.25  110.49  622.58  131.12   621.4  134.07  621.63
  137.02  622.33  148.81  625.51  166.56   626.6  190.73  628.76  217.91  631.99
  226.97  634.14  229.99  634.15  263.22  642.04  266.24     642  278.32  645.23
  293.43  649.88  302.49  652.13  305.51  652.16  308.53  652.78  323.63  656.76
#Mann= 3 , 0 , 0
       0      .1       0    57.2      .1       0  137.02      .1       0
Bank Sta=57.2,137.02
XS Rating Curve= 0 ,0
Exp/Cntr=0.3,0.1

Type RM Length L Ch R = 1 ,2926.08 ,115.23,91.44,67.85
XS GIS Cut Line= 5
     624529.5284    4317642.3413     624577.9174    4317601.7288
     624585.5155    4317596.2594     624634.4916    4317557.8576
     624752.3879    4317325.7691
#Sta/Elev= 30
       0   674.2   12.03  664.59   15.04  663.39   18.05  661.21   21.06  657.52
   48.13  634.31   54.15  626.56   57.16   624.3   63.17  621.46   65.51  620.62
   70.19  620.17   84.39  620.26   99.21  621.87  122.92  620.94  131.81  621.32
  134.77   621.3  147.02  624.07  229.71  631.81  245.02  634.31  275.65  642.36
  281.77  643.11  297.09  648.48  309.34  651.84  324.65  654.94  346.09  661.45
  349.15  662.23  352.21  662.26  382.84  672.44   385.9  672.49  395.09  675.53
#Mann= 3 , 0 , 0
       0      .1       0   63.17      .1       0  131.81      .1       0
Bank Sta=63.17,131.81
XS Rating Curve= 0 ,0
Exp/Cntr=0.3,0.1

Type RM Length L Ch R = 1 ,2834.64 ,94.54,91.44,79.65
XS GIS Cut Line= 5
     624671.6112     4317717.417      624659.622    4317652.8786
     624657.0595    4317628.1086     624663.6876    4317610.0881
     624775.6713    4317276.0273
#Sta/Elev= 30
       0  694.41   11.94  684.38   14.92  683.94    17.9  680.98   26.85  668.55
   38.79  649.01   41.77  644.94   44.76  642.68   53.71  630.15   62.66  619.92
   65.64  618.55   79.48  619.03   90.54  621.04  140.38  620.95  164.89  619.39
  171.02  619.55  174.08  620.55  180.21  623.73  186.34  625.26  253.74  630.27
  272.12  633.74   333.4  652.09  342.59  653.63   367.1  662.04  373.23  663.07
   400.8  673.12  406.93  674.19  431.44  683.34  437.57  684.25  462.08  692.68
#Mann= 3 , 0 , 0
       0      .1       0   62.66      .1       0  174.08      .1       0
Bank Sta=62.66,174.08
XS Rating Curve= 0 ,0
Exp/Cntr=0.3,0.1

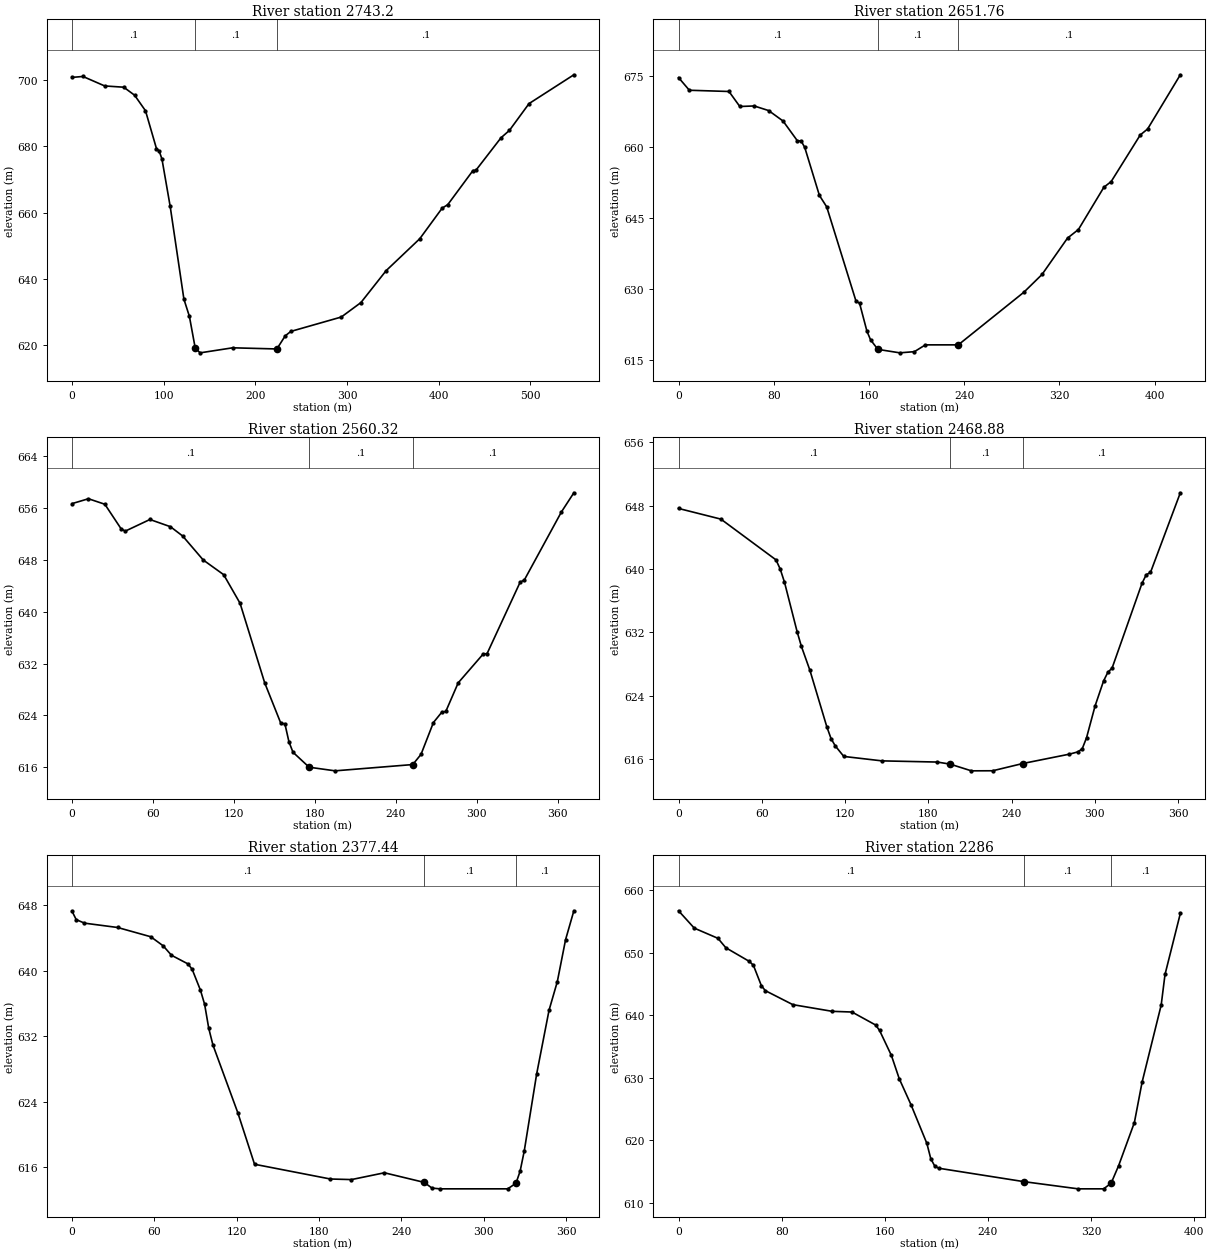
Type RM Length L Ch R = 1 ,2743.2  ,87.17,91.44,91.28
XS GIS Cut Line= 6
     624721.6962    4317736.4032     624770.0079    4317676.2667
     624746.9839    4317630.8802     624732.9783     4317595.266
     624717.7737    4317562.8934     624795.7797    4317226.2855
#Sta/Elev= 30
       0  700.83   11.87  701.11    35.6  698.25   56.37  697.87   68.24  695.45
   80.13  690.76   92.11  679.33    95.1  678.57   98.09  676.19  107.08  661.87
  122.04  633.89  128.03   628.7  134.42  619.08  139.81  617.68  175.24   619.2
  223.47  618.85  232.64  622.82  238.76  624.15   293.8  628.49   315.2  632.85
  342.72  642.49  379.42  652.12  403.88  661.36  409.99  662.42  437.51  672.72
  440.57  672.75  468.09   682.6  477.27  684.83  498.67  692.92  547.59  701.62
#Mann= 3 , 0 , 0
       0      .1       0  134.42      .1       0  223.47      .1       0
Bank Sta=134.42,223.47
XS Rating Curve= 0 ,0
Exp/Cntr=0.3,0.1

Type RM Length L Ch R = 1 ,2651.76 ,89.31,91.44,95.56
XS GIS Cut Line= 4
     624778.8463    4317723.7032     624835.3942    4317641.3447
     624792.5612    4317506.7583     624805.3047    4317326.8274
#Sta/Elev= 30
       0  674.58    9.08  671.91   42.38  671.65   51.47  668.49   63.57   668.6
   75.68  667.63   87.79  665.43    99.9  661.24  102.97  661.24  106.04  659.85
  118.33  649.76  124.47  647.34  149.03  627.52   152.1  627.01  158.24  621.17
  161.31  619.33  167.45  617.32  185.87  616.59  198.16  616.84  207.37  618.27
     235  618.27  290.06  629.35  305.34   633.1  326.75  640.76  335.92  642.57
  357.32  651.48  363.43  652.67  387.89   662.5  394.01  663.74  421.52  675.17
#Mann= 3 , 0 , 0
       0      .1       0  167.45      .1       0     235      .1       0
Bank Sta=167.45,235
XS Rating Curve= 0 ,0
Exp/Cntr=0.3,0.1

Type RM Length L Ch R = 1 ,2560.32 ,87.43,91.44,91.81
XS GIS Cut Line= 5
     624835.9964    4317691.9531     624903.6873    4317562.8378
     624893.5422    4317534.6839     624887.6156    4317510.6366
     624865.6298    4317340.5858
#Sta/Elev= 30
       0  656.67   12.15  657.42    24.3  656.57   36.45  652.75   39.48  652.43
   57.71  654.22   72.89  653.11      82  651.67   97.19  647.98  112.37  645.71
  124.52   641.3  142.75  629.05  154.76  622.78  157.75  622.72  160.75  619.94
  163.74  618.33  175.71  616.02  194.97  615.46  252.53  616.43  258.65     618
  267.84  622.91  273.96  624.48  277.02  624.62  286.21  629.03  304.58  633.44
  307.64  633.55  332.14  644.56   335.2  644.88  362.76   655.4  371.94  658.34
#Mann= 3 , 0 , 0
       0      .1       0  175.71      .1       0  252.53      .1       0
Bank Sta=175.71,252.53
XS Rating Curve= 0 ,0
Exp/Cntr=0.3,0.1

Type RM Length L Ch R = 1 ,2468.88 ,50.62,91.44,116.25
XS GIS Cut Line= 3
     624874.2024    4317655.2289     624985.9525    4317542.3753
     624952.4235    4317342.3369
#Sta/Elev= 30
       0  647.64   30.54  646.29   70.25  641.14    73.3  639.97   76.36  638.32
   85.52  632.03   88.57   630.2   94.68  627.19   106.9  620.03  109.95  618.54
  113.01  617.62  119.12   616.3   146.6  615.74  186.48  615.59   195.7  615.33
  211.06  614.48  226.43  614.49  247.94   615.4  281.75  616.59  287.89  616.88
  290.97  617.28  294.04  618.65  300.19  622.67  306.33  625.84  309.41  626.93
  312.48  627.47  333.99  638.16  337.06  639.26  340.14  639.55  361.65  649.62
#Mann= 3 , 0 , 0
       0      .1       0   195.7      .1       0  247.94      .1       0
Bank Sta=195.7,247.94
XS Rating Curve= 0 ,0
Exp/Cntr=0.3,0.1

Type RM Length L Ch R = 1 ,2377.44 ,37.05,91.44,150.91
XS GIS Cut Line= 6
     624866.5294    4317672.4268     624956.5048    4317587.4206
     625033.2474    4317542.1562     625058.3828    4317521.5186
      625085.635    4317474.9519     625124.9324    4317421.5461
#Sta/Elev= 30
       0  647.23    3.02  646.21    9.06  645.78   33.21  645.25   57.36  644.12
   66.42  643.01   72.46  641.86   84.53   640.8   87.55  640.14   93.59  637.59
   96.61  635.88   99.63  632.94  102.65  630.92  120.76  622.66     133  616.35
   188.3  614.55  203.66  614.48  227.66  615.31  256.63  614.14  262.35  613.44
  268.17  613.35  317.53  613.35  323.55  614.03  326.57   615.5  329.58  617.96
  338.62  627.36  347.66  635.15  353.69  638.64  359.72  643.77  365.75  647.29
#Mann= 3 , 0 , 0
       0      .1       0  256.63      .1       0  323.55      .1       0
Bank Sta=256.63,323.55
XS Rating Curve= 0 ,0
Exp/Cntr=0.3,0.1

Type RM Length L Ch R = 1 ,2286    ,79.55,91.44,87.87
XS GIS Cut Line= 6
     624818.1106    4317718.4644     625021.6851    4317577.4419
     625059.0884    4317582.0091     625102.1415    4317592.6141
     625119.2812     4317609.129     625153.8675     4317617.658
#Sta/Elev= 30
       0  656.72   12.23  653.94   30.57  652.31   36.69   650.8   55.03   648.6
   58.09  647.98   64.21  644.75   67.26  643.94   88.66  641.69  119.24  640.62
  134.53  640.51  152.87  638.43  155.93  637.56   165.1  633.56  171.21  629.82
  180.39  625.63  192.62  619.47  195.67  617.01  198.73  615.85  201.79   615.5
  267.94  613.35  309.94   612.2  329.74   612.2  335.56  613.11  341.39  615.93
  353.58  622.82  359.52  629.25  374.36  641.62  377.33  646.52  389.21  656.29
#Mann= 3 , 0 , 0
       0      .1       0  267.94      .1       0  335.56      .1       0
Bank Sta=267.94,335.56
XS Rating Curve= 0 ,0
Exp/Cntr=0.3,0.1

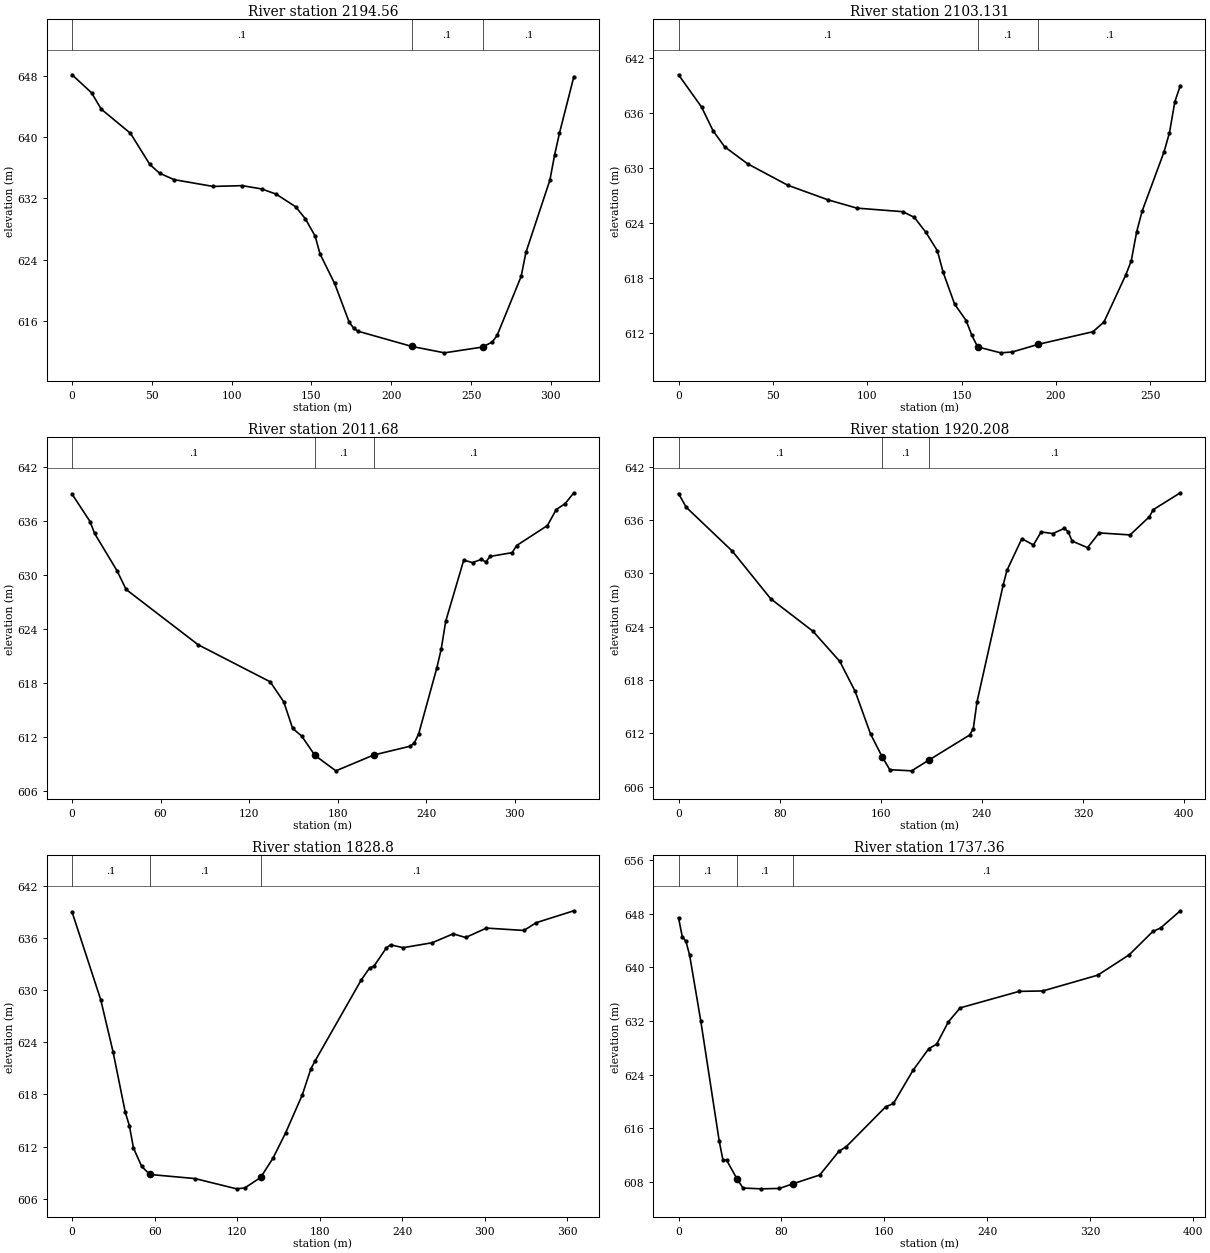
Type RM Length L Ch R = 1 ,2194.56 ,102.17,91.43,85.42
XS GIS Cut Line= 6
     624849.0669    4317712.1144     625012.4555    4317653.4071
     625030.7118    4317659.3602     625043.5541    4317670.5318
     625064.0493    4317681.5853     625144.0761    4317694.5786
#Sta/Elev= 30
       0  648.11   12.18  645.77   18.28  643.63   36.55  640.49   48.73  636.42
   54.83  635.28   63.96  634.44   88.33  633.56  106.61  633.66  118.79  633.23
  127.93  632.55  140.11   630.9   146.2  629.33  152.29  627.08  155.34  624.76
  164.48  620.92  173.62  615.87  176.36   615.1   179.1  614.69  212.76  612.71
   233.3  611.87  257.33  612.63  263.33   613.3  266.33  614.16  281.35  621.83
  284.35  624.96  299.36  634.38  302.37  637.71  305.37  640.51  314.38  647.87
#Mann= 3 , 0 , 0
       0      .1       0  212.76      .1       0  257.33      .1       0
Bank Sta=212.76,257.33
XS Rating Curve= 0 ,0
Exp/Cntr=0.3,0.1

Type RM Length L Ch R = 1 ,2103.131,85.99,91.45,111.43
XS GIS Cut Line= 5
     624867.3232    4317726.0933     625039.7292    4317765.3628
     625064.7461    4317767.3633     625084.8544    4317762.6008
     625126.9824    4317772.9342
#Sta/Elev= 30
       0  640.16   12.19  636.65   18.29  634.07   24.39  632.33   36.58  630.47
   57.92  628.13   79.26  626.54   94.51  625.64   118.9  625.25  124.99  624.63
  131.09     623  137.19     621  140.24  618.66  146.34  615.18  152.43   613.4
  155.48  611.78  158.53  610.53  170.72  609.88  176.82  609.97  190.76  610.81
  219.63  612.18  225.47  613.23  237.04  618.36  239.93  619.88  242.83  623.07
  245.72  625.31  257.28  631.74  260.18  633.83  263.07  637.24  265.96  638.99
#Mann= 3 , 0 , 0
       0      .1       0  158.53      .1       0  190.76      .1       0
Bank Sta=158.53,190.76
XS Rating Curve= 0 ,0
Exp/Cntr=0.3,0.1

Type RM Length L Ch R = 1 ,2011.68 ,93.7,91.47,88.41
XS GIS Cut Line= 6
     624846.8179    4317763.7965     624976.3216    4317838.4983
     624998.5653    4317847.8263     625013.2018    4317852.6354
     625083.1904    4317883.1831     625123.9695     4317820.682
#Sta/Elev= 30
       0  639.03    12.2  635.97   15.26  634.65   30.51  630.48   36.61  628.41
   85.43  622.25  134.25  618.12   143.4   615.9   149.5  612.92  155.53  612.09
  164.58  609.92  178.76   608.2   204.3  609.96  228.74  610.93   231.8  611.27
  234.85  612.31  247.07  619.61  250.12  621.75  253.18  624.86   265.4  631.68
  271.37   631.4  277.34  631.76  280.32  631.47  283.31  632.09  298.23  632.51
  301.22   633.3  322.11  635.53  328.08  637.31  334.05  637.96  340.02  639.18
#Mann= 3 , 0 , 0
       0      .1       0  164.58      .1       0   204.3      .1       0
Bank Sta=164.58,204.3
XS Rating Curve= 0 ,0
Exp/Cntr=0.3,0.1

Type RM Length L Ch R = 1 ,1920.208,129.33,91.41,71.33
XS GIS Cut Line= 6
     624799.8889    4317866.3461     624966.1386    4317933.3129
     624976.3001    4317934.9023      624993.009    4317938.2667
     625057.4044    4317929.4832      625125.557    4317824.2539
#Sta/Elev= 30
       0  638.98    6.08  637.44   42.53  632.51   72.91  627.15  106.32   623.5
  127.59   620.1  139.74  616.73  151.89  611.94     161   609.4  167.08  607.93
  184.37   607.8  198.04  609.01  230.19  611.82  233.15  612.53   236.1  615.56
  256.78  628.69  259.73  630.33  271.55  633.91  280.72   633.2  286.84  634.67
  296.01  634.48  305.19  635.07  308.25  634.68   311.3  633.64  323.53   632.9
  332.71  634.56  357.17  634.33  372.46  636.38  375.52  637.17  396.92  639.07
#Mann= 3 , 0 , 0
       0      .1       0     161      .1       0  198.04      .1       0
Bank Sta=161,198.04
XS Rating Curve= 0 ,0
Exp/Cntr=0.3,0.1

Type RM Length L Ch R = 1 ,1828.8  ,126.89,91.44,68.02
XS GIS Cut Line= 6
     624881.7743    4318085.6169     624931.5237    4318047.8355
     624958.9003    4318020.3242     624993.1874     4318002.822
     625063.8871    4317935.4255     625128.2029    4317825.8414
#Sta/Elev= 30
       0  638.96   20.82  628.88   29.75  622.92   38.67  615.94   41.65   614.4
   44.62  611.84   50.57  609.73   56.52   608.8   89.34  608.33  119.54  607.15
  125.62  607.26  137.03  608.46  145.99  610.67  155.15  613.57  167.36  617.97
  173.46  620.91  176.52  621.83  210.09  631.14   216.2  632.53  219.25  632.71
  228.41  634.84  231.46  635.19  240.59  634.86  261.77  635.43  276.89  636.45
  285.97  636.03   301.1  637.11  328.32  636.84   337.4  637.74  364.63   639.1
#Mann= 3 , 0 , 0
       0      .1       0   56.52      .1       0  137.03      .1       0
Bank Sta=56.52,137.03
XS Rating Curve= 0 ,0
Exp/Cntr=0.3,0.1

Type RM Length L Ch R = 1 ,1737.36 ,110.3,91.44,76.55
XS GIS Cut Line= 6
     625049.0898    4318136.2769     625046.6177    4318093.2116
     625041.1951    4318085.6027     625041.7671    4318068.1861
     625054.1583    4318006.2958     625155.1904    4317770.2788
#Sta/Elev= 30
       0   647.4    2.88   644.6    5.75  643.89    8.63  641.82   17.25  632.06
   31.63  614.09   34.51  611.26   37.38  611.22   45.47  608.43   50.14  607.06
    64.4  606.94    78.5     607   89.38  607.72  109.84  609.01  124.63  612.52
  130.55  613.26  161.01  619.17  167.12  619.68  182.41  624.65  194.63  627.87
  200.74  628.53  209.91  631.89  219.08  633.96  264.93  636.42  283.26  636.48
  326.05  638.84   350.5  641.88  368.84  645.36  374.95  645.89  390.24  648.45
#Mann= 3 , 0 , 0
       0      .1       0   45.47      .1       0   89.38      .1       0
Bank Sta=45.47,89.38
XS Rating Curve= 0 ,0
Exp/Cntr=0.3,0.1

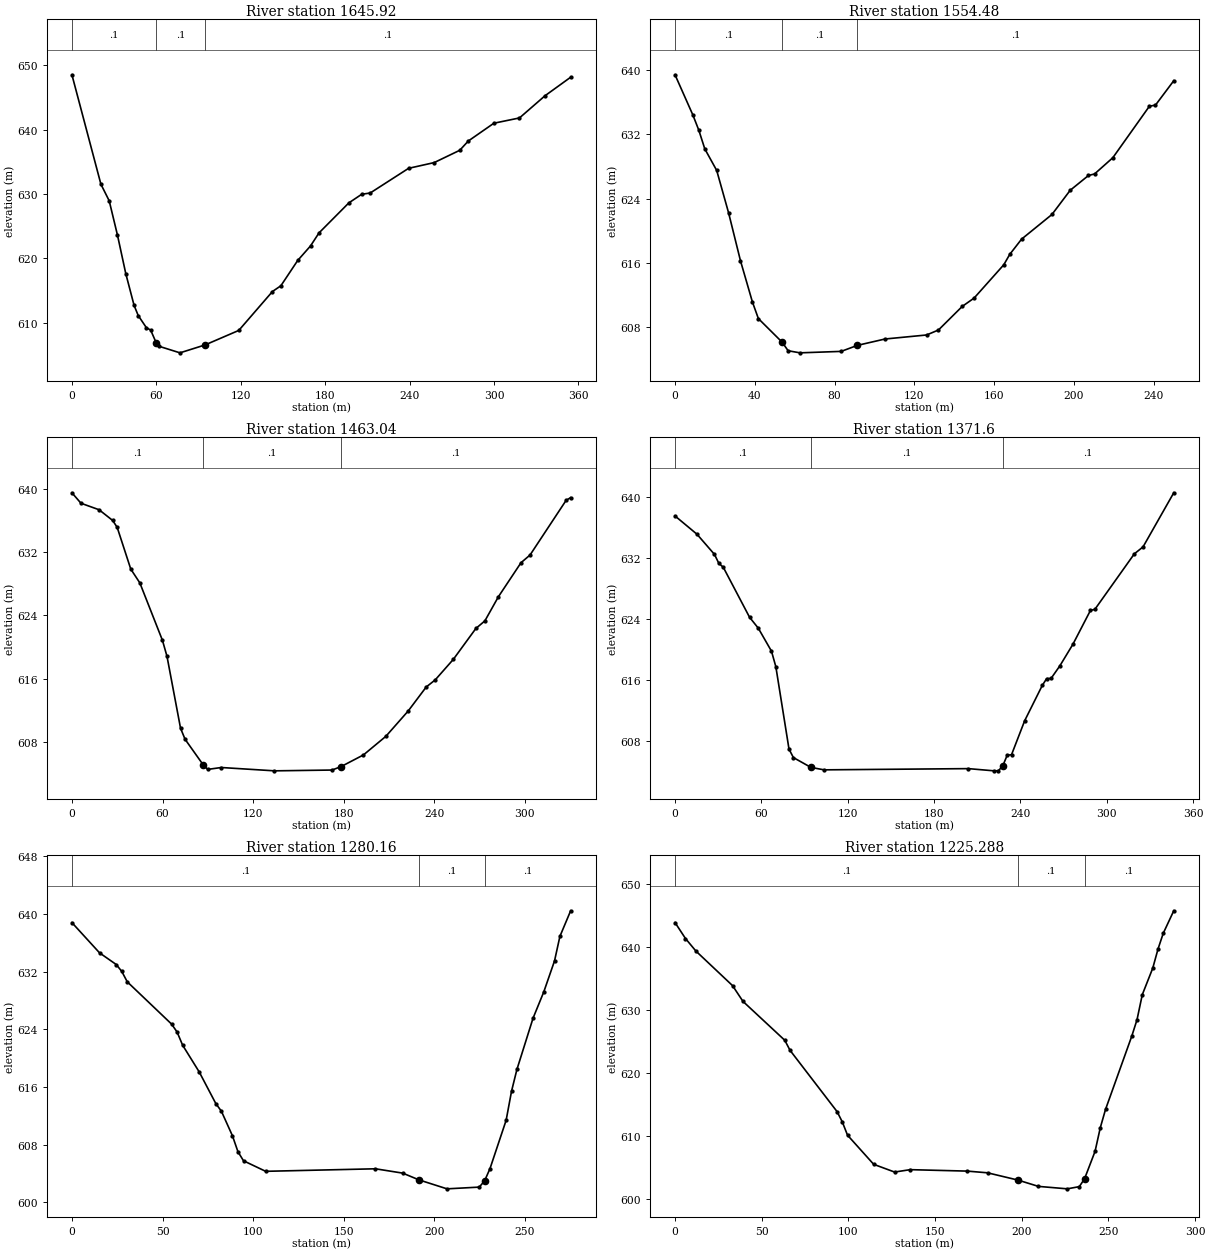
Type RM Length L Ch R = 1 ,1645.92 ,93.49,91.44,91.03
XS GIS Cut Line= 5
     625162.7961    4318106.0395     625137.5342    4318056.1159
     625121.8064    4318020.7286     625106.5199    4317956.7165
     625160.1514    4317770.2788
#Sta/Elev= 30
       0   648.5   20.61  631.51    26.5  628.94   32.39   623.6   38.28  617.64
   44.17  612.72   47.12  611.13   53.01  609.22   55.95  608.88   59.91   606.9
   61.91  606.36    76.8  605.34   94.68  606.57  118.61  608.82  142.54  614.86
  148.52  615.75  160.49  619.68  169.58  621.93  175.64  623.96  196.86  628.62
  205.96  629.95  212.02  630.15   239.3  633.98  257.49  634.87  275.67  636.78
  281.74  638.22  299.92  640.98  318.11   641.8   336.3  645.25  354.49  648.12
#Mann= 3 , 0 , 0
       0      .1       0   59.91      .1       0   94.68      .1       0
Bank Sta=59.91,94.68
XS Rating Curve= 0 ,0
Exp/Cntr=0.3,0.1

Type RM Length L Ch R = 1 ,1554.48 ,91.46,91.44,92.1
XS GIS Cut Line= 5
     625248.4421    4318060.6253     625207.2436    4317991.3889
     625200.2351    4317970.8283     625161.7749    4317907.1017
      625149.568    4317834.8372
#Sta/Elev= 30
       0   639.4    8.95   634.4   11.94   632.5   14.92  630.19   20.89  627.51
   26.86  622.23   32.82  616.27   38.79  611.16   41.78  609.09   53.71  606.15
    56.7  605.09   62.66  604.83   83.28  605.01   91.43  605.76  105.27  606.55
  126.11  607.05  132.06  607.67  143.97   610.6  149.93  611.64  164.81  615.78
  167.79  617.07  173.74  618.97  188.94  622.03   198.1  625.04  207.26  626.88
  210.31  627.07  219.47  629.09   237.8  635.49  240.85  635.63  250.01  638.66
#Mann= 3 , 0 , 0
       0      .1       0   53.71      .1       0   91.43      .1       0
Bank Sta=53.71,91.43
XS Rating Curve= 0 ,0
Exp/Cntr=0.3,0.1

Type RM Length L Ch R = 1 ,1463.04 ,70.29,91.44,116.97
XS GIS Cut Line= 6
     625290.6538    4318075.3831     625314.4664    4318013.8673
     625303.3431    4317973.4362     625261.4526    4317902.8088
     625235.7527    4317878.2681     625200.3681    4317779.8038
#Sta/Elev= 30
       0  639.47       6  638.15   17.99  637.33   26.99  635.98   29.98  635.11
   38.98  629.85   44.98  628.11   59.97  620.86   62.97  618.85   71.95  609.78
   74.95  608.39   86.93  605.17   89.93  604.59   98.91  604.83  134.16  604.41
  172.25  604.51  178.22  604.94  193.12  606.42  207.93  608.76  222.74  611.96
  234.66  614.98  240.64  615.88   252.6  618.46  267.55  622.36  273.53  623.32
   282.5  626.37  297.44  630.65  303.42  631.62  327.34  638.52  330.33  638.86
#Mann= 3 , 0 , 0
       0      .1       0   86.93      .1       0  178.22      .1       0
Bank Sta=86.93,178.22
XS Rating Curve= 0 ,0
Exp/Cntr=0.3,0.1

Type RM Length L Ch R = 1 ,1371.6  ,35.71,91.44,126.44
XS GIS Cut Line= 6
     625294.5013    4318077.1139     625373.8765    4317972.8678
      625372.289     4317954.347     625380.5207    4317930.4124
     625366.1006    4317895.6327     625358.0601    4317761.8121
#Sta/Elev= 30
       0  637.54   15.24  635.15   27.42   632.5   30.47  631.32   33.52  630.82
    51.8  624.26   57.89  622.82   67.04  619.81   70.08  617.77   79.22  606.97
   82.27  605.86   94.46  604.57   103.6  604.25  203.89  604.41  221.72  604.12
  224.76  604.13  227.81  604.78  230.86  606.16   233.9  606.24  243.04   610.7
  255.23  615.31  258.28  616.21  261.33  616.23  267.42  617.87  276.56  620.72
  288.75  625.16  291.79  625.29  319.22  632.57  325.31  633.49  346.64  640.58
#Mann= 3 , 0 , 0
       0      .1       0   94.46      .1       0  227.81      .1       0
Bank Sta=94.46,227.81
XS Rating Curve= 0 ,0
Exp/Cntr=0.3,0.1

Type RM Length L Ch R = 1 ,1280.16 ,27.63,54.87,61.31
XS GIS Cut Line= 5
     625293.3107     4318088.491     625388.8964    4317989.7195
     625437.9058    4317954.9555     625444.6158    4317948.3049
      625500.181    4317908.7161
#Sta/Elev= 30
       0  638.81   15.27  634.61   24.44     633   27.49  632.05   30.54   630.6
   54.98  624.74   58.03  623.64   61.09  621.81   70.25   618.1   79.42  613.71
   82.47  612.66   88.58  609.25   91.63  607.03   94.69  605.78  106.91  604.32
  167.49  604.67  182.52  604.07  191.53  603.13  206.98  601.89  224.78  602.13
  227.75  603.01  230.72  604.71  239.61   611.4  242.58  615.42  245.55  618.44
  254.45  625.55  260.38   629.2  266.31   633.5  269.28   636.9  275.21  640.45
#Mann= 3 , 0 , 0
       0      .1       0  191.53      .1       0  227.75      .1       0
Bank Sta=191.53,227.75
XS Rating Curve= 0 ,0
Exp/Cntr=0.3,0.1

Type RM Length L Ch R = 1 ,1225.288,36.16,36.57,37.35
XS GIS Cut Line= 5
     625282.5966    4318114.1837     625401.1302    4318011.5252
     625433.9386    4317998.8252     625471.6418    4317992.7397
     625525.6169    4317972.8959
#Sta/Elev= 30
       0  643.89    6.03  641.35   12.06  639.35   33.17  633.86    39.2  631.35
   63.33  625.16   66.34  623.57   93.48  613.82    96.5  612.18   99.51  610.07
  114.59  605.44  126.65  604.21   135.7  604.59  168.54  604.36  180.26  604.09
  197.87  602.93  209.62  601.93  226.28  601.54  233.21  601.89  236.23  603.14
  242.29   607.5  245.31  611.26  248.34  614.18  263.47  625.82   266.5  628.44
  269.53  632.41  275.58  636.64  278.61  639.68  281.63  642.18  287.69  645.76
#Mann= 3 , 0 , 0
       0      .1       0  197.87      .1       0  236.23      .1       0
Bank Sta=197.87,236.23
XS Rating Curve= 0 ,0
Exp/Cntr=0.3,0.1

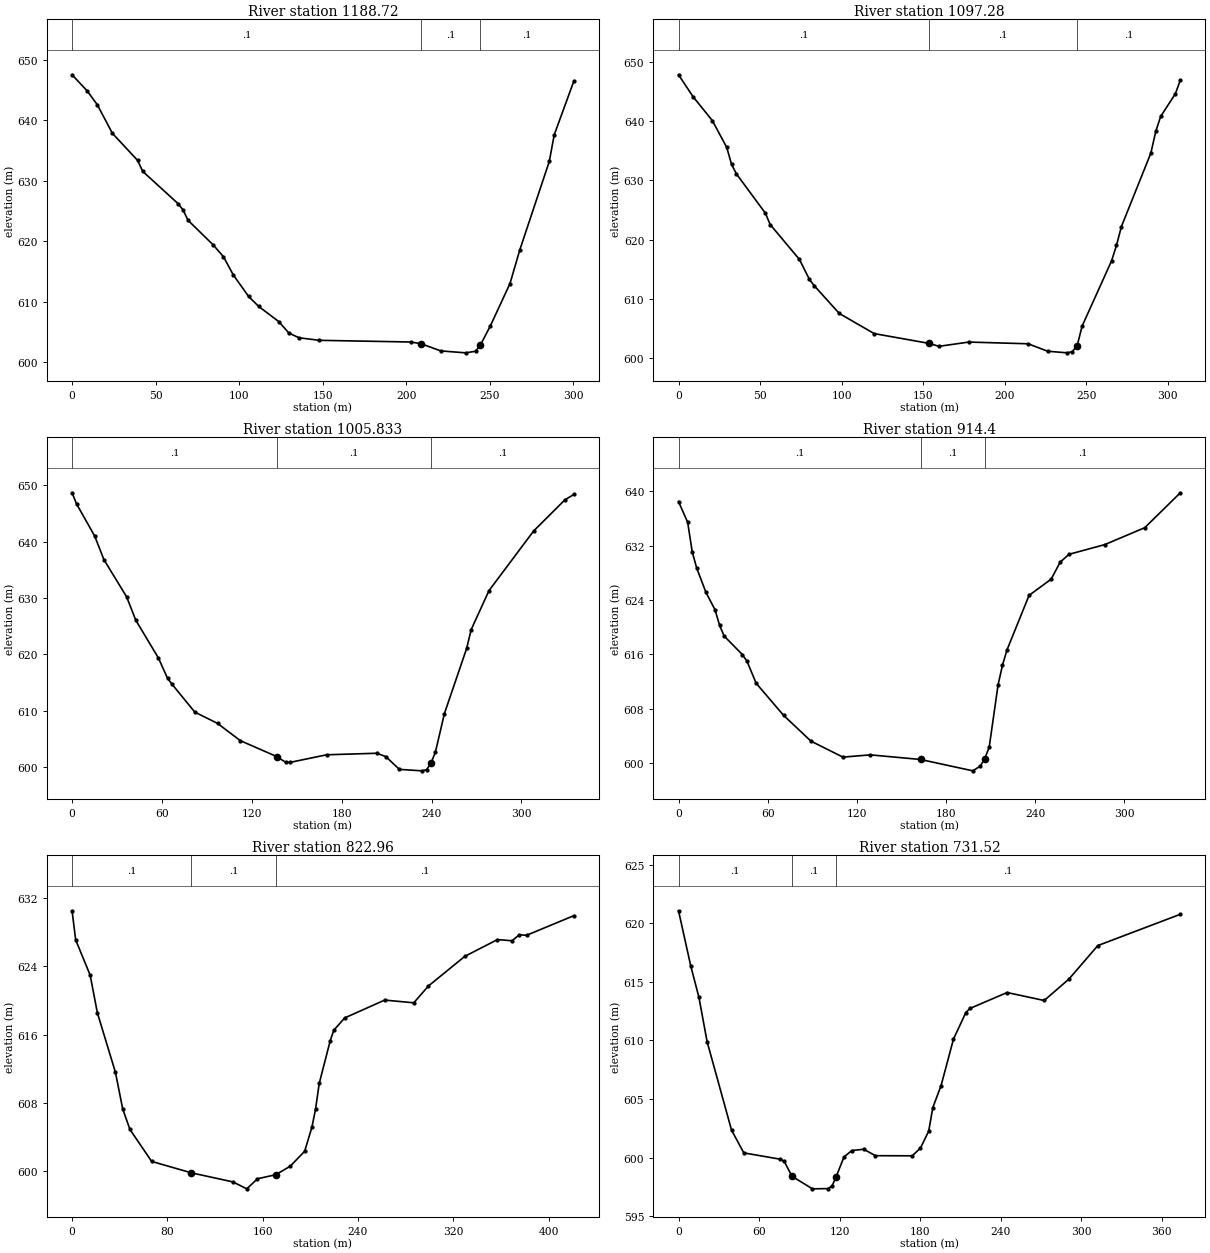
Type RM Length L Ch R = 1 ,1188.72 ,90.04,91.44,87.58
XS GIS Cut Line= 6
     625274.4516    4318143.8712     625402.5574    4318047.8879
     625446.7924    4318035.7924     625460.9844    4318031.4262
     625481.5981    4318028.4814     625537.9715    4318011.5604
#Sta/Elev= 30
       0  647.48    9.06  644.81    15.1  642.53   24.16   637.8   39.26  633.32
   42.28  631.52   63.43  626.19   66.45  625.14   69.47  623.42   84.57  619.34
   90.61  617.42   96.65  614.35  105.71  610.84  111.75  609.19  123.83  606.67
  129.87  604.78  135.91  604.01  147.99  603.59  202.88  603.31   208.9  603.03
  220.78  601.84  235.66  601.52   241.6  601.78  244.55  602.83  250.43  605.96
  262.21  612.97  268.09  618.53  285.75  633.16  288.69  637.54  300.46  646.44
#Mann= 3 , 0 , 0
       0      .1       0   208.9      .1       0  244.55      .1       0
Bank Sta=208.9,244.55
XS Rating Curve= 0 ,0
Exp/Cntr=0.3,0.1

Type RM Length L Ch R = 1 ,1097.28 ,76.49,91.45,99.82
XS GIS Cut Line= 4
     625274.4516    4318155.5129     625337.9333    4318131.0826
     625460.1435    4318129.1244     625570.9399    4318090.1702
#Sta/Elev= 30
       0  647.83    8.87  644.14    20.7   640.1   29.57  635.56   32.53  632.68
   35.49  631.09   53.23  624.46   56.19  622.53   74.13  616.64   80.24  613.27
    83.3  612.17   98.58  607.51  119.97  604.11  153.58  602.46  159.69  601.96
  178.02  602.68  214.34  602.39  226.38  601.13  238.43  600.86  241.44  601.07
  244.45  602.08  247.46  605.37  265.53   616.4  268.54  619.01  271.55  622.18
  289.62   634.6  292.63  638.27  295.65   640.8  304.68  644.63  307.69  646.94
#Mann= 3 , 0 , 0
       0      .1       0  153.58      .1       0  244.45      .1       0
Bank Sta=153.58,244.45
XS Rating Curve= 0 ,0
Exp/Cntr=0.3,0.1

Type RM Length L Ch R = 1 ,1005.833,76.02,91.43,90.99
XS GIS Cut Line= 4
     625276.5683    4318204.1963     625507.2277     4318206.589
     625519.1234    4318207.2127     625610.0977    4318223.4429
#Sta/Elev= 30
       0  648.66    3.04  646.66   15.18  640.94   21.25   636.8   36.42   630.2
   42.49  626.07   57.67  619.33   63.74  615.74   66.77  614.68   81.95  609.74
   97.12  607.74   112.3  604.68  136.58  601.86  142.65  600.83  145.69  600.83
  169.97  602.17  203.36  602.44  209.43  601.85  218.53  599.58  233.65  599.32
  236.63  599.51  239.61  600.68  242.58  602.67  248.55  609.46  263.45  621.07
  266.43  624.37  278.36  631.31  308.17  641.89  329.03  647.41  334.99  648.36
#Mann= 3 , 0 , 0
       0      .1       0  136.58      .1       0  239.61      .1       0
Bank Sta=136.58,239.61
XS Rating Curve= 0 ,0
Exp/Cntr=0.3,0.1

Type RM Length L Ch R = 1 ,914.4   ,85.91,91.44,94.83
XS GIS Cut Line= 6
     625301.9736    4318261.5207     625450.8626    4318283.8391
     625488.5328    4318297.1615      625501.073    4318295.9166
     625547.4068    4318307.1725     625632.9627    4318291.9941
#Sta/Elev= 30
       0  638.46    6.15  635.41    9.22  631.06   12.29  628.64   18.43  625.12
   24.58  622.54   27.65  620.24   30.72  618.68   43.01  615.95   46.09  614.97
   52.23  611.74   70.67  607.03    89.1  603.23  110.61  600.88  129.04  601.21
  162.85  600.53  198.07  598.86  203.11  599.57  206.09  600.67  209.07  602.34
  215.03  611.51  218.01  614.41  220.99  616.62  235.89  624.67  250.79  627.06
  256.78  629.55  262.78  630.71  286.75  632.13  313.71  634.62  337.68  639.76
#Mann= 3 , 0 , 0
       0      .1       0  162.85      .1       0  206.09      .1       0
Bank Sta=162.85,206.09
XS Rating Curve= 0 ,0
Exp/Cntr=0.3,0.1

Type RM Length L Ch R = 1 ,822.96  ,91.49,91.44,85.45
XS GIS Cut Line= 6
     625319.0338    4318352.3314     625433.3446    4318367.9227
     625455.5347    4318380.1568     625466.6716     4318384.346
     625512.3179    4318386.4905     625727.4192    4318327.9775
#Sta/Elev= 30
       0  630.49    3.04  627.08   15.18  622.96   21.25  618.54   36.43  611.57
    42.5   607.3   48.58   604.9   66.79  601.16  100.19  599.82  135.08  598.76
  146.66  597.95  155.65  599.13  170.89   599.6  183.07  600.59  195.26  602.35
  201.36  605.18  204.41  607.29  207.46  610.28  216.63  615.25  219.68  616.51
  228.84  617.95  262.43  620.04  286.86  619.72  299.07  621.68  329.61  625.15
  357.09  627.12  369.31  626.98  375.42  627.68  381.52  627.62  421.22  629.92
#Mann= 3 , 0 , 0
       0      .1       0  100.19      .1       0  170.89      .1       0
Bank Sta=100.19,170.89
XS Rating Curve= 0 ,0
Exp/Cntr=0.3,0.1

Type RM Length L Ch R = 1 ,731.52  ,16.1,14.37,19.34
XS GIS Cut Line= 6
     625350.3872    4318457.6887     625423.2975    4318457.6887
     625435.4949    4318465.5313     625447.3894    4318468.8617
     625500.1744    4318468.0528     625699.7022    4318372.5355
#Sta/Elev= 30
       0  621.07    9.11  616.35   15.19  613.68   21.27   609.9   39.49  602.34
   48.61   600.4   75.81  599.86   78.71  599.68   84.51   598.4   99.76  597.33
  111.49  597.35  114.43  597.59  117.36  598.35  123.23  600.05  129.09   600.6
  137.89  600.71  146.69  600.16  174.06  600.15  180.21  600.81  186.35  602.26
  189.42  604.27  195.57  606.15  204.79  610.11     214  612.38  217.07  612.73
  244.73  614.09  272.38  613.41  290.81  615.24  312.32   618.1  373.77  620.77
#Mann= 3 , 0 , 0
       0      .1       0   84.51      .1       0  117.36      .1       0
Bank Sta=84.51,117.36
XS Rating Curve= 0 ,0
Exp/Cntr=0.3,0.1

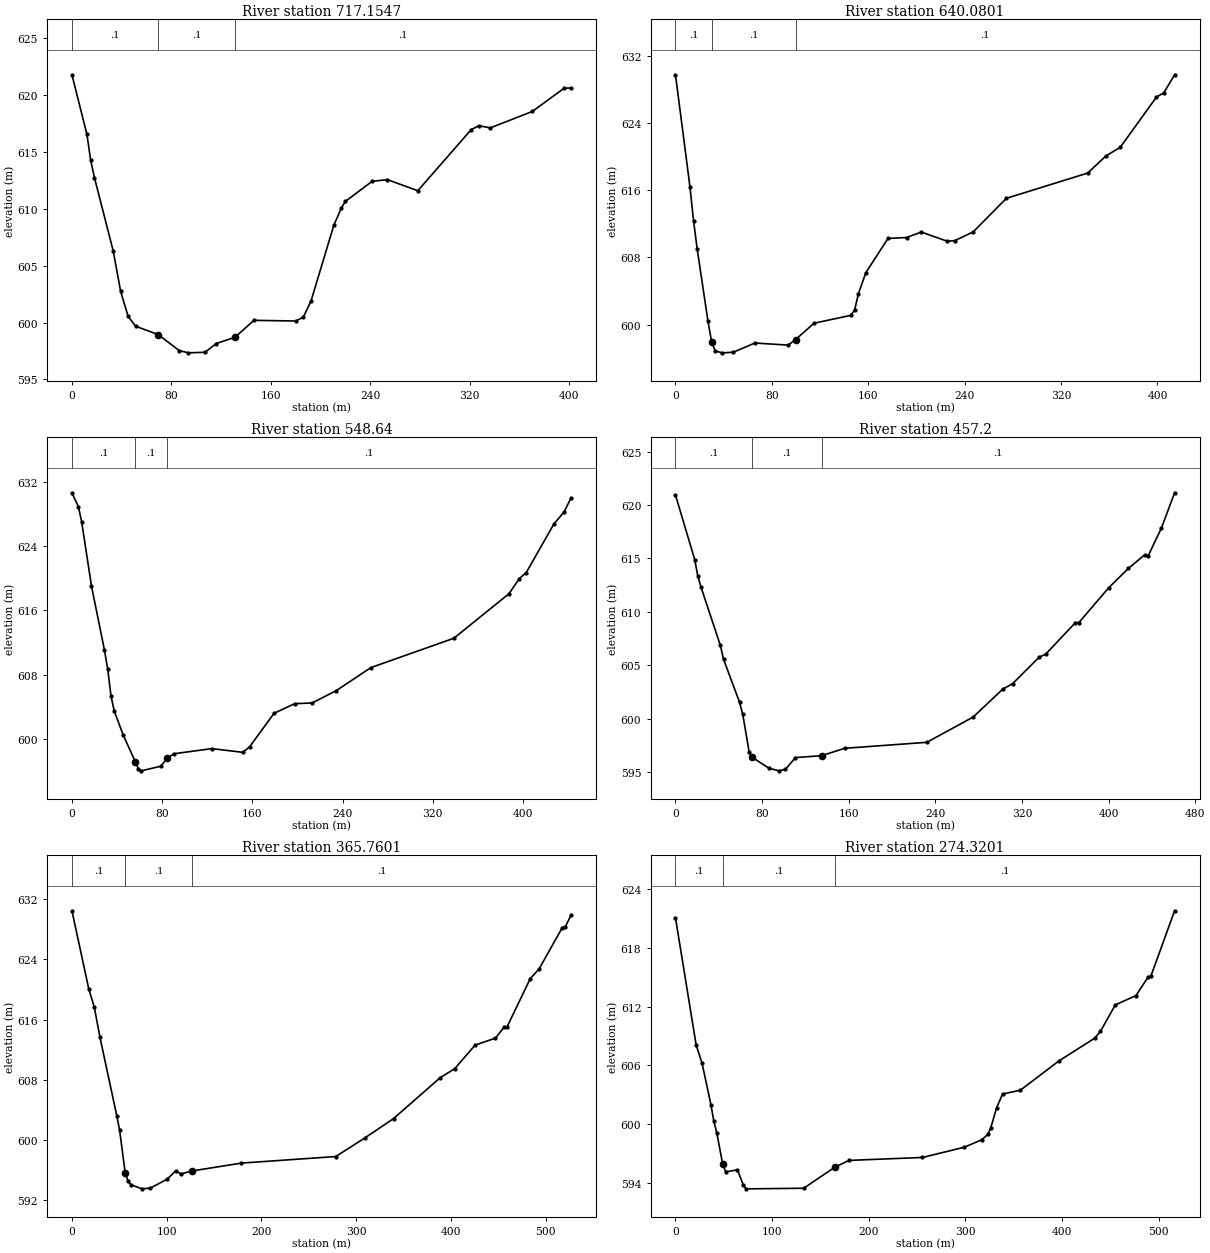
Type RM Length L Ch R = 1 ,717.1547,96.32,77.07,43.12
XS GIS Cut Line= 6
     625351.1699    4318475.0766     625420.5096    4318473.6542
     625454.2441    4318487.9417     625502.6629    4318487.5448
     625697.3152    4318382.8552     625715.0376    4318365.1312
#Sta/Elev= 30
       0   621.8   12.06  616.56   15.08  614.27   18.09  612.76   33.17  606.32
    39.2  602.74   45.23  600.54   51.26  599.68   69.35  598.95   86.28  597.54
   93.68  597.34  107.03  597.39  116.11  598.16  131.24  598.71  146.37   600.2
  180.01  600.14  186.15  600.48  192.28  601.88   210.7  608.57  216.84   610.1
  219.91  610.66   241.4  612.42  253.68  612.58  278.24   611.6  321.21  616.98
  327.35  617.32  336.56  617.13  370.33  618.57  395.96  620.62  401.53  620.64
#Mann= 3 , 0 , 0
       0      .1       0   69.35      .1       0  131.24      .1       0
Bank Sta=69.35,131.24
XS Rating Curve= 0 ,0
Exp/Cntr=0.3,0.1

Type RM Length L Ch R = 1 ,640.0801,99.69,91.44,85.87
XS GIS Cut Line= 4
     625425.4999    4318578.6165     625478.7041    4318534.8014
     625703.9101    4318385.5711     625748.0567    4318324.8025
#Sta/Elev= 30
       0  629.76   11.99  616.44   14.98  612.38   17.98  609.05   26.97  600.39
   29.97  597.96   32.96  596.85   38.96  596.63   47.95   596.7   65.93   597.8
   93.48  597.55   99.62   598.2  114.97  600.16  145.67   601.1  148.74  601.79
  151.81  603.66  157.95  606.18  176.37  610.26  191.72  610.37     204  611.02
  225.49  609.93  231.63  609.99  246.98  611.03  274.61  615.04  342.09  618.05
  357.11  620.08  369.13  621.12  399.17  627.11  405.18   627.6   414.2  629.75
#Mann= 3 , 0 , 0
       0      .1       0   29.97      .1       0   99.62      .1       0
Bank Sta=29.97,99.62
XS Rating Curve= 0 ,0
Exp/Cntr=0.3,0.1

Type RM Length L Ch R = 1 ,548.64  ,80,91.44,97.83
XS GIS Cut Line= 6
     625483.9979     4318659.514     625513.4599    4318636.2629
     625525.5866    4318612.6771     625543.6919    4318593.8928
     625724.0419    4318423.0583     625752.8192     4318323.215
#Sta/Elev= 30
       0   630.6    5.77  628.85    8.66  626.96   17.32  619.02   28.87  611.02
   31.76  608.66   34.64  605.34   37.53  603.46   45.46   600.5   56.09   597.2
   58.78  596.33   61.48  596.04   78.67  596.61   84.46  597.59   90.26  598.16
     124   598.8   151.6  598.34  157.73  599.06   179.2  603.19   197.6  604.39
  212.94  604.47   234.4  606.01  265.07  608.87  338.68  612.52  387.58  618.06
  396.74  619.94  402.86  620.68  427.31  626.71  436.47  628.23  442.59  629.96
#Mann= 3 , 0 , 0
       0      .1       0   56.09      .1       0   84.46      .1       0
Bank Sta=56.09,84.46
XS Rating Curve= 0 ,0
Exp/Cntr=0.3,0.1

Type RM Length L Ch R = 1 ,457.2   ,105.49,91.44,63.97
XS GIS Cut Line= 5
     625505.2567    4318720.5108     625568.7815    4318688.7121
     625608.6731    4318666.1462     625695.6691    4318585.9467
      625750.438    4318366.8713
#Sta/Elev= 30
       0  620.93   17.76  614.89   20.72  613.31   23.68  612.28   41.44  606.86
    44.4  605.56    59.2  601.52   62.16  600.39   68.08  596.86   71.04  596.36
   86.32  595.36   95.48  595.11  101.59  595.25  110.76  596.35  135.07  596.53
  156.31  597.22  232.16  597.78  274.86  600.14  302.33  602.76  311.48  603.28
   335.9  605.75     342  606.04  369.46  608.99  372.52  608.98  399.98  612.23
  418.29  614.06  433.55  615.34   436.6  615.24  448.81  617.83  461.01  621.14
#Mann= 3 , 0 , 0
       0      .1       0   71.04      .1       0  135.07      .1       0
Bank Sta=71.04,135.07
XS Rating Curve= 0 ,0
Exp/Cntr=0.3,0.1

Type RM Length L Ch R = 1 ,365.7601,95.2,91.44,89.18
XS GIS Cut Line= 6
      625601.116    4318817.3996     625640.5475    4318754.8517
     625666.9398    4318702.0673     625673.5489    4318671.9305
     625730.7265    4318555.5196     625758.2432    4318323.7441
#Sta/Elev= 30
       0  630.46   17.75  620.09   23.66  617.63   29.58  613.65   47.32  603.24
   50.28  601.35   56.19  595.68   59.15  594.57   62.11  594.08   73.94  593.52
   82.79  593.62   100.5   594.8  109.35  595.89  115.25  595.51  127.05   595.9
  178.89  596.94  278.42  597.81  308.86  600.25  339.57  602.86  388.71  608.28
  404.06  609.48  425.56  612.61  447.06  613.54  456.27     615  459.34  615.04
  483.91  621.46  493.12  622.73  517.69  628.23  520.76  628.33  526.91  629.88
#Mann= 3 , 0 , 0
       0      .1       0   56.19      .1       0  127.05      .1       0
Bank Sta=56.19,127.05
XS Rating Curve= 0 ,0
Exp/Cntr=0.3,0.1

Type RM Length L Ch R = 1 ,274.3201,86.44,91.44,111.91
XS GIS Cut Line= 5
     625696.8597    4318870.9035     625717.6956    4318807.0015
      625753.012     4318728.351     625760.1326    4318688.2426
     625757.1849    4318366.0775
#Sta/Elev= 30
       0  621.09   21.39  608.08    27.5  606.21   36.66  601.98   39.72  600.25
   42.77  599.08   48.88  595.87   51.94   595.1   64.16   595.3   70.19  593.74
   73.16  593.36  132.62  593.42  165.07  595.59  179.62  596.27  255.53  596.57
  298.49  597.61   316.9  598.38  323.04  598.93   326.1  599.58  332.24  601.66
  338.38  603.06  356.79  603.45  396.68  606.45   433.5  608.76  439.63  609.47
  454.98  612.18  476.45  613.14  488.73     615   491.8  615.12  516.34  621.81
#Mann= 3 , 0 , 0
       0      .1       0   48.88      .1       0  165.07      .1       0
Bank Sta=48.88,165.07
XS Rating Curve= 0 ,0
Exp/Cntr=0.3,0.1