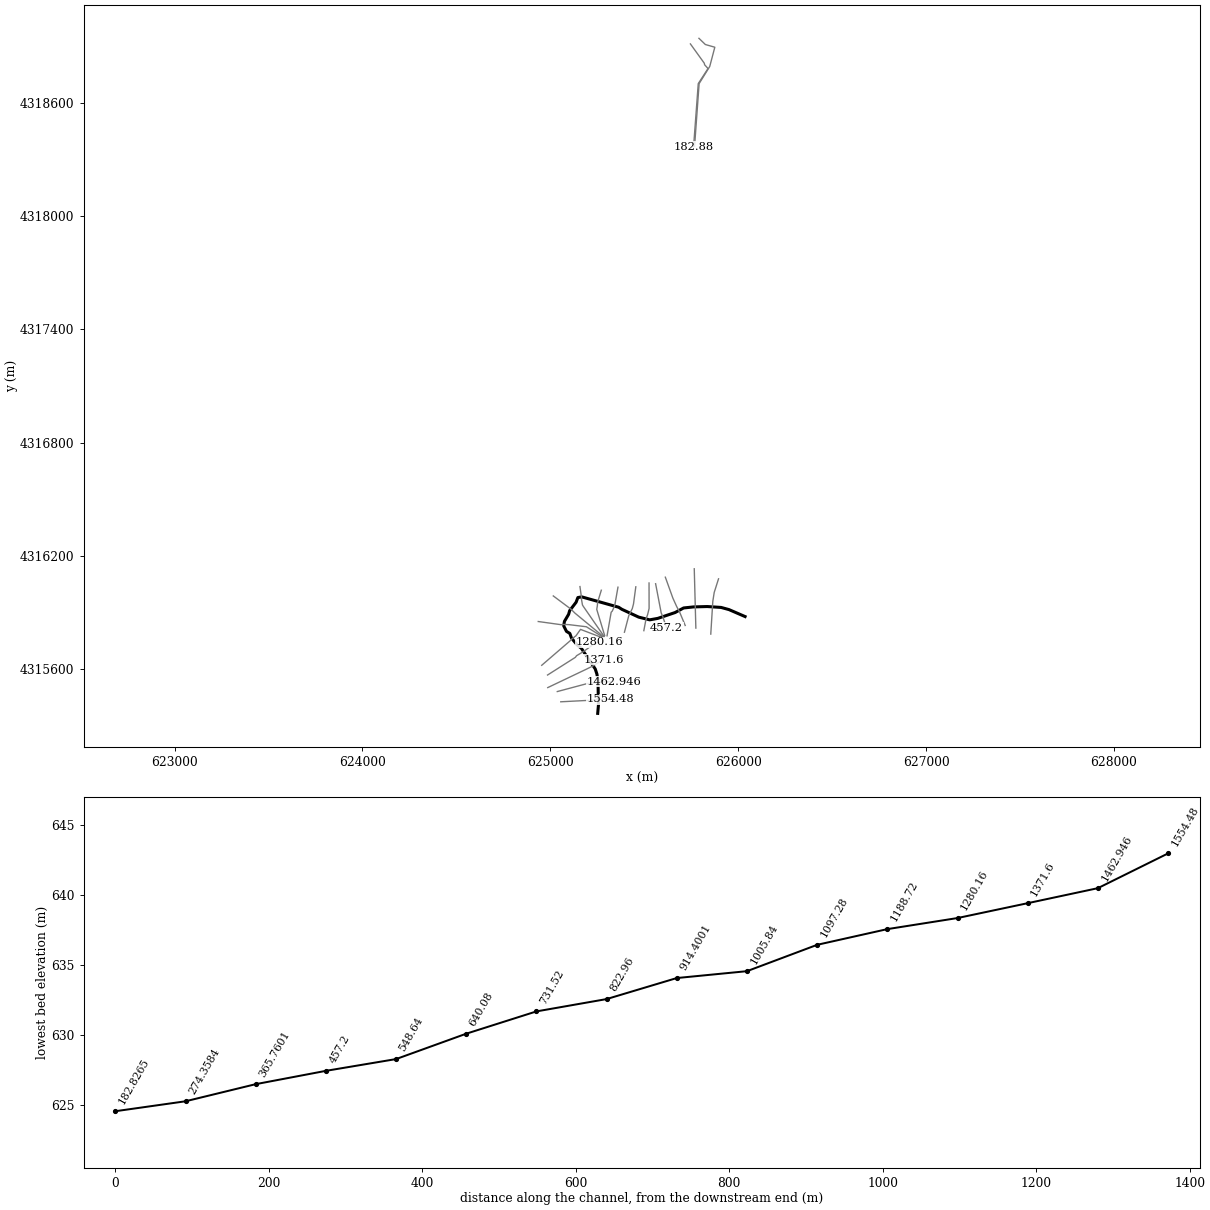
HEC-RAS study RedCreek.prj: RedCreek

--- RedCreek.g01 (geometry) --- (continued)

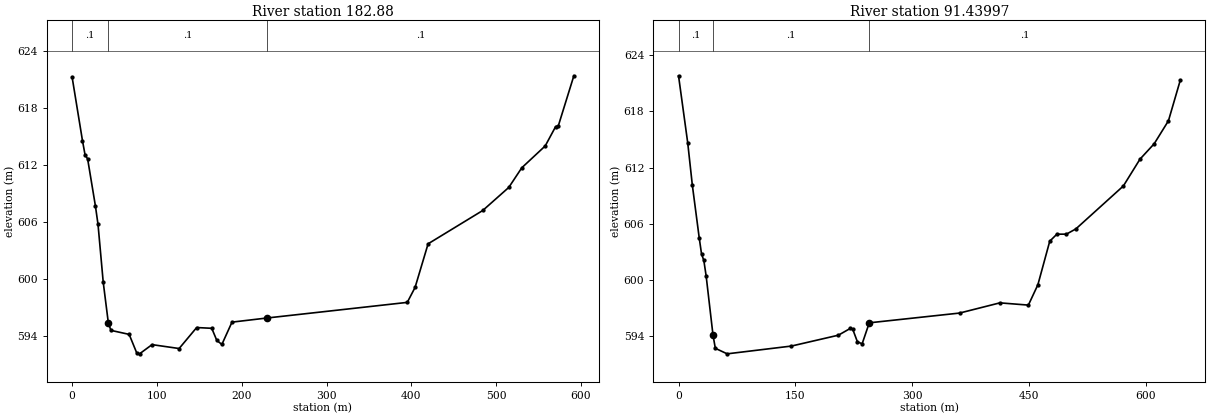
Type RM Length L Ch R = 1 ,182.88  ,78.06,91.44,116.01
XS GIS Cut Line= 6
     625745.5432     4318913.237     625819.3593    4318811.0612
     625821.3606    4318802.4591     625839.3523     4318782.774
     625787.3263    4318702.8168     625762.4765    4318369.2525
#Sta/Elev= 30
       0   621.3   12.24  614.59    15.3  613.09   18.36  612.65   27.54  607.69
    30.6  605.75   36.71  599.68   42.83  595.33   45.89  594.59   67.31  594.17
   76.49  592.16   79.55  592.12    94.3  593.09  126.21  592.68   146.9  594.89
   164.7  594.81  170.66  593.53  176.62  593.11  188.54  595.46  230.28   595.9
   395.2  597.54  404.41  599.12  419.75  603.71  484.19  607.22  514.88  609.65
  530.22  611.72  557.84  614.02  570.12  616.06  573.18  616.11   591.6  621.41
#Mann= 3 , 0 , 0
       0      .1       0   42.83      .1       0  230.28      .1       0
Bank Sta=42.83,230.28
XS Rating Curve= 0 ,0
Exp/Cntr=0.3,0.1

Type RM Length L Ch R = 1 ,91.43997,105.53,91.44,44.57
XS GIS Cut Line= 6
     625791.0516    4318942.8704     625825.1331    4318910.0968
     625875.4804    4318895.7434     625848.4165    4318793.6799
     625791.9543    4318702.9541     625767.7682    4318371.3692
#Sta/Elev= 30
       0  621.79   11.82  614.62   17.73  610.12    26.6  604.48   29.55  602.78
   32.51  602.08   35.46  600.44   44.33  594.09   47.28  592.71   62.48  592.12
  145.02  592.95  205.36  594.11  220.62  594.83  223.68  594.77  229.78  593.41
  235.89  593.19  245.05  595.43  361.02  596.47  412.87  597.56  449.47  597.32
  461.67  599.49  476.93  604.14  486.08  604.89  498.28  604.89  510.48  605.45
  571.48  610.03  592.83  612.89  611.13  614.54  629.43  616.99  644.68  621.33
#Mann= 3 , 0 , 0
       0      .1       0   44.33      .1       0  245.05      .1       0
Bank Sta=44.33,245.05
XS Rating Curve= 0 ,0
Exp/Cntr=0.3,0.1

River Reach=Laurel Fork     ,1
Reach XY= 30
     625252.2188    4315364.4723     625256.0704    4315406.9707
     625253.8637    4315533.4034     625248.0989    4315572.3343
     625239.1219    4315599.8197     625164.9061    4315709.7543
     625144.3829    4315725.6619      625123.631    4315750.2356
     625112.1216    4315765.3169     625103.7872    4315788.3357
     625086.0422     4315799.084     625071.2315    4315828.3569
     625075.2122    4315852.2327     625097.3627    4315889.5139
     625102.9935    4315908.9859     625137.1248     4315953.436
     625146.6498    4315978.4392     625167.2874    4315982.0111
     625363.6864    4315927.0667     625380.8065    4315916.1297
     625470.6437    4315874.5743     625528.8624    4315860.2854
     625571.9731    4315868.0096     625664.1759     4315899.064
     625709.4197    4315923.2735     625762.6011    4315928.8297
     625835.2293    4315930.8141     625908.7657    4315926.0842
     625950.8345    4315914.5748     626036.5238    4315877.6759

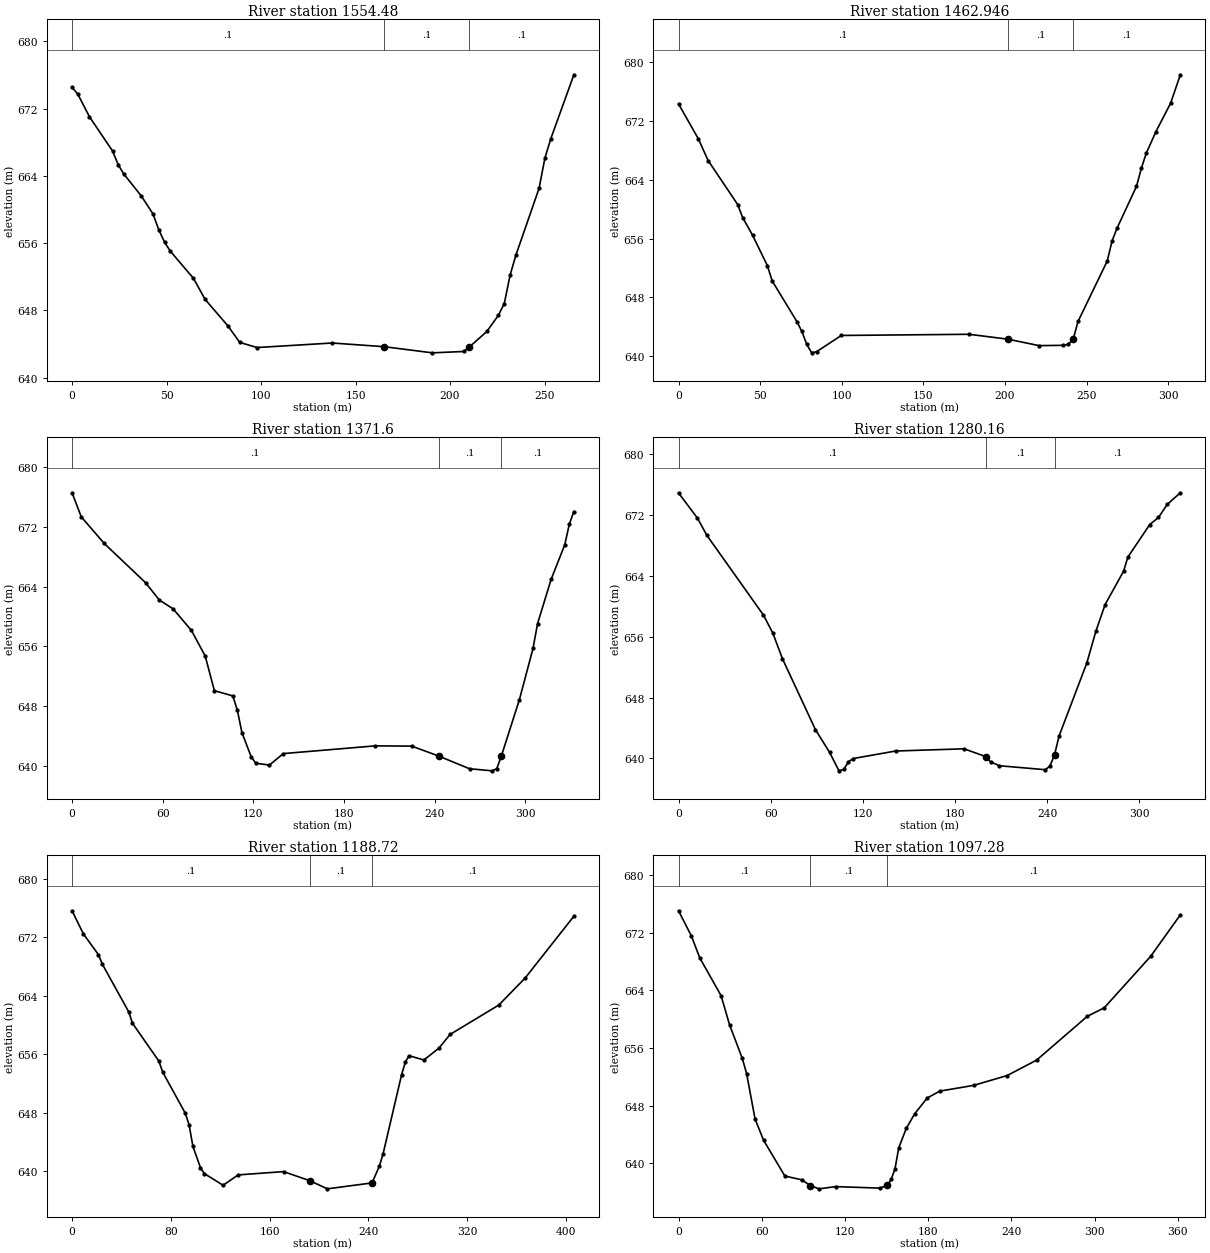
Type RM Length L Ch R = 1 ,1554.48 ,89.42,91.53,91.67
XS GIS Cut Line= 5
     625055.6435    4315425.8673     625238.9566    4315435.3126
     625247.6689    4315438.8809     625258.8129    4315439.4163
      625320.194    4315440.2452
#Sta/Elev= 30
       0  674.54    3.06  673.73    9.18  671.05   21.41  666.98   24.47  665.31
   27.53  664.19   36.71   661.6   42.83  659.48   45.89   657.6   48.95  656.12
   52.01  655.05   64.24  651.82   70.36  649.33    82.6  646.13   88.72   644.2
    97.9  643.59  137.67  644.13   165.2  643.69  190.62  642.96   207.2  643.12
  210.27  643.67  219.47   645.5  225.61  647.44  228.68  648.81  231.75  652.18
  234.82  654.57   247.1  662.53  250.17  666.11  253.24  668.39  265.51  676.04
#Mann= 3 , 0 , 0
       0      .1       0   165.2      .1       0  210.27      .1       0
Bank Sta=165.2,210.27
XS Rating Curve= 0 ,0
Exp/Cntr=0.3,0.1

Type RM Length L Ch R = 1 ,1462.946,75.17,91.35,95.92
XS GIS Cut Line= 5
     625037.1226     4315480.107     625194.8063    4315522.0555
     625242.0081    4315526.2889     625247.9317      4315530.57
     625337.4253    4315533.0238
#Sta/Elev= 30
       0  674.29   12.09  669.57   18.13   666.6   36.26  660.62   39.28  658.85
   45.32  656.47   54.39  652.34   57.41  650.23   72.52  644.72   75.54  643.39
   78.56  641.62   81.58  640.48   84.61  640.64   99.71  642.84  177.98     643
  201.67  642.34  220.85  641.46  235.77   641.5  238.76  641.63  241.74  642.31
  244.73  644.74  262.63  652.96  265.62   655.7   268.6   657.4  280.54  663.09
  283.52  665.54  286.51  667.58  292.47  670.54  301.43  674.38   307.4  678.25
#Mann= 3 , 0 , 0
       0      .1       0  201.67      .1       0  241.74      .1       0
Bank Sta=201.67,241.74
XS Rating Curve= 0 ,0
Exp/Cntr=0.3,0.1

Type RM Length L Ch R = 1 ,1371.6  ,86.43,91.44,92.6
XS GIS Cut Line= 4
     624986.3225    4315501.0973     625192.1607    4315598.8362
     625223.6964     4315614.403     625283.1057    4315649.5636
#Sta/Elev= 30
       0  676.51    6.08   673.3   21.27  669.75   48.61  664.52   57.73   662.2
   66.84  661.03   78.99  658.14   88.11  654.73   94.18   650.1  106.34  649.41
  109.37  647.51  112.41  644.51  118.49  641.31  121.53  640.42  130.64  640.18
  139.76  641.71  200.52  642.74  224.83  642.71  242.52  641.39  263.03  639.69
  278.04  639.41  281.04   639.7  284.04  641.35  296.05  648.92  305.05  655.75
  308.06  659.06  317.06  664.98  326.06  669.58  329.07  672.33  332.07  673.99
#Mann= 3 , 0 , 0
       0      .1       0  242.52      .1       0  284.04      .1       0
Bank Sta=242.52,284.04
XS Rating Curve= 0 ,0
Exp/Cntr=0.3,0.1

Type RM Length L Ch R = 1 ,1280.16 ,86.96,91.44,105.7
XS GIS Cut Line= 6
     624985.2642    4315567.7725     625133.2951    4315661.5058
     625139.6274    4315670.1034     625174.7541    4315691.0937
     625225.9841    4315727.6547     625259.9022    4315742.3978
#Sta/Elev= 30
       0  674.94    12.3  671.63   18.44  669.36   55.33  658.85   61.48  656.45
   67.63  653.13   89.14  643.78   98.36  640.78  104.51  638.35  107.59  638.53
  110.66  639.54  113.73  639.97   141.4  640.96  185.89  641.25  200.34  640.21
  203.23  639.53  209.01  639.02  238.85   638.5  241.84  638.98  244.84  640.45
  247.84  642.95  265.82  652.51  271.81  656.74  277.81  660.25   289.8  664.62
  292.64   666.5  306.87  670.78  312.56  671.71  318.25  673.43  326.78  674.96
#Mann= 3 , 0 , 0
       0      .1       0  200.34      .1       0  244.84      .1       0
Bank Sta=200.34,244.84
XS Rating Curve= 0 ,0
Exp/Cntr=0.3,0.1

Type RM Length L Ch R = 1 ,1188.72 ,116.86,91.44,83.57
XS GIS Cut Line= 6
     624954.3079    4315619.3663     625105.1301    4315748.9097
     625114.2055    4315758.6406     625136.3929    4315775.5731
     625160.6833    4315809.7344     625277.1002    4315765.4166
#Sta/Elev= 30
       0  675.65    9.18  672.48   21.41  669.63   24.47  668.35   45.88  661.81
   48.94  660.24   70.35  655.05   73.41  653.55   91.76  647.91   94.82  646.32
   97.88  643.38     104  640.48  107.06  639.66  122.35  638.05  134.58  639.47
  171.29  639.92   192.7  638.67   206.8  637.56  243.03  638.37  249.02   640.7
  252.01  642.39  266.98   653.2  269.98  654.92  272.97   655.8  284.99  655.21
  297.14  656.82  306.26  658.71  345.75  662.74  367.02  666.43  406.52   674.9
#Mann= 3 , 0 , 0
       0      .1       0   192.7      .1       0  243.03      .1       0
Bank Sta=192.7,243.03
XS Rating Curve= 0 ,0
Exp/Cntr=0.3,0.1

Type RM Length L Ch R = 1 ,1097.28 ,108.84,91.44,82.17
XS GIS Cut Line= 6
      624935.787    4315851.4064     625057.2734    4315834.5687
     625067.8937    4315835.7821     625098.6147    4315834.8995
     625191.8805    4315823.6547      625279.746    4315768.7239
#Sta/Elev= 30
       0  675.07     9.2   671.6   15.33  668.52   30.66  663.28   36.79  659.23
   45.99  654.55   49.06  652.46   55.19  646.13   61.32  643.19   76.65  638.22
   88.92  637.69   95.05  636.89  101.18  636.44  113.45  636.75  145.19  636.54
  150.62  636.93  153.33  637.77  156.05  639.21  158.76  642.14  164.19  644.84
  170.25  646.87  179.34  649.07  188.43  650.02  212.68  650.81  236.92  652.18
  258.13  654.32  294.71  660.41   306.9  661.59  340.42  668.75  361.76   674.5
#Mann= 3 , 0 , 0
       0      .1       0   95.05      .1       0  150.62      .1       0
Bank Sta=95.05,150.62
XS Rating Curve= 0 ,0
Exp/Cntr=0.3,0.1

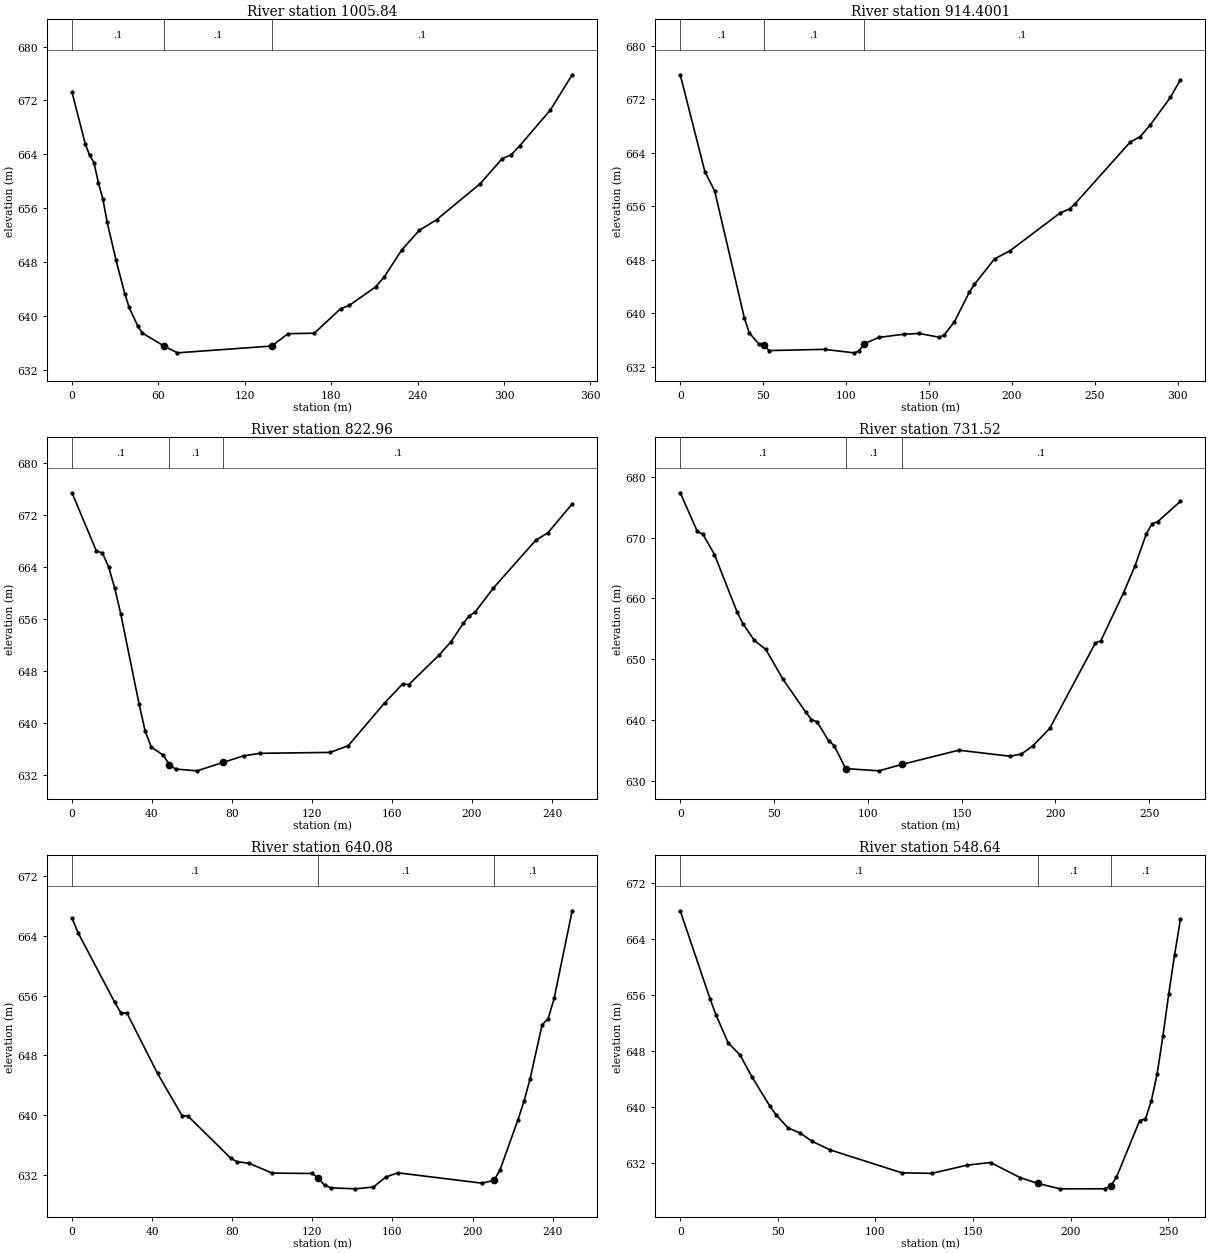
Type RM Length L Ch R = 1 ,1005.84 ,101.1,91.44,59.14
XS GIS Cut Line= 5
     625015.8236    4315987.0056     625106.4285    4315919.5921
     625111.1387    4315915.7207     625131.0262    4315896.0018
     625285.6992    4315768.7239
#Sta/Elev= 30
       0  673.25    9.16  665.61   12.21  663.87   15.26  662.79   18.31   659.8
   21.37  657.44   24.42  653.94   30.52  648.37   36.63  643.35   39.68  641.32
   45.78  638.48   48.84   637.5    64.1  635.54   73.25  634.56  138.63  635.57
  150.07   637.4  168.28  637.47  186.49   641.1  192.56  641.59  210.77  644.33
  216.84  645.82  228.98  649.82  241.12  652.72  253.26  654.32  283.61  659.68
  298.78  663.38  304.85  663.91  310.92  665.28  332.17  670.57  347.34  675.81
#Mann= 3 , 0 , 0
       0      .1       0    64.1      .1       0  138.63      .1       0
Bank Sta=64.1,138.63
XS Rating Curve= 0 ,0
Exp/Cntr=0.3,0.1

Type RM Length L Ch R = 1 ,914.4001,96.06,91.44,77.14
XS GIS Cut Line= 6
     625157.7466    4316036.6657     625165.8209    4315978.8143
     625166.0791    4315967.7922     625171.1432    4315938.9127
     625175.8688    4315931.2797     625286.3606    4315772.0312
#Sta/Elev= 30
       0  675.67   14.86  661.18    20.8  658.27   38.64  639.31   41.61  637.06
   47.55  635.35   50.52  635.26    53.5  634.41   87.03  634.59  104.75  634.07
  107.74  634.31  110.77  635.41  119.85  636.38  134.99  636.86  144.08  636.97
  156.19   636.4  159.22  636.75  165.28  638.72  174.37  643.18  177.39  644.32
  189.51  648.13  198.59   649.3  228.88  654.97  234.94  655.63  237.96  656.35
  271.28   665.6  277.34  666.42  283.39  668.17  295.51  672.28  301.56  674.91
#Mann= 3 , 0 , 0
       0      .1       0   50.52      .1       0  110.77      .1       0
Bank Sta=50.52,110.77
XS Rating Curve= 0 ,0
Exp/Cntr=0.3,0.1

Type RM Length L Ch R = 1 ,822.96  ,90.98,91.44,82.31
XS GIS Cut Line= 6
     625271.4126    4316017.4183     625255.2538    4315965.0438
     625251.4279    4315950.1226     625250.2565     4315934.609
     625247.0815    4315915.8236     625289.3151    4315776.8378
#Sta/Elev= 30
       0  675.42   12.18  666.46   15.23  666.13   18.27  664.03   21.32  660.77
   24.36   656.8    33.5  642.93   36.54  638.76   39.59  636.26   45.68  634.97
    48.7  633.51   51.77  632.85   62.51  632.57   75.55  633.87   85.77  634.88
   93.94  635.27  129.03  635.41  138.11  636.44  156.27  643.02  165.35  645.97
  168.38  645.86  183.51   650.4  189.56  652.49  195.61  655.29  198.64  656.44
  201.66  657.09  210.74  660.76  231.93  668.13  237.98  669.26  250.08   673.7
#Mann= 3 , 0 , 0
       0      .1       0    48.7      .1       0   75.55      .1       0
Bank Sta=48.7,75.55
XS Rating Curve= 0 ,0
Exp/Cntr=0.3,0.1

Type RM Length L Ch R = 1 ,731.52  ,96.22,91.44,95.43
XS GIS Cut Line= 6
     625360.0412    4316033.5087     625343.6379    4315940.6784
     625340.7243    4315930.7635     625329.4024    4315906.1909
     625323.8461    4315900.7934     625301.8829    4315775.5149
#Sta/Elev= 30
       0  677.35    9.12     671   12.16  670.51   18.25  667.21   30.41   657.7
   33.45  655.83   39.53  653.11   45.61  651.63   54.74  646.75    66.9  641.33
   69.94  640.12   72.98  639.73   79.06  636.66    82.1  635.81   88.19  632.06
  105.97  631.69  118.08  632.74  148.54  635.08  175.79  634.09  181.85  634.45
  187.91  635.76  196.99  638.67  221.22  652.63  224.25  653.06  236.36  660.96
  242.42  665.34  248.47  670.61   251.5  672.25  254.53   672.6  266.64  675.95
#Mann= 3 , 0 , 0
       0      .1       0   88.19      .1       0  118.08      .1       0
Bank Sta=88.19,118.08
XS Rating Curve= 0 ,0
Exp/Cntr=0.3,0.1

Type RM Length L Ch R = 1 ,640.08  ,86.69,91.44,94.47
XS GIS Cut Line= 5
     625454.9822    4316035.4277     625442.7236    4315944.7143
     625436.3375    4315920.1292     625417.3311    4315881.8042
     625394.4872    4315794.6972
#Sta/Elev= 30
       0  666.41    3.05  664.44   21.36   655.1   24.41   653.7   27.46  653.65
   42.72  645.58   54.92  639.93   57.97  639.85   79.33  634.19   82.38  633.75
   88.49  633.52     100  632.21  119.99  632.16  123.05   631.5  126.11  630.59
  129.16  630.24  141.38   630.1  150.55  630.34  156.66  631.68  162.72  632.25
  204.74  630.86  210.75  631.23  213.75  632.65  222.75  639.39  225.76  641.89
  228.76  644.85  234.76   652.1  237.76  652.91  240.77  655.64  249.77  667.39
#Mann= 3 , 0 , 0
       0      .1       0  123.05      .1       0  210.75      .1       0
Bank Sta=123.05,210.75
XS Rating Curve= 0 ,0
Exp/Cntr=0.3,0.1

Type RM Length L Ch R = 1 ,548.64  ,65.94,91.44,98.23
XS GIS Cut Line= 6
     625525.4061    4316055.7073     625525.7294    4315920.7312
     625517.9647    4315888.6887     625510.8157     4315868.483
     625507.6795    4315855.7049      625497.719    4315802.9434
#Sta/Elev= 30
       0  667.99   15.34  655.36   18.41  653.06   24.54  649.15   30.68  647.38
   36.81  644.24   46.01  640.07   49.08  638.87   55.22  636.99   61.35  636.27
   67.49  635.09   76.69  633.86   113.5  630.58  128.84   630.5  146.97  631.67
  158.95  632.05  174.07   629.9  183.26  629.06  194.64  628.29  217.45   628.3
  220.43  628.66  223.42  629.91  235.35  638.03  238.33  638.27  241.32  640.85
   244.3  644.67  247.28  650.12  250.26  656.13  253.25   661.7  256.23  666.75
#Mann= 3 , 0 , 0
       0      .1       0  183.26      .1       0  220.43      .1       0
Bank Sta=183.26,220.43
XS Rating Curve= 0 ,0
Exp/Cntr=0.3,0.1

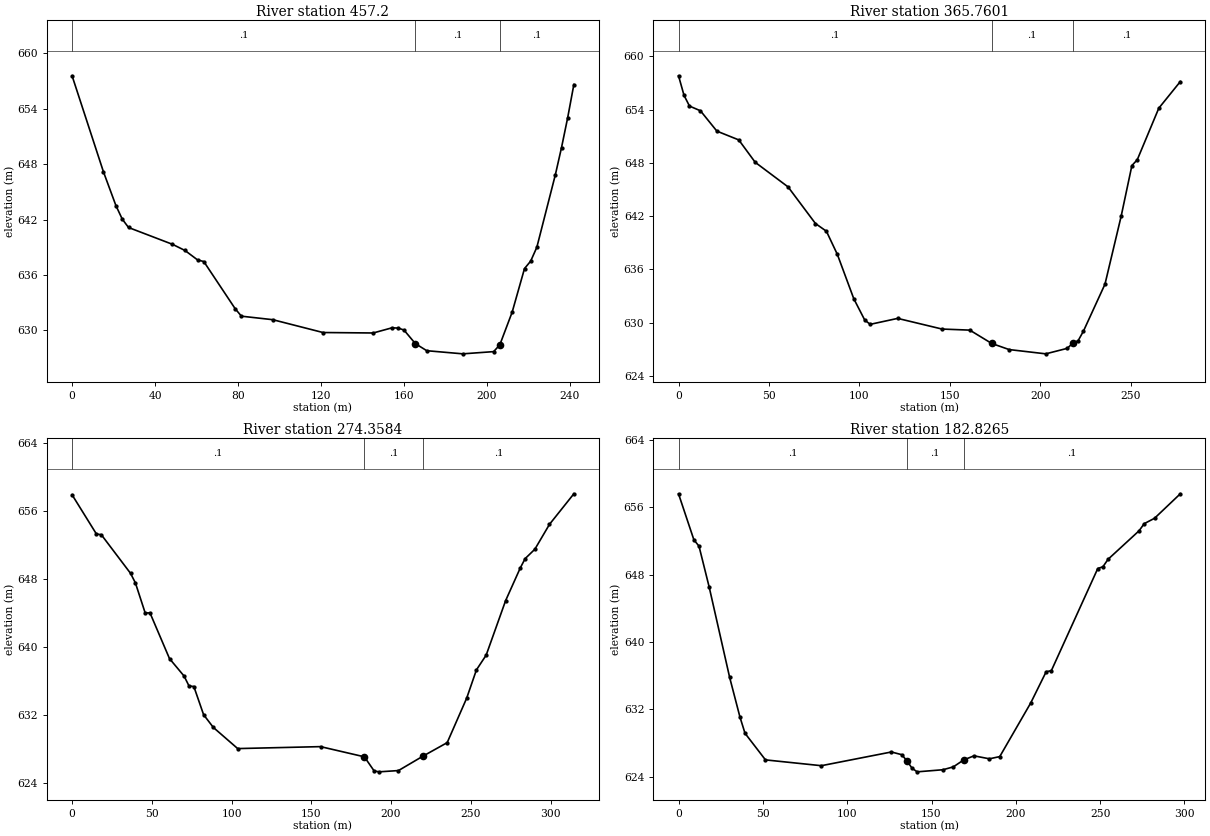
Type RM Length L Ch R = 1 ,457.2   ,85.9,91.44,92.82
XS GIS Cut Line= 4
     625560.3645    4316051.8035     625590.0241    4315897.3274
     625597.7439    4315879.7254     625618.6362    4315817.6946
#Sta/Elev= 30
       0  657.58   15.12  647.18   21.17   643.5    24.2  642.05   27.22  641.14
    48.4  639.32   54.45  638.65    60.5  637.63   63.52  637.45   78.65  632.34
   81.67  631.53    96.8  631.15     121  629.76   145.2  629.71  154.27  630.27
   157.3  630.24  160.04  630.03  165.53  628.56  171.03  627.79  188.42  627.45
  203.29  627.69  206.27  628.43  212.22  631.97  218.17  636.69  221.15   637.5
  224.12     639  233.05  646.86  236.02   649.8     239  653.05  241.97  656.63
#Mann= 3 , 0 , 0
       0      .1       0  165.53      .1       0  206.27      .1       0
Bank Sta=165.53,206.27
XS Rating Curve= 0 ,0
Exp/Cntr=0.3,0.1

Type RM Length L Ch R = 1 ,365.7601,109.44,91.4,86.47
XS GIS Cut Line= 5
     625612.1053    4316086.4542     625652.2454    4315975.4546
     625672.4984    4315930.7987     625688.0211    4315901.7891
     625717.8622    4315830.4626
#Sta/Elev= 30
       0   657.8    3.03   655.6    6.05  654.39   12.11  653.86   21.19  651.57
   33.29  650.58   42.37  648.06   60.53  645.29   75.66  641.17   81.72   640.3
   87.77  637.69   96.85   632.7   102.9   630.3  105.93  629.82   121.1  630.49
  145.62  629.29  160.94  629.17  173.05  627.67   182.7  626.98  202.94   626.5
  214.84  627.12  217.81   627.7  220.79  627.97  223.76  629.06  235.65  634.34
  244.58  641.98  250.52  647.69   253.5  648.35  265.39  654.15  277.29  657.15
#Mann= 3 , 0 , 0
       0      .1       0  173.05      .1       0  217.81      .1       0
Bank Sta=173.05,217.81
XS Rating Curve= 0 ,0
Exp/Cntr=0.3,0.1

Type RM Length L Ch R = 1 ,274.3584,97.12,91.53,92.13
XS GIS Cut Line= 2
     625766.0465    4316130.9913     625774.5796    4315816.4901
#Sta/Elev= 30
       0  657.92   15.27   653.3   18.33  653.22   36.65  648.67   39.71  647.54
   45.82  644.01   48.87     644   61.09  638.62   70.25  636.56   73.31   635.4
   76.36  635.33   82.47  632.01   88.58  630.51  103.85  628.02  155.78  628.25
  183.27  627.05  189.38  625.39  192.44  625.28  204.65  625.43  219.93  627.12
   235.2  628.72  247.42  633.96  253.53  637.29  259.64  639.03  271.85  645.46
  281.02   649.3  284.07   650.4  290.18  651.51  299.34  654.44  314.62  658.04
#Mann= 3 , 0 , 0
       0      .1       0  183.27      .1       0  219.93      .1       0
Bank Sta=183.27,219.93
XS Rating Curve= 0 ,0
Exp/Cntr=0.3,0.1

Type RM Length L Ch R = 1 ,182.8265,101.41,91.39,86.61
XS GIS Cut Line= 4
     625895.2615    4316077.7804     625872.2427     4316005.549
     625864.8362    4315958.7856     625853.9547      4315784.74
#Sta/Elev= 30
       0   657.6     9.1  652.14   12.13  651.39   18.19  646.51   30.32  635.78
   36.39   631.1   39.42  629.15   51.55  625.99   84.69   625.3  126.22  626.93
  132.34  626.61  135.39  625.89  138.45     625  141.51  624.57  156.81  624.82
  162.93  625.16  169.05  625.98  175.17  626.47  184.34  626.12  190.46  626.38
  208.82  632.75     218  636.47  221.06  636.59  248.59  648.73  251.65  648.94
  254.71  649.83  273.07  653.21  276.13  654.06  282.25   654.7  297.54  657.61
#Mann= 3 , 0 , 0
       0      .1       0  135.39      .1       0  169.05      .1       0
Bank Sta=135.39,169.05
XS Rating Curve= 0 ,0
Exp/Cntr=0.3,0.1