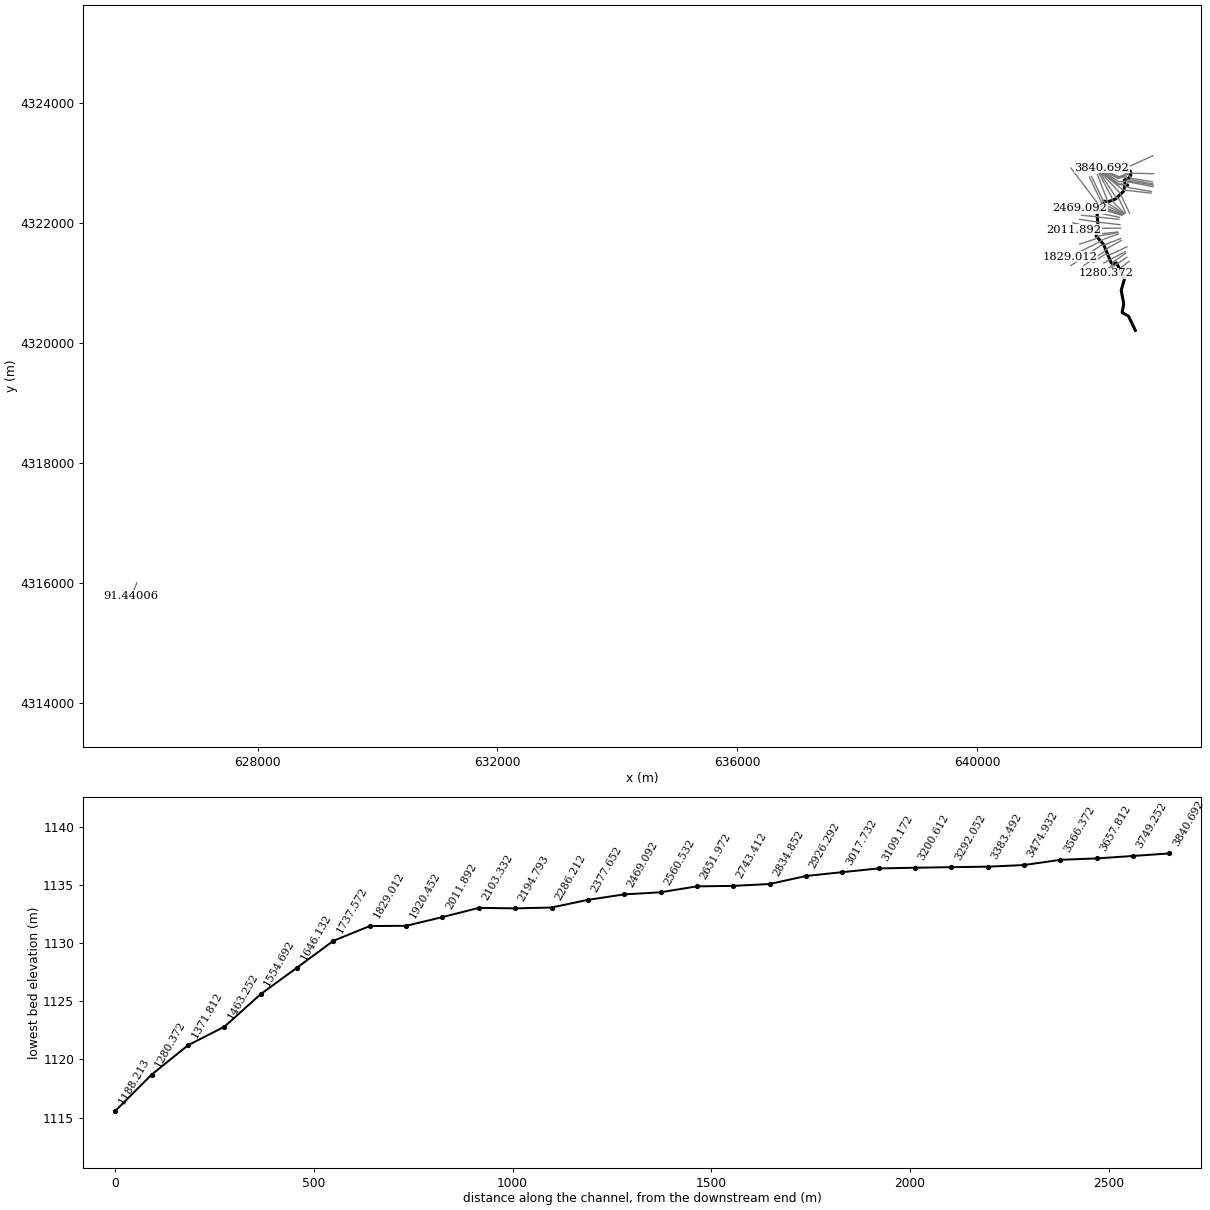
HEC-RAS study RedCreek.prj: RedCreek

--- RedCreek.g01 (geometry) --- (continued)

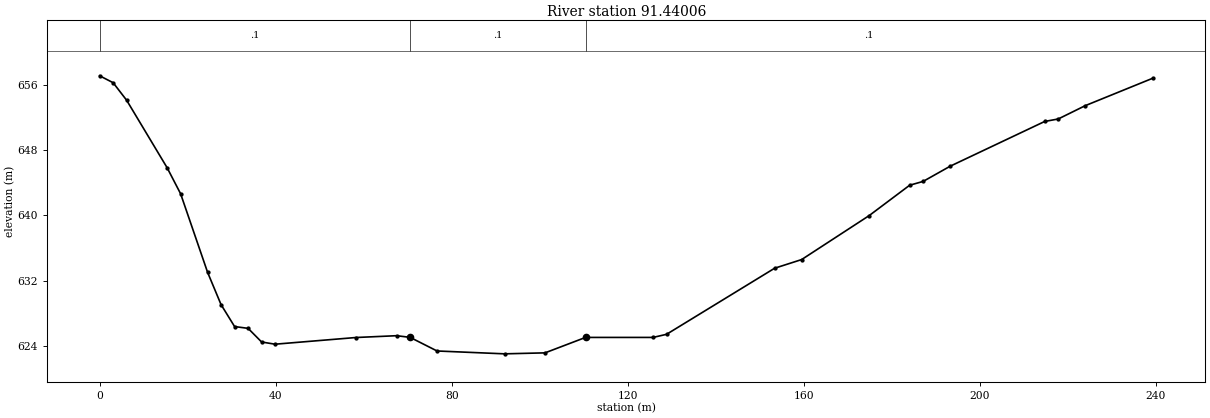
Type RM Length L Ch R = 1 ,91.44006,73.82,91.44,77
XS GIS Cut Line= 3
     625985.5954    4315996.4031     625948.0069    4315902.4233
     625888.8798    4315777.5963
#Sta/Elev= 30
       0   657.1    3.07  656.25    6.13  654.11   15.34  645.84    18.4  642.66
   24.54  633.03    27.6  629.08   30.67   626.4   33.74  626.18   36.81  624.51
   39.87  624.24   58.28  625.06   67.48  625.28   70.55  625.08   76.68  623.41
   92.02  623.06  101.22  623.18  110.43  625.07  125.77  625.07  128.84  625.45
   153.4  633.54  159.54   634.6  174.88  639.98  184.09   643.7  187.16  644.17
   193.3  646.03  214.79  651.51  217.85  651.81  223.99  653.44  239.34   656.8
#Mann= 3 , 0 , 0
       0      .1       0   70.55      .1       0  110.43      .1       0
Bank Sta=70.55,110.43
XS Rating Curve= 0 ,0
Exp/Cntr=0.3,0.1

River Reach=LeftForkRedCreek,1
Reach XY= 30
     642479.4387    4322893.8101     642559.2108    4322860.0757
     642562.4271    4322795.4606     642524.5719    4322740.4184
     642454.5204    4322717.9389     642467.8324    4322641.2578
      642511.627     4322626.762     642456.8168    4322613.6158
     642447.6887    4322532.6531     642310.7665    4322400.4935
     642159.9537    4322342.5496     642121.4568     4322363.584
     642107.5661    4322289.3683      641985.211    4322274.5479
     641983.8711    4322227.0902      642031.366    4322194.1181
     642000.0128    4322145.6992     642022.2378    4321873.0456
      641983.344    4321782.5579     642109.9474     4321638.492
      642232.582    4321340.8351     642265.7228    4321313.3147
     642321.0208    4321333.1585      642426.091      4321142.97
     642455.6262    4321058.2595     642402.8417    4320874.5061
     642445.6547     4320648.978     642417.4855    4320504.8131
     642523.9567    4320445.7443     642638.3306    4320206.7709

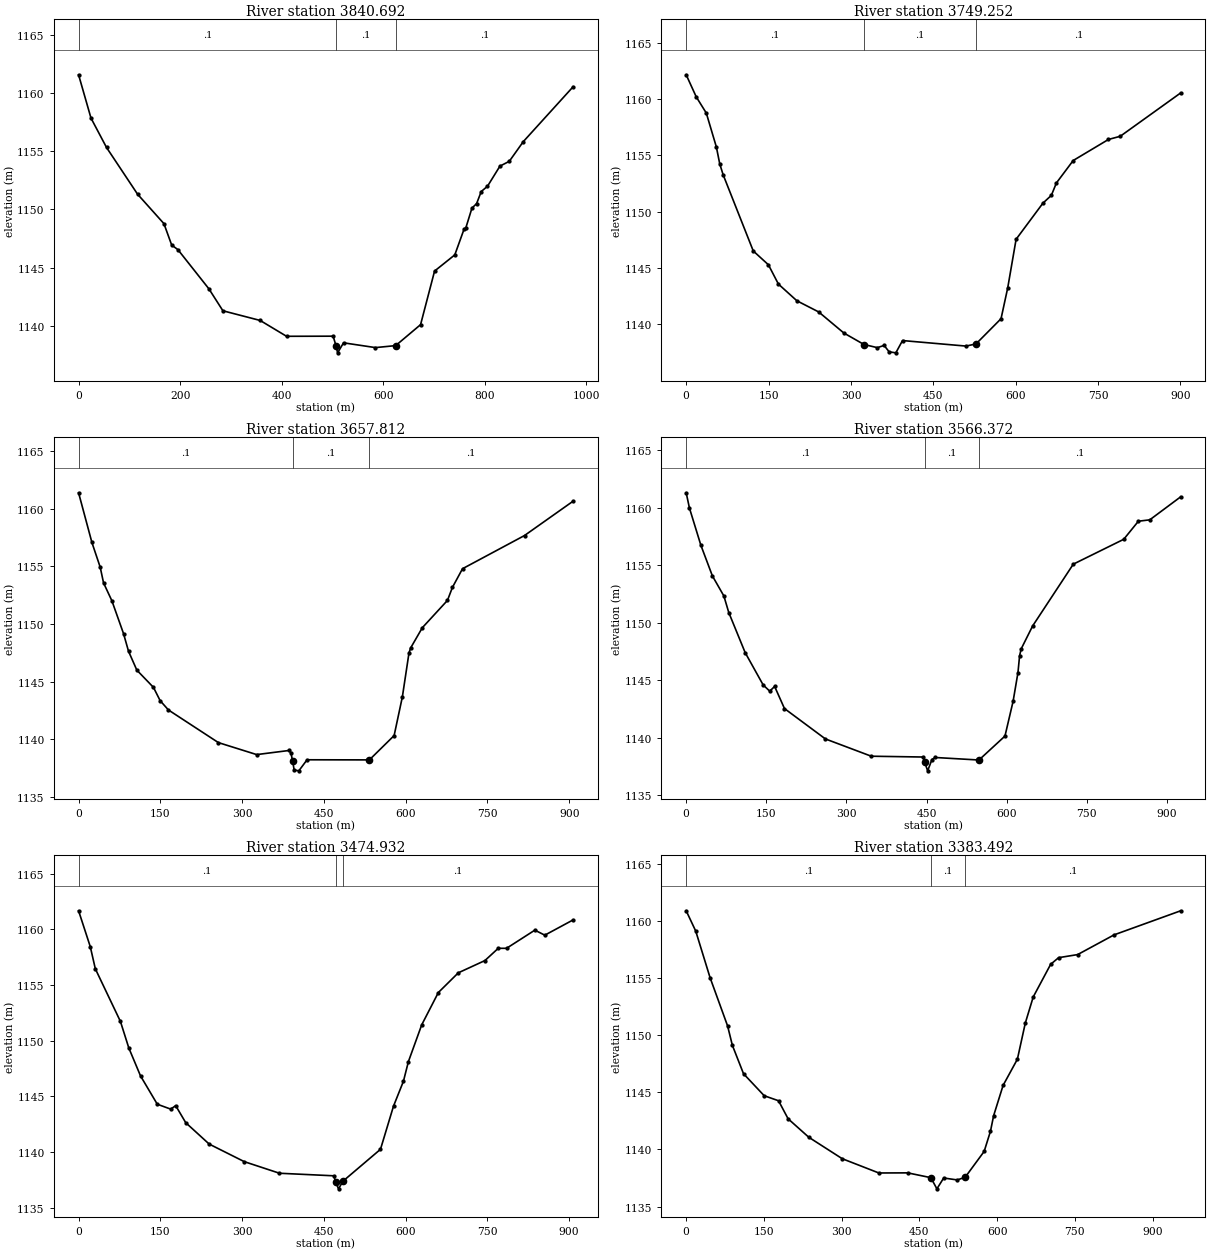
Type RM Length L Ch R = 1 ,3840.692,147.63,91.44,41.45
XS GIS Cut Line= 6
     642931.0759    4323119.9616     642507.8212    4322928.3453
      642499.614    4322895.5375     642496.3775    4322866.4107
     642480.0197     4322834.927     642077.7929    4322918.2164
#Sta/Elev= 30
       0 1161.56   24.45 1157.84   55.02 1155.32  116.15 1151.31  168.12 1148.78
   183.4 1146.94  195.62 1146.55  256.76 1143.18  284.27  1141.3  357.63 1140.47
  409.59 1139.11  501.36 1139.12  507.22 1138.27  510.15 1137.69  521.87 1138.55
  584.67 1138.14  624.52 1138.31  673.57 1140.11  701.15 1144.71     741  1146.1
   759.4 1148.33  762.46 1148.38  774.72 1150.11  783.92  1150.5  793.11 1151.54
  805.38 1151.99   829.9 1153.72  848.29 1154.13  875.88 1155.82  973.97 1160.53
#Mann= 3 , 0 , 0
       0      .1       0  507.22      .1       0  624.52      .1       0
Bank Sta=507.22,624.52
XS Rating Curve= 0 ,0
Exp/Cntr=0.3,0.1

Type RM Length L Ch R = 1 ,3749.252,93.08,91.44,32.42
XS GIS Cut Line= 5
     642941.3616    4322819.4274     642575.0266    4322829.9107
     642549.7798    4322840.5918      642365.743    4322768.5665
     642085.6974    4322898.8026
#Sta/Elev= 30
       0 1162.15   18.32 1160.19   36.65 1158.75   54.97 1155.74   61.08 1154.25
   67.19 1153.29  122.16 1146.51  149.65 1145.29  167.97 1143.57  201.57 1142.09
  241.27  1141.1  287.08 1139.23  323.73 1138.21  348.16 1137.93  360.38 1138.13
  369.53 1137.56  381.71 1137.47   393.9 1138.56  509.43 1138.07  527.68 1138.26
  573.28  1140.5  585.45 1143.24   600.7 1147.55  649.63 1150.76  664.92 1151.45
  674.09 1152.55  704.67 1154.54  768.88 1156.41  790.29 1156.69  900.37 1160.54
#Mann= 3 , 0 , 0
       0      .1       0  323.73      .1       0  527.68      .1       0
Bank Sta=323.73,527.68
XS Rating Curve= 0 ,0
Exp/Cntr=0.3,0.1

Type RM Length L Ch R = 1 ,3657.812,31.92,91.44,51.59
XS GIS Cut Line= 6
     642922.3115    4322686.0772     642587.5932    4322739.2384
     642568.0247     4322746.922     642510.3347    4322809.8823
     642354.1482    4322752.3105     642092.0474    4322887.6901
#Sta/Elev= 30
       0 1161.39   24.43 1157.08   39.69 1154.93    45.8 1153.57   61.07 1152.02
   82.44 1149.17    91.6 1147.64  106.86    1146   137.4  1144.5  149.61 1143.35
  164.88 1142.54  256.48 1139.71   326.7 1138.67  386.58 1139.03  389.55 1138.81
  392.51 1138.14  395.47 1137.33     404 1137.26  419.15 1138.22  533.42 1138.21
  578.82 1140.32  593.95 1143.68  606.05 1147.48  609.08 1147.92  630.54 1149.68
  676.64 1152.05  685.86 1153.19  704.29  1154.8  817.99 1157.68  907.11 1160.66
#Mann= 3 , 0 , 0
       0      .1       0  392.51      .1       0  533.42      .1       0
Bank Sta=392.51,533.42
XS Rating Curve= 0 ,0
Exp/Cntr=0.3,0.1

Type RM Length L Ch R = 1 ,3566.372,48.59,91.44,101.29
XS GIS Cut Line= 6
     642931.8366    4322649.5646     642554.0506    4322720.0164
     642507.8868    4322715.4157     642482.4807    4322776.3728
     642350.1254    4322741.0299     642095.2224    4322878.1651
#Sta/Elev= 30
       0 1161.29    6.13 1159.96   27.61 1156.72   49.08 1154.07   70.55 1152.33
   79.75 1150.89  110.42 1147.41  144.16  1144.6  156.43 1144.06  165.63 1144.47
  184.04 1142.55  260.72 1139.91   346.6 1138.41  443.67 1138.34  446.49  1137.9
  452.13 1137.14  460.18 1138.12     466  1138.3   548.2 1138.08  596.91 1140.16
  612.13 1143.18  621.26 1145.68  624.31 1147.15  627.35 1147.74  648.67 1149.72
  724.84 1155.09  819.29 1157.25  846.72 1158.82  868.04 1158.94  925.93 1160.94
#Mann= 3 , 0 , 0
       0      .1       0  446.49      .1       0   548.2      .1       0
Bank Sta=446.49,548.2
XS Rating Curve= 0 ,0
Exp/Cntr=0.3,0.1

Type RM Length L Ch R = 1 ,3474.932,23.87,91.44,76.23
XS GIS Cut Line= 6
     642935.0116    4322630.5146     642534.9057    4322696.0583
     642469.2548    4322701.8166     642454.3702     4322690.049
     642363.1421     4322685.855     642095.2224    4322867.0525
#Sta/Elev= 30
       0 1161.66    21.5 1158.43   30.72 1156.45   76.79 1151.72   92.15 1149.34
  113.65 1146.83  144.36 1144.29  168.93 1143.85  178.15 1144.16  196.58 1142.63
  239.58 1140.71  304.08 1139.13  368.58 1138.09  468.43 1137.86  471.48  1137.3
   476.9 1136.69  485.04 1137.38  553.83 1140.24  577.75 1144.12  595.93 1146.35
  605.09 1148.12   629.5 1151.42  660.01 1154.32  696.63 1156.09  745.45 1157.19
  769.86 1158.29  785.11 1158.29  836.99 1159.92  855.29 1159.47  907.17 1160.84
#Mann= 3 , 0 , 0
       0      .1       0  471.48      .1       0  485.04      .1       0
Bank Sta=471.48,485.04
XS Rating Curve= 0 ,0
Exp/Cntr=0.3,0.1

Type RM Length L Ch R = 1 ,3383.492,106.92,91.44,10.83
XS GIS Cut Line= 6
     642933.4241     4322603.527     642535.5341    4322682.3066
     642463.7155    4322631.3689     642430.1239    4322646.1644
     642357.1078    4322650.2003     642084.1099      4322862.29
#Sta/Elev= 30
       0 1160.92   18.44 1159.14   46.09 1155.06   79.89 1150.83   89.11 1149.13
  110.62 1146.64  150.57 1144.71  178.22 1144.27  196.66 1142.69  236.61 1141.07
  301.14 1139.19  371.81 1137.94  427.45 1137.95  472.07 1137.53  483.79 1136.55
  496.87  1137.5  523.11 1137.33  538.39 1137.57  574.96 1139.83  587.15  1141.6
  593.24 1142.96  611.53 1145.62  639.07 1147.91  654.36 1151.08  669.66 1153.37
  703.31 1156.23  718.61 1156.81  755.32 1157.08  825.69 1158.81  954.18 1160.92
#Mann= 3 , 0 , 0
       0      .1       0  472.07      .1       0  538.39      .1       0
Bank Sta=472.07,538.39
XS Rating Curve= 0 ,0
Exp/Cntr=0.3,0.1

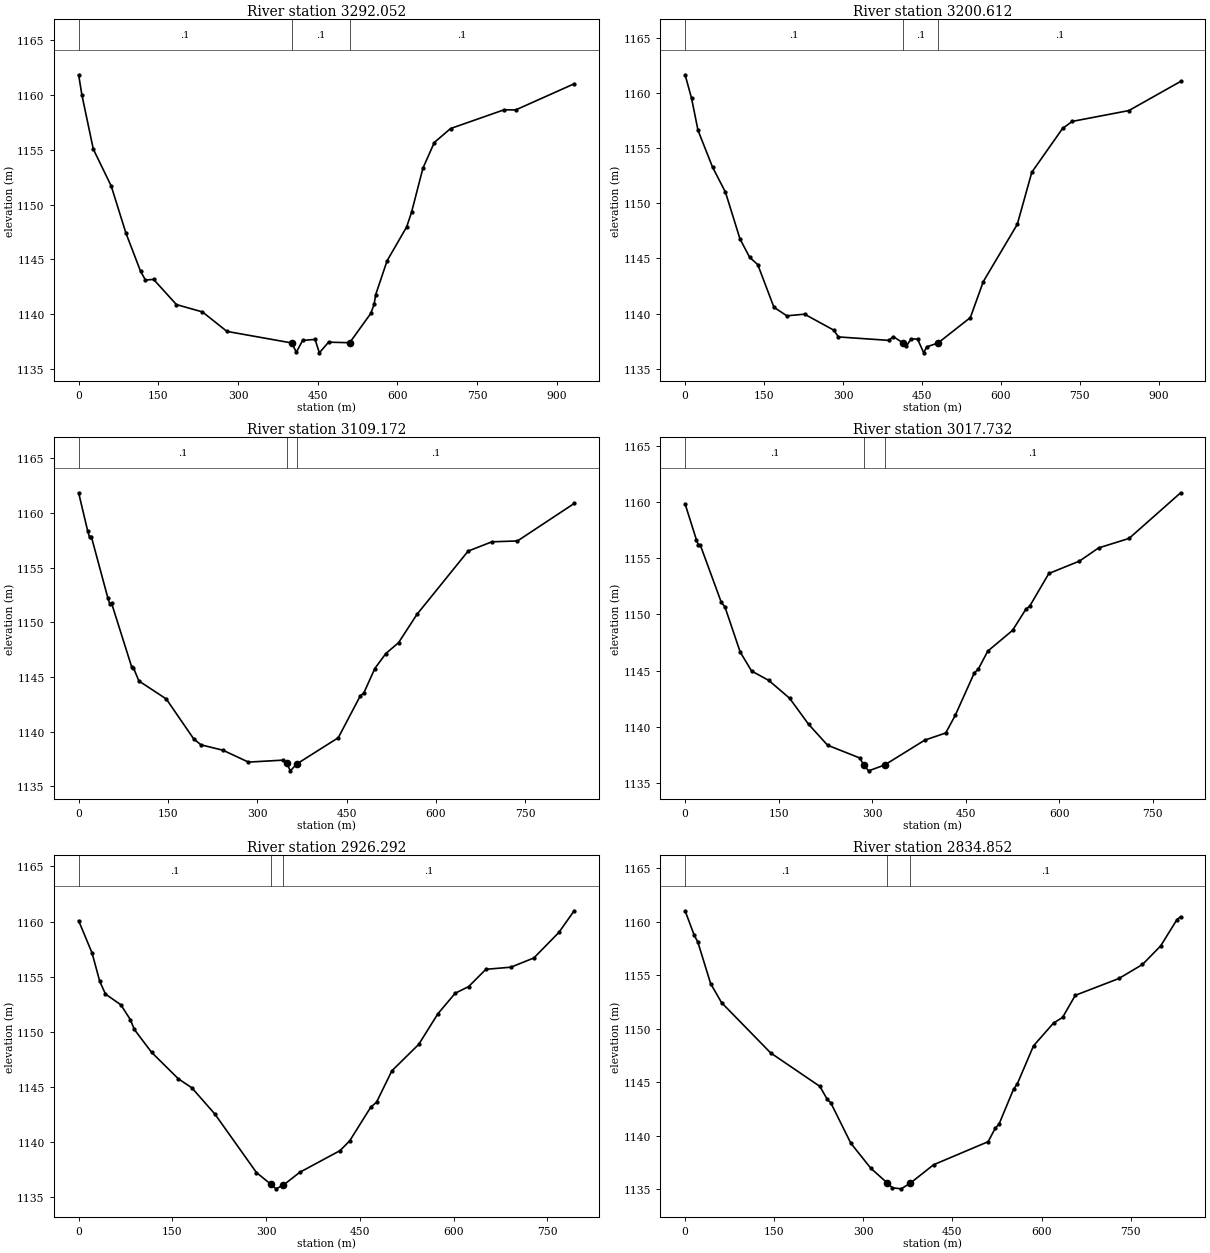
Type RM Length L Ch R = 1 ,3292.052,56.31,91.44,93.26
XS GIS Cut Line= 6
     642906.4365    4322522.5643     642552.7089    4322583.5881
     642474.9063    4322606.2618      642459.463    4322632.3245
     642352.3473    4322639.2584     642076.1723     4322852.765
#Sta/Elev= 30
       0  1161.8    6.14 1159.96   27.61 1155.04   61.36 1151.68   88.97 1147.41
  116.58 1143.93  125.79 1143.13  141.13 1143.19  184.08  1140.9  233.17 1140.23
  279.19 1138.46  401.03 1137.41  409.91 1136.57  421.75 1137.64  445.15 1137.73
  453.19 1136.51  470.55 1137.48  510.27 1137.43  550.14  1140.1  556.27 1140.93
  559.34 1141.81   580.8 1144.89  617.55 1147.96  626.74 1149.29  648.17  1153.3
  669.61 1155.64  700.23 1156.91  801.28 1158.62  822.71  1158.6  932.95 1160.98
#Mann= 3 , 0 , 0
       0      .1       0  401.03      .1       0  510.27      .1       0
Bank Sta=401.03,510.27
XS Rating Curve= 0 ,0
Exp/Cntr=0.3,0.1

Type RM Length L Ch R = 1 ,3200.612,173.43,91.44,75.56
XS GIS Cut Line= 6
     642903.2615    4322495.5768      642458.323    4322546.9168
     642456.2409    4322545.3048      642447.834    4322546.2939
     642429.8626    4322550.4358     642069.8223      4322843.24
#Sta/Elev= 30
       0 1161.63   12.27  1159.5   24.54  1156.6   52.15 1153.27   76.69    1151
   104.3 1146.77  122.71  1145.1  138.05 1144.45  168.73 1140.59  193.27 1139.81
  227.01 1139.96  282.23 1138.52  291.44  1137.9  386.54 1137.59  395.74 1137.92
  414.15 1137.36  420.28 1137.06  429.48 1137.73  441.76  1137.7  453.35 1136.46
  458.99    1137   480.5 1137.35  541.97 1139.65  566.56 1142.91   631.1 1148.09
  658.76 1152.81  717.15 1156.77  735.59 1157.41  843.16 1158.39   941.5 1161.03
#Mann= 3 , 0 , 0
       0      .1       0  414.15      .1       0   480.5      .1       0
Bank Sta=414.15,480.5
XS Rating Curve= 0 ,0
Exp/Cntr=0.3,0.1

Type RM Length L Ch R = 1 ,3109.172,73.49,91.44,97.01
XS GIS Cut Line= 5
     642542.8983    4322162.2011     642398.4166     4322463.671
     642389.6881    4322486.3652     642381.6753    4322500.2574
     642068.2348     4322833.715
#Sta/Elev= 30
       0 1161.86   15.34 1158.33    18.4 1157.78   21.47 1157.82   49.07 1152.23
   52.14 1151.71   55.21 1151.77   88.94 1145.94   92.01 1145.84  101.21 1144.63
  147.22 1142.98  193.22 1139.33  205.49 1138.78  242.29 1138.29  285.23  1137.2
  343.42 1137.38   349.5 1137.09  355.58  1136.4  366.64 1137.04  436.08 1139.43
  472.94 1143.25  479.09 1143.54  497.51 1145.77  515.94 1147.14  537.44 1148.14
  568.16 1150.72  654.16 1156.52  694.09 1157.37  737.09 1157.45   832.3 1160.88
#Mann= 3 , 0 , 0
       0      .1       0   349.5      .1       0  366.64      .1       0
Bank Sta=349.5,366.64
XS Rating Curve= 0 ,0
Exp/Cntr=0.3,0.1

Type RM Length L Ch R = 1 ,3017.732,99.42,91.44,70.09
XS GIS Cut Line= 6
     642474.6356    4322168.5511      642368.138     4322397.895
     642340.2261    4322416.4305     642322.2823    4322420.8582
     642309.1352    4322433.3618     642052.3598    4322828.9525
#Sta/Elev= 30
       0 1159.83   18.28 1156.61   21.33 1156.17   24.37 1156.17   57.88  1151.1
   63.98 1150.65   88.35 1146.65  106.63 1144.96  134.05 1144.13  167.56 1142.54
  198.03 1140.22  228.49 1138.36  280.28 1137.22  286.37  1136.6  294.29 1136.08
  319.97  1136.6  384.24 1138.81  417.93 1139.45  433.24 1141.02  463.87 1144.81
  469.99 1145.11  485.31 1146.73  525.12 1148.58  546.56 1150.47  552.68 1150.74
  583.31 1153.64   632.3 1154.74  662.93 1155.91  711.93 1156.76  794.62 1160.82
#Mann= 3 , 0 , 0
       0      .1       0  286.37      .1       0  319.97      .1       0
Bank Sta=286.37,319.97
XS Rating Curve= 0 ,0
Exp/Cntr=0.3,0.1

Type RM Length L Ch R = 1 ,2926.292,79.35,91.44,90.65
XS GIS Cut Line= 6
     642455.5856    4322162.2011     642260.2534    4322353.2591
     642251.6947    4322386.0064     642249.8342    4322400.6583
     642244.0476    4322428.9962     642036.4848    4322819.4274
#Sta/Elev= 30
       0 1160.08   21.49 1157.15   33.77 1154.58   42.98 1153.42   67.54 1152.45
   82.89 1151.09   89.03 1150.22  116.66 1148.14  159.64 1145.73  181.13 1144.92
  217.97 1142.54  284.52 1137.23  307.08 1136.19  315.94 1135.75  327.64 1136.09
  353.85 1137.25  418.33 1139.22  433.68  1140.1  467.46 1143.16  476.67 1143.61
  501.24 1146.46  544.23 1148.86  574.93 1151.64  602.57  1153.5  624.06  1154.1
   651.7 1155.67  691.62 1155.86  728.47  1156.7  768.38 1159.01  792.95 1160.98
#Mann= 3 , 0 , 0
       0      .1       0  307.08      .1       0  327.64      .1       0
Bank Sta=307.08,327.64
XS Rating Curve= 0 ,0
Exp/Cntr=0.3,0.1

Type RM Length L Ch R = 1 ,2834.852,62.3,91.44,72.82
XS GIS Cut Line= 5
     642450.8231    4322154.2636     642177.2005    4322329.7177
     642180.9997    4322359.2016     642171.1098    4322373.9187
     642006.3222    4322805.1399
#Sta/Elev= 30
       0 1161.01   15.33 1158.73   21.47 1158.09   42.93 1154.22   61.33 1152.44
  144.12 1147.74  226.92 1144.62  239.18 1143.42  245.32 1143.08  279.05 1139.31
  312.78 1136.97  339.91 1135.63  348.83 1135.16  363.64 1135.06  378.62 1135.57
  418.36 1137.31  510.08 1139.46  522.31 1140.74  528.42  1141.1  552.88 1144.36
  558.99 1144.83  586.51 1148.41  620.14 1150.53  635.42 1151.06  656.82 1153.12
  730.19 1154.69  769.94    1156  800.51 1157.73  828.02 1160.19  834.14 1160.46
#Mann= 3 , 0 , 0
       0      .1       0  339.91      .1       0  378.62      .1       0
Bank Sta=339.91,378.62
XS Rating Curve= 0 ,0
Exp/Cntr=0.3,0.1

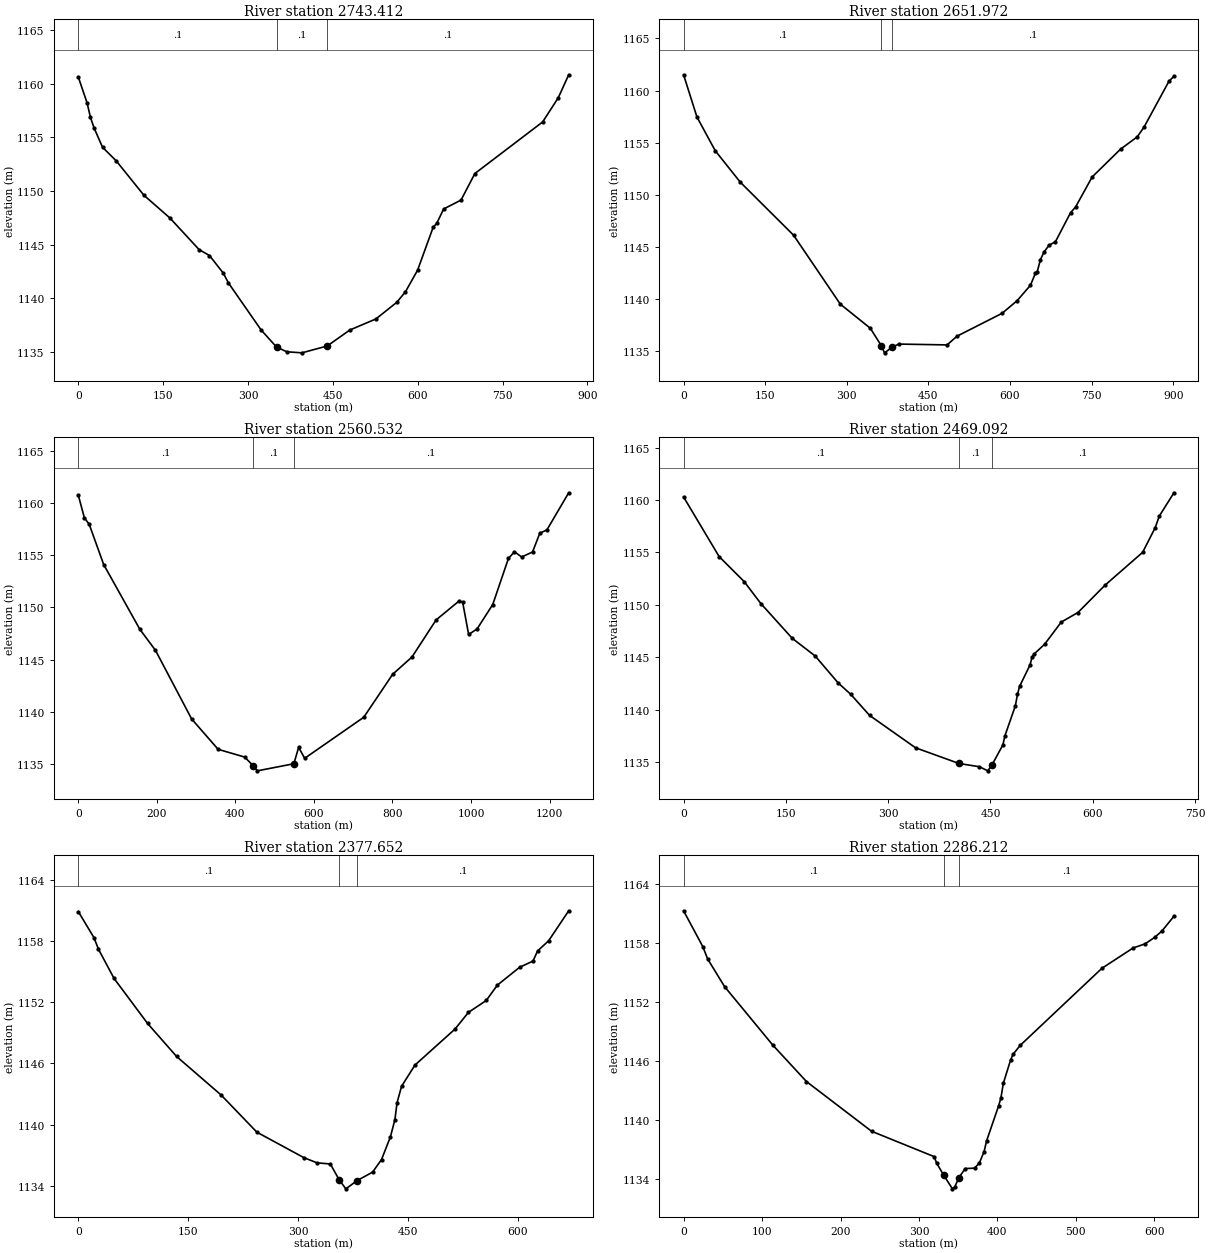
Type RM Length L Ch R = 1 ,2743.412,85.45,91.44,67.01
XS GIS Cut Line= 6
     642440.7689    4322152.0808     642162.3573    4322283.9182
     642127.7244    4322340.7156     642131.4894    4322344.3541
     642102.0648    4322369.1369     641908.9553    4322773.8529
#Sta/Elev= 30
       0 1160.61   15.25 1158.24   21.35 1156.88   27.45 1155.92    42.7 1154.08
    67.1  1152.8   115.9  1149.6  161.65 1147.49   213.5 1144.53   231.8 1143.98
   256.2 1142.34  265.35 1141.42  323.17 1137.03  350.38 1135.44  368.52    1135
  395.24  1134.9  440.08 1135.54  480.01 1137.03  526.08 1138.06  562.94 1139.61
  578.29 1140.59  599.79 1142.61  627.44 1146.63  633.58 1146.97  645.87 1148.32
  676.58 1149.15  701.15 1151.63  820.94 1156.44  848.58  1158.7  867.01 1160.84
#Mann= 3 , 0 , 0
       0      .1       0  350.38      .1       0  440.08      .1       0
Bank Sta=350.38,440.08
XS Rating Curve= 0 ,0
Exp/Cntr=0.3,0.1

Type RM Length L Ch R = 1 ,2651.972,78.79,91.44,113.43
XS GIS Cut Line= 5
     642431.6143    4322139.5395     642111.1081    4322262.1045
     642091.0553    4322300.7773     642090.2858    4322306.3461
     641871.9136    4322765.9153
#Sta/Elev= 30
       0 1161.51   24.51 1157.47   58.21 1154.23  104.17 1151.22  202.21 1146.13
  287.99 1139.53  343.14 1137.22  363.47 1135.54  369.28 1134.86   383.8 1135.41
  395.39  1135.7  484.28 1135.62  502.67 1136.46  585.43 1138.65  613.02 1139.86
  637.54 1141.34  646.73 1142.51   649.8 1142.62  655.93  1143.8  662.06 1144.49
  671.25 1145.15  683.51 1145.52   711.1 1148.28  720.29 1148.83  750.95 1151.72
  803.05 1154.38   833.7 1155.56  845.96 1156.47  891.94 1160.88  901.14 1161.37
#Mann= 3 , 0 , 0
       0      .1       0  363.47      .1       0   383.8      .1       0
Bank Sta=363.47,383.8
XS Rating Curve= 0 ,0
Exp/Cntr=0.3,0.1

Type RM Length L Ch R = 1 ,2560.532,36.27,91.44,121.82
XS GIS Cut Line= 6
     642423.9634    4322134.4463     642012.3184    4322267.3845
     642008.7003    4322292.3102     642021.9062     4322291.519
     641985.7645    4322358.0189     641565.2785    4322913.9765
#Sta/Elev= 30
       0 1160.72   15.34 1158.58   27.62 1157.96   64.44 1154.11   156.5 1147.91
   196.4 1145.89  288.46 1139.32  355.97 1136.41  423.57 1135.67  444.64 1134.86
  455.84 1134.35  548.89 1135.03  561.05  1136.6   576.4 1135.55  726.87 1139.48
  800.57  1143.6   849.7 1145.25  911.11  1148.8  969.46 1150.61  978.67 1150.52
  994.02 1147.41 1015.52 1147.94 1055.44 1150.28 1095.36 1154.69 1110.71 1155.33
 1129.14 1154.83 1156.77 1155.31  1175.2  1157.1 1193.62 1157.44  1248.9 1160.98
#Mann= 3 , 0 , 0
       0      .1       0  444.64      .1       0  548.89      .1       0
Bank Sta=444.64,548.89
XS Rating Curve= 0 ,0
Exp/Cntr=0.3,0.1

Type RM Length L Ch R = 1 ,2469.092,73.06,91.44,73.34
XS GIS Cut Line= 6
     642408.7057    4322127.5671     642030.5342    4322242.3505
     642020.2322    4322228.4148     641980.7871    4322231.4328
     641970.8705    4322230.8411     641714.1731    4322241.3382
#Sta/Elev= 30
       0 1160.29   52.08 1154.61   88.85 1152.22  113.35 1150.12  159.31 1146.81
  193.01 1145.12  226.71 1142.55  245.09 1141.47  272.66 1139.46  340.06 1136.37
  403.87 1134.87  433.84 1134.56  446.01 1134.17   452.1 1134.72  468.15 1136.64
  471.21 1137.52   486.5 1140.38  489.56 1141.46  492.62 1142.22  507.91 1144.26
  510.97 1145.01  514.03 1145.32  529.32 1146.24  553.79 1148.36  578.25 1149.27
  618.01 1151.88  673.07 1155.01  691.42 1157.35  697.54 1158.47  718.94 1160.69
#Mann= 3 , 0 , 0
       0      .1       0  403.87      .1       0   452.1      .1       0
Bank Sta=403.87,452.1
XS Rating Curve= 0 ,0
Exp/Cntr=0.3,0.1

Type RM Length L Ch R = 1 ,2377.652,84.33,91.44,86.11
XS GIS Cut Line= 4
     642374.3098    4322091.8483     642082.2395    4322154.4758
     642013.1421    4322177.3441     641716.8189    4322212.2339
#Sta/Elev= 30
       0 1160.89   21.34 1158.34   27.43 1157.21   48.77 1154.34   94.49 1149.93
  134.11 1146.69  195.08  1142.9  243.84 1139.26  307.81 1136.77     326 1136.25
   344.2 1136.14  356.33 1134.58  365.43  1133.7  380.63  1134.5  401.94 1135.34
  414.12 1136.57   426.3  1138.8  432.38 1140.48  435.43 1142.17  441.52 1143.76
  459.79 1145.84  514.59 1149.38  532.86 1151.01  557.21 1152.18  572.44 1153.69
  602.88 1155.44  621.15 1156.05  627.24 1157.03  642.46 1158.04  669.86 1160.98
#Mann= 3 , 0 , 0
       0      .1       0  356.33      .1       0  380.63      .1       0
Bank Sta=356.33,380.63
XS Rating Curve= 0 ,0
Exp/Cntr=0.3,0.1

Type RM Length L Ch R = 1 ,2286.212,84.23,91.42,89.59
XS GIS Cut Line= 6
     642362.4036    4322060.0982      642032.545    4322095.0566
     642022.9265    4322100.2964     642020.0942    4322101.3009
     642004.1816    4322102.2533     641741.9544    4322126.2442
#Sta/Elev= 30
       0 1161.29   24.57 1157.64   30.71 1156.39   52.21 1153.59  113.64 1147.65
  156.64 1143.94  239.57 1138.89  319.42 1136.31  322.49 1135.66  331.71  1134.4
  342.66 1133.04  345.66 1133.24  350.98 1134.19  358.95  1135.1  370.79 1135.14
  376.91 1135.65  383.04 1136.83   386.1 1137.89  401.41 1141.45  404.47 1142.28
  407.53 1143.76  416.72 1146.12  419.78 1146.69  428.97 1147.61  533.07 1155.44
  572.88 1157.51  588.19 1157.93  600.43 1158.59  609.62 1159.23  624.93 1160.73
#Mann= 3 , 0 , 0
       0      .1       0  331.71      .1       0  350.98      .1       0
Bank Sta=331.71,350.98
XS Rating Curve= 0 ,0
Exp/Cntr=0.3,0.1

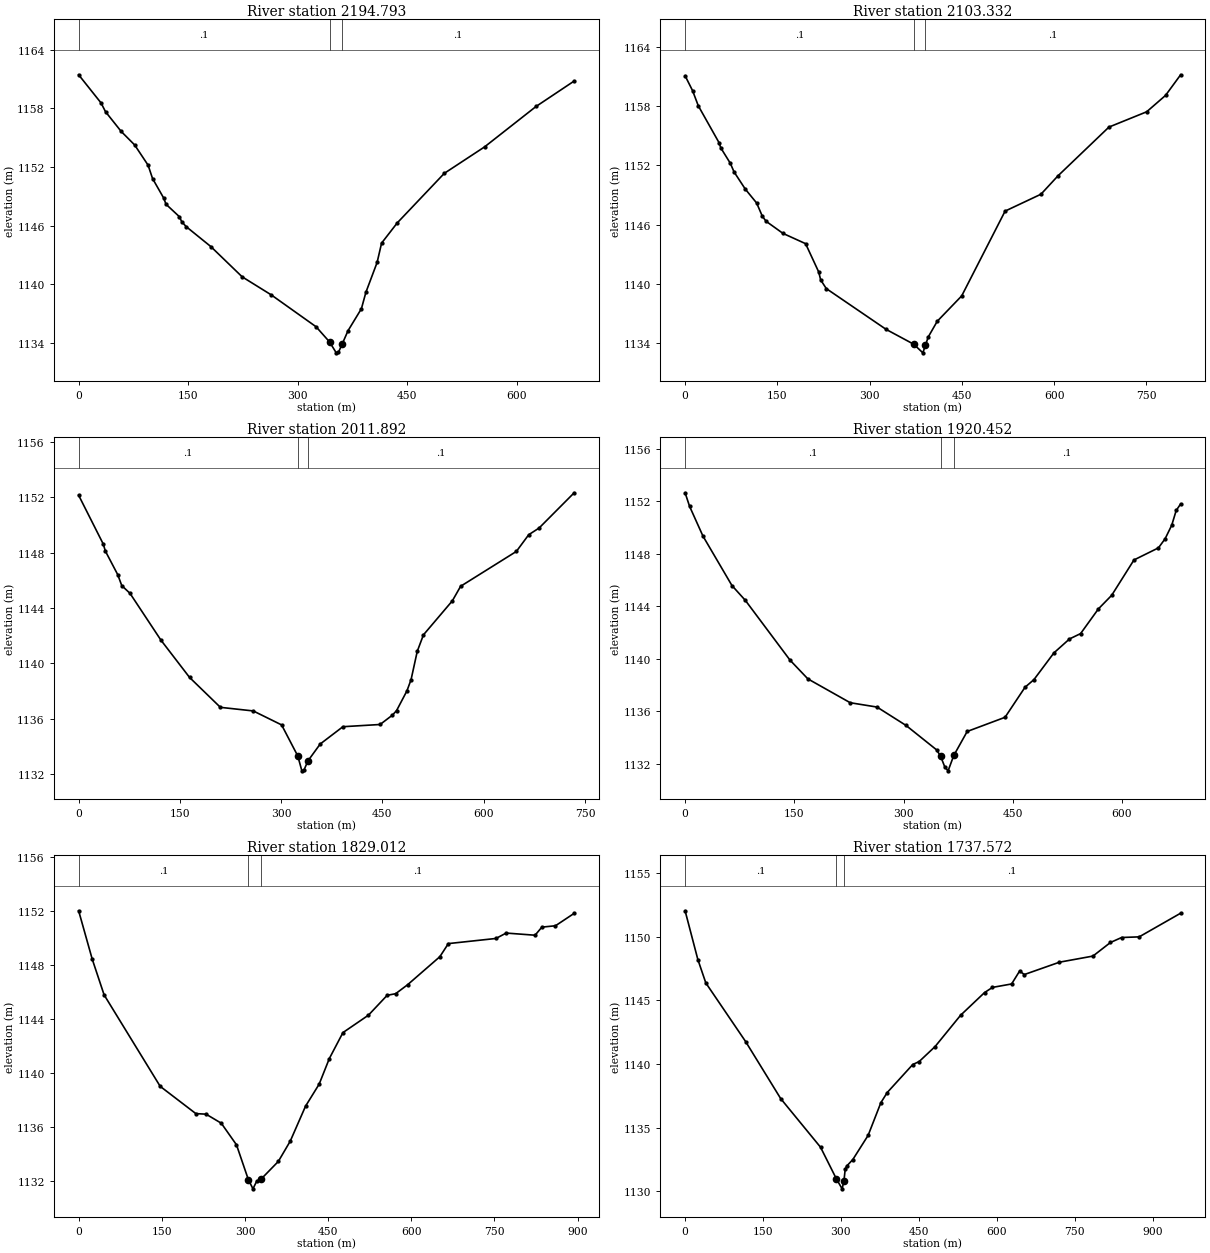
Type RM Length L Ch R = 1 ,2194.793,86.77,91.46,94.16
XS GIS Cut Line= 4
     642381.9166    4321969.5047     642025.2768    4322011.6643
     642018.5008    4322012.8876     641708.8153    4322058.2461
#Sta/Elev= 30
       0 1161.43   30.69 1158.55   36.83 1157.65   58.32 1155.63   76.74 1154.25
   95.15 1152.18  101.29 1150.81  116.64  1148.8  119.71 1148.18  138.12  1146.9
  141.19  1146.4  147.33 1145.89   181.1 1143.85  224.07 1140.75  263.97  1138.9
  325.36 1135.64  343.78 1134.09  352.98 1132.97  356.05 1133.03  361.42 1133.92
  369.08 1135.23  387.49 1137.49  393.63 1139.17  408.97 1142.22  415.11  1144.2
  436.58 1146.27  501.02 1151.34  556.26 1154.05  626.83 1158.19     679 1160.79
#Mann= 3 , 0 , 0
       0      .1       0  343.78      .1       0  361.42      .1       0
Bank Sta=343.78,361.42
XS Rating Curve= 0 ,0
Exp/Cntr=0.3,0.1

Type RM Length L Ch R = 1 ,2103.332,94.74,91.44,85.71
XS GIS Cut Line= 5
     642391.2035    4321912.2752     642085.1301    4321909.5266
     642015.5251    4321926.5838     641982.0918    4321915.7672
     641598.2457    4321998.9529
#Sta/Elev= 30
       0 1161.08   12.24 1159.56   21.43 1158.04    55.1 1154.31   58.16 1153.76
   73.46 1152.22   79.58 1151.34   97.95 1149.59  116.31 1148.19   125.5 1146.86
  131.62 1146.34  159.16 1145.11  195.89 1144.07  217.32 1141.19  220.38  1140.4
  229.56 1139.52  326.99 1135.38  371.78 1133.88  386.54 1133.01  390.82 1133.79
  395.32 1134.62  409.96 1136.21  449.71 1138.78  520.28 1147.37  578.58 1149.08
   606.2 1150.94  689.05 1155.88  750.42 1157.43   781.1 1159.09  805.65 1161.18
#Mann= 3 , 0 , 0
       0      .1       0  371.78      .1       0  390.82      .1       0
Bank Sta=371.78,390.82
XS Rating Curve= 0 ,0
Exp/Cntr=0.3,0.1

Type RM Length L Ch R = 1 ,2011.892,63.57,91.44,95.22
XS GIS Cut Line= 5
     642342.7847    4321848.1401     642088.7014    4321819.8246
     642003.5801    4321837.9036     641992.1816    4321842.0362
     641615.7082    4321887.8277
#Sta/Elev= 30
       0 1152.14   36.52 1148.61   39.57 1148.11   57.83 1146.41   63.91 1145.61
   76.09 1145.05  121.74 1141.68  164.35 1138.97     210 1136.81  258.66 1136.55
  300.67 1135.54  324.67 1133.29  330.67 1132.22  333.67 1132.26  339.68 1132.94
  357.86 1134.16   391.5 1135.41  446.55 1135.57  464.91 1136.25  471.02 1136.58
  486.31    1138  492.43 1138.81  501.61 1140.86  510.78 1142.05   553.6 1144.51
  565.83 1145.56  648.41 1148.08  666.76 1149.29  682.05 1149.77  734.05 1152.32
#Mann= 3 , 0 , 0
       0      .1       0  324.67      .1       0  339.68      .1       0
Bank Sta=324.67,339.68
XS Rating Curve= 0 ,0
Exp/Cntr=0.3,0.1

Type RM Length L Ch R = 1 ,1920.452,96.66,91.44,93.48
XS GIS Cut Line= 6
     642347.5472    4321837.0276     642012.3061    4321779.4152
     642006.9278    4321773.8441     641998.5197    4321761.5434
     641971.4748    4321732.2226     641707.7834    4321644.9397
#Sta/Elev= 30
       0 1152.66    6.13 1151.63   24.52 1149.36   64.35 1145.59   82.74 1144.46
  144.03 1139.91  168.55 1138.48  226.77 1136.66  263.54 1136.33  303.38 1134.93
  345.32 1133.07  350.79 1132.59  356.58 1131.77  361.14 1131.47  368.94 1132.64
  387.35 1134.47  439.32 1135.55  466.79 1137.84     479 1138.42  506.47 1140.46
  527.84 1141.52   543.1 1141.93  567.52 1143.81  585.83 1144.85  616.36 1147.54
  649.93 1148.46  659.09 1149.15  668.25 1150.19  674.35 1151.31  680.46 1151.81
#Mann= 3 , 0 , 0
       0      .1       0  350.79      .1       0  368.94      .1       0
Bank Sta=350.79,368.94
XS Rating Curve= 0 ,0
Exp/Cntr=0.3,0.1

Type RM Length L Ch R = 1 ,1829.012,89.95,91.44,76.74
XS GIS Cut Line= 6
     642349.9946    4321813.0827     642133.3418    4321736.3864
     642062.7553    4321700.2573     642054.2279    4321696.5451
     642050.7043    4321686.0364     641544.6675    4321436.3814
#Sta/Elev= 30
       0 1152.04   24.51 1148.46   45.97 1145.81  147.09 1139.04  211.44 1137.02
  229.83 1136.98  257.28 1136.31  284.72 1134.71  306.07 1132.14  314.46 1131.45
  321.22 1132.02  329.53 1132.19   360.2 1133.48  381.67 1134.98  409.27 1137.57
   433.8  1139.2   452.2  1141.1  476.74 1143.02  522.74 1144.31  556.47 1145.78
   571.8  1145.9  593.27 1146.56  651.54 1148.64  666.87 1149.61  752.74 1149.99
  771.14 1150.39  823.27 1150.23  835.54 1150.83  860.07 1150.93   893.8 1151.85
#Mann= 3 , 0 , 0
       0      .1       0  306.07      .1       0  329.53      .1       0
Bank Sta=306.07,329.53
XS Rating Curve= 0 ,0
Exp/Cntr=0.3,0.1

Type RM Length L Ch R = 1 ,1737.572,85.98,91.44,96.23
XS GIS Cut Line= 5
     642393.9817      4321739.33     642116.9421    4321630.7721
     642112.4158    4321629.3206     642065.6988    4321624.5697
     641563.1883    4321288.2145
#Sta/Elev= 30
       0 1152.03   24.54  1148.2   39.88 1146.36  116.57 1141.75  184.05 1137.27
  260.74 1133.45  291.41 1130.95   302.3 1130.18  305.83 1130.82  308.17  1131.7
  311.11 1131.97  322.85 1132.48  352.33 1134.38  376.89 1136.95  389.16 1137.75
  438.28 1139.95  450.55 1140.18  481.25 1141.36  530.36 1143.82   576.4  1145.6
  591.75 1146.01  628.59 1146.28  643.93 1147.29  653.14 1147.02  720.67 1147.99
  785.13 1148.47   818.9 1149.54  840.38 1149.93  874.15 1149.98  953.96 1151.84
#Mann= 3 , 0 , 0
       0      .1       0  291.41      .1       0  305.83      .1       0
Bank Sta=291.41,305.83
XS Rating Curve= 0 ,0
Exp/Cntr=0.3,0.1

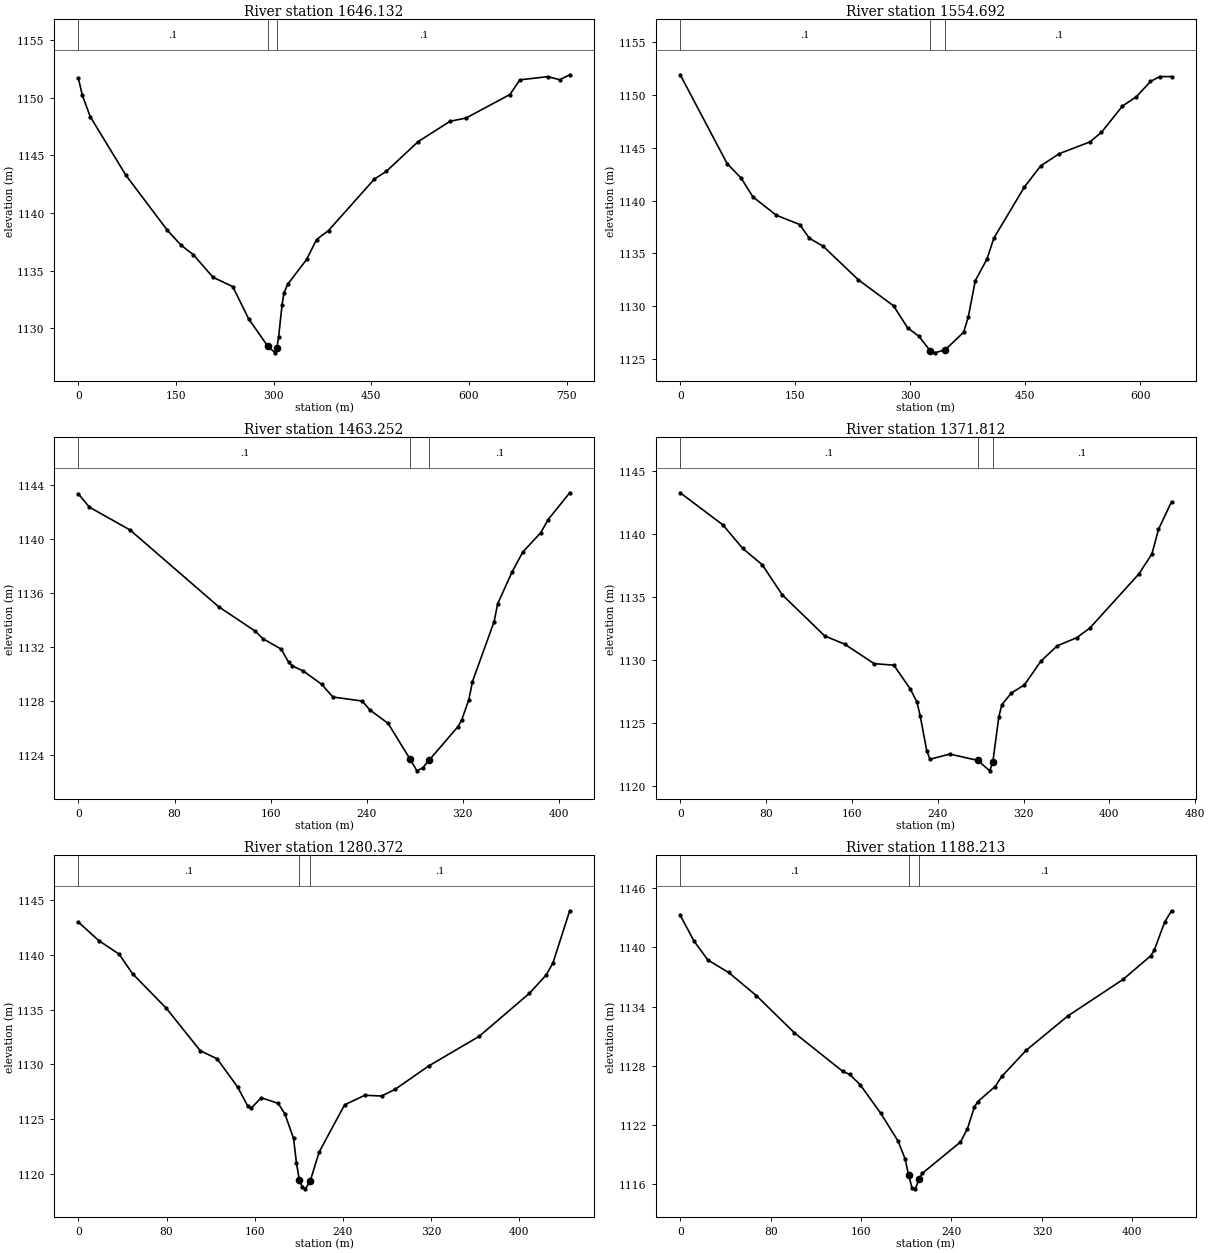
Type RM Length L Ch R = 1 ,1646.132,103.15,91.44,82.39
XS GIS Cut Line= 6
     642407.2108    4321707.5799     642179.1829    4321579.7557
     642153.4327    4321555.2185     642140.7166    4321545.8281
     642113.9407    4321519.3165       641781.47    4321289.5374
#Sta/Elev= 30
       0 1151.66    6.08 1150.19   18.24 1148.34   72.95 1143.27  136.78 1138.49
  158.06 1137.19   176.3  1136.4   206.7 1134.43  237.09 1133.62  261.41 1130.83
  291.05 1128.44  302.25 1127.88  304.88  1128.3  307.52 1129.28  312.79 1132.03
  315.69 1133.06  321.48 1133.83  350.47 1135.97  365.78  1137.7  384.15 1138.48
  454.57 1142.94  472.94 1143.61  521.92 1146.19  570.91 1147.95  595.41 1148.23
  662.76 1150.27  678.07 1151.54  720.94 1151.82  739.31 1151.55  754.62 1151.98
#Mann= 3 , 0 , 0
       0      .1       0  291.05      .1       0  304.88      .1       0
Bank Sta=291.05,304.88
XS Rating Curve= 0 ,0
Exp/Cntr=0.3,0.1

Type RM Length L Ch R = 1 ,1554.692,80.74,91.44,97.82
XS GIS Cut Line= 6
     642497.1694    4321600.4234     642220.6123    4321470.4054
     642185.8192    4321469.7664      642178.346    4321471.3782
      642143.883    4321483.6346     641932.2828    4321339.8083
#Sta/Elev= 30
       0 1151.91   61.12 1143.51   79.45 1142.13   94.73 1140.36  125.29 1138.62
  155.85 1137.74  168.08 1136.46  186.41 1135.68  232.25 1132.51  278.09 1130.05
  296.43 1127.97   311.4 1127.15  325.89 1125.79  331.69  1125.6  345.49 1125.89
  369.38 1127.54  375.47 1128.97  384.62 1132.42  399.85 1134.47  408.98 1136.47
  448.58 1141.28   469.9 1143.29  494.27 1144.45  533.86 1145.55  549.09 1146.46
  576.51 1148.95  594.78 1149.84  613.06 1151.28  625.24 1151.74  640.47 1151.74
#Mann= 3 , 0 , 0
       0      .1       0  325.89      .1       0  345.49      .1       0
Bank Sta=325.89,345.49
XS Rating Curve= 0 ,0
Exp/Cntr=0.3,0.1

Type RM Length L Ch R = 1 ,1463.252,75.98,91.44,95.1
XS GIS Cut Line= 4
     642474.6797    4321519.7254      642225.441    4321393.7063
     642217.1335    4321388.6052     642112.1998    4321330.5479
#Sta/Elev= 30
       0 1143.35    9.21 1142.37   42.97 1140.68  116.62 1134.99  147.32 1133.16
  153.45 1132.62   168.8 1131.83  174.94 1130.87  178.01 1130.59  187.21 1130.21
  202.56 1129.22  211.77 1128.28  236.32 1127.98  242.46 1127.33   257.8 1126.32
  276.22 1123.65  281.72  1122.8   286.6 1123.02  292.03  1123.6  316.02 1126.09
  319.02 1126.57  325.01 1128.09  328.01 1129.43     346 1133.87     349  1135.2
  360.99 1137.57  369.98 1139.05  384.97 1140.49  390.97 1141.45  408.96 1143.44
#Mann= 3 , 0 , 0
       0      .1       0  276.22      .1       0  292.03      .1       0
Bank Sta=276.22,292.03
XS Rating Curve= 0 ,0
Exp/Cntr=0.3,0.1

Type RM Length L Ch R = 1 ,1371.812,87.81,91.44,70.62
XS GIS Cut Line= 6
     642472.2985    4321489.2982     642266.7249    4321344.8869
     642263.6584    4321324.8175     642260.2032    4321310.9969
     642253.2311    4321295.6743     642135.7478    4321194.0226
#Sta/Elev= 30
       0 1143.26   39.83 1140.71   58.21 1138.85   76.59 1137.54   94.98 1135.18
   134.8  1131.9  153.19 1131.26  180.76 1129.71  199.14 1129.59  214.46  1127.7
  220.59 1126.68  223.65 1125.59  229.78  1122.8  232.84 1122.13  251.23 1122.54
  277.23 1122.04  288.58 1121.21  291.39 1121.92     297  1125.5   299.8 1126.46
   308.7 1127.38  320.89 1128.03  336.12  1129.9  351.35 1131.12  369.63 1131.77
  381.81 1132.53   427.5 1136.82  439.69 1138.41  445.78 1140.35  457.96 1142.55
#Mann= 3 , 0 , 0
       0      .1       0  277.23      .1       0  291.39      .1       0
Bank Sta=277.23,291.39
XS Rating Curve= 0 ,0
Exp/Cntr=0.3,0.1

Type RM Length L Ch R = 1 ,1280.372,88.32,92.16,94.19
XS GIS Cut Line= 6
     642497.6985    4321427.3856     642344.1885    4321319.7546
     642332.4128    4321314.1353     642320.3033    4321310.1603
      642308.616    4321304.3315     642145.2728      4321157.51
#Sta/Elev= 30
       0 1142.95   18.44 1141.27   36.88 1140.04   49.18 1138.25   79.91  1135.1
  110.65 1131.25  126.01 1130.51  144.45 1127.96  153.67 1126.23  156.75 1126.02
  165.97 1126.98  181.34 1126.46  187.48  1125.5  195.31 1123.27  197.92 1121.05
  200.53 1119.49  203.33 1118.83  206.13 1118.69  210.48 1119.42  218.53 1122.04
  241.62 1126.33  259.92  1127.2  275.17 1127.13  287.37 1127.73  317.88 1129.86
  363.63 1132.55  409.39 1136.47  424.64 1138.14  430.74 1139.23  445.99 1143.98
#Mann= 3 , 0 , 0
       0      .1       0  200.53      .1       0  210.48      .1       0
Bank Sta=200.53,210.48
XS Rating Curve= 0 ,0
Exp/Cntr=0.3,0.1

Type RM Length L Ch R = 1 ,1188.213,91.17,90.72,91.08
XS GIS Cut Line= 2
     642535.7986     4321359.123     642191.3104    4321094.0099
#Sta/Elev= 30
       0 1143.24   12.24 1140.63   24.49 1138.71   42.86 1137.45   67.35 1135.11
  101.02 1131.34  143.88 1127.43     150 1127.12  159.18 1126.09  177.55 1123.17
  192.86 1120.35  198.98 1118.57  202.04 1116.94   205.1 1115.63  208.16 1115.54
  211.22 1116.56  214.28 1117.12  247.96 1120.28  254.08 1121.62   260.2 1123.81
  263.26 1124.37  278.57  1125.9  284.69 1126.95  306.12 1129.57  342.86 1133.04
  391.84 1136.75  416.33 1139.14  419.39  1139.7  428.57 1142.54  434.69  1143.7
#Mann= 3 , 0 , 0
       0      .1       0  202.04      .1       0  211.22      .1       0
Bank Sta=202.04,211.22
XS Rating Curve= 0 ,0
Exp/Cntr=0.3,0.1