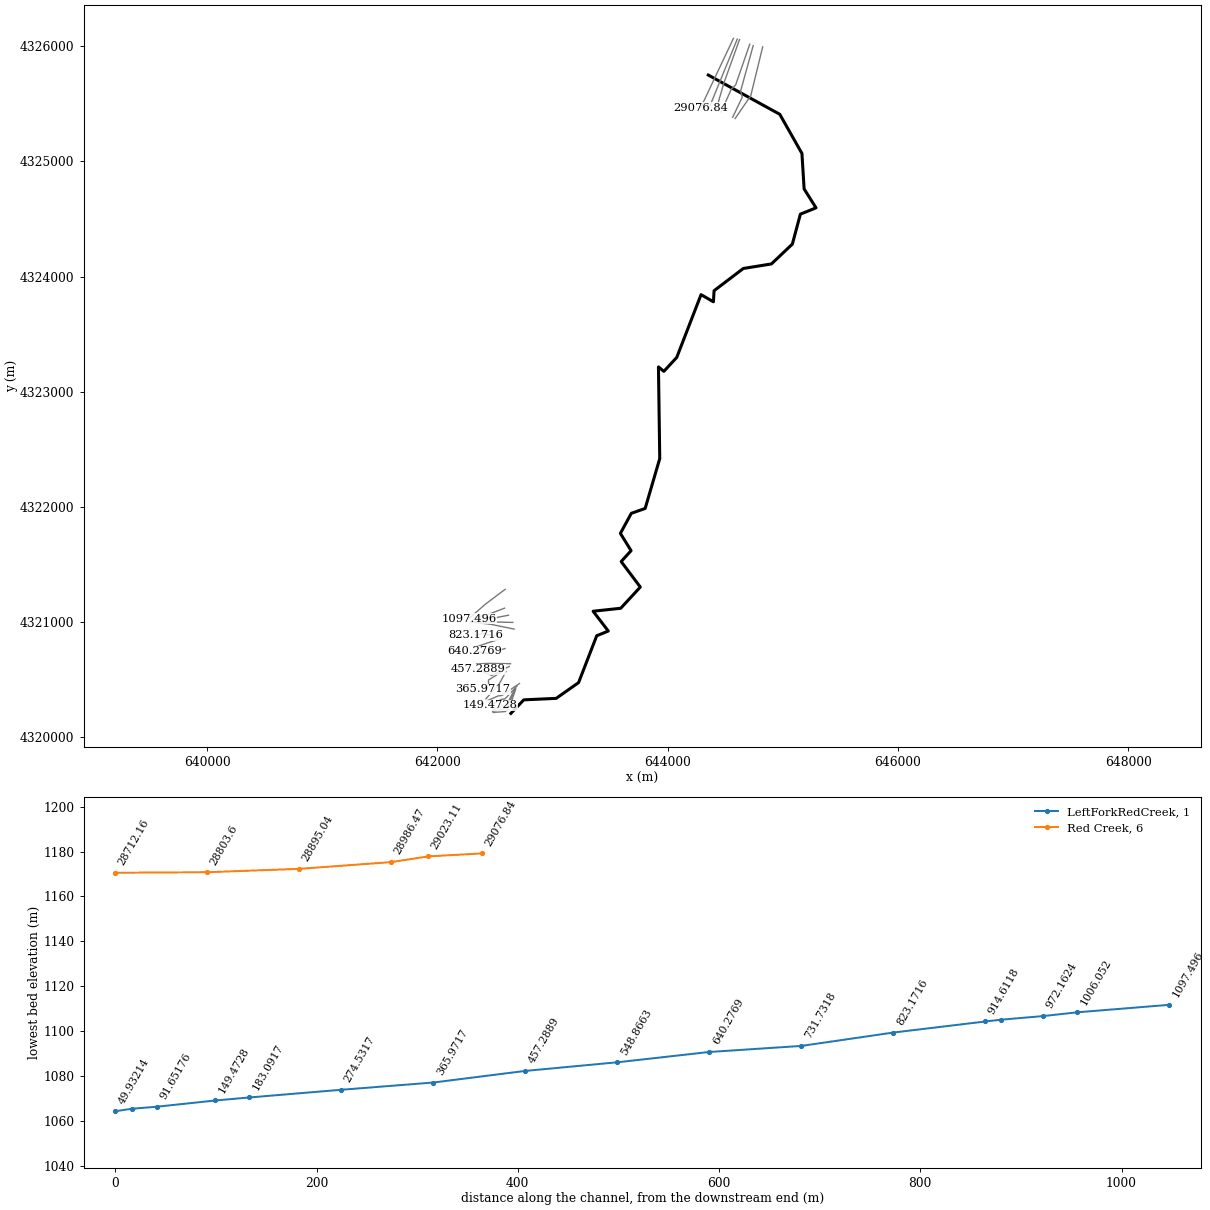
HEC-RAS study RedCreek.prj: RedCreek

--- RedCreek.g01 (geometry) --- (continued)

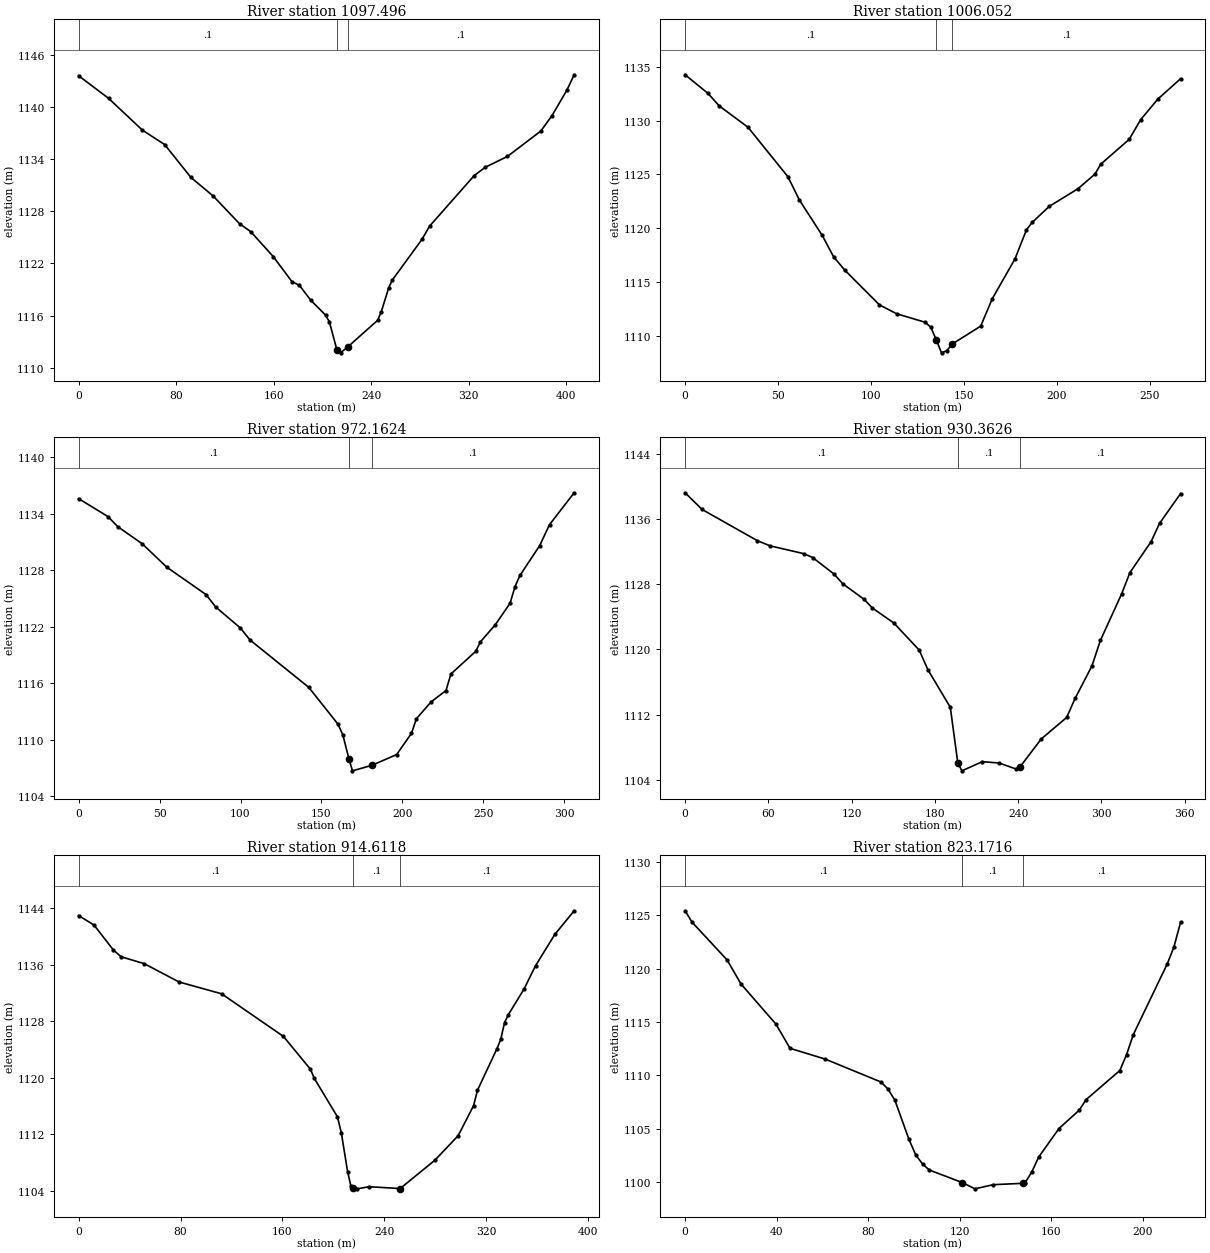
Type RM Length L Ch R = 1 ,1097.496,95.29,91.44,88.78
XS GIS Cut Line= 3
     642588.4243    4321284.1134     642421.4521    4321158.6274
     642271.7175    4321029.3192
#Sta/Elev= 30
       0 1143.58   24.57 1140.98   52.22 1137.34   70.65 1135.66   92.15 1131.89
  110.58 1129.73  132.08 1126.56  141.29 1125.65  159.72 1122.79  175.08 1119.91
  181.22 1119.48  190.44 1117.78  202.73 1116.05   205.8 1115.28  211.91  1112.1
  214.96 1111.72  221.04 1112.42  245.39 1115.46  248.44 1116.46  254.53 1119.22
  257.57 1120.11  281.92 1124.79  288.01 1126.28  324.53 1132.08  333.66 1133.05
  351.92  1134.3  379.32 1137.22  388.45 1138.98  400.62 1141.89  406.71 1143.69
#Mann= 3 , 0 , 0
       0      .1       0  211.91      .1       0  221.04      .1       0
Bank Sta=211.91,221.04
XS Rating Curve= 0 ,0
Exp/Cntr=0.3,0.1

Type RM Length L Ch R = 1 ,1006.052,43.6,33.89,30.71
XS GIS Cut Line= 4
     642582.8681    4321120.6006     642459.5623    4321073.0784
     642448.4803    4321070.0561     642328.8676    4321042.0192
#Sta/Elev= 30
       0 1134.28   12.29 1132.55   18.44 1131.37    33.8  1129.4   55.32 1124.78
   61.46 1122.62   73.76 1119.32    79.9 1117.32   86.05 1116.06  104.49 1112.86
  113.71 1112.03  129.07 1111.24  132.15 1110.77  135.02 1109.62  137.89 1108.39
  140.76 1108.59  143.63 1109.21  158.99 1110.88  165.13 1113.41  177.42 1117.14
  183.56 1119.84  186.63 1120.53  195.85 1122.03   211.2 1123.66  220.42 1125.03
  223.49 1125.95  238.85 1128.27  244.99  1130.1   254.2 1132.01  266.49 1133.92
#Mann= 3 , 0 , 0
       0      .1       0  135.02      .1       0  143.63      .1       0
Bank Sta=135.02,143.63
XS Rating Curve= 0 ,0
Exp/Cntr=0.3,0.1

Type RM Length L Ch R = 1 ,972.1624,33.32,41.8,44.3
XS GIS Cut Line= 4
     642617.8848    4321059.3661     642472.3637    4321031.1086
     642446.9636    4321039.9986     642316.5873    4321027.4573
#Sta/Elev= 30
       0 1135.62   18.15 1133.71    24.2 1132.64   39.33 1130.82   54.46 1128.34
   78.66 1125.44   84.71 1124.11   99.83  1121.9  105.89 1120.61  142.19 1115.58
   160.2 1111.68  163.19 1110.55  166.97    1108  169.17 1106.72  181.24 1107.31
  196.47 1108.45  205.61  1110.7  208.66 1112.25  217.79 1114.05  226.93 1115.24
  229.98    1117  245.21 1119.39  248.25 1120.42  257.39 1122.23  266.53 1124.51
  269.58 1126.28  272.62 1127.46  284.81 1130.63   290.9 1132.86  306.13 1136.24
#Mann= 3 , 0 , 0
       0      .1       0  166.97      .1       0  181.24      .1       0
Bank Sta=166.97,181.24
XS Rating Curve= 0 ,0
Exp/Cntr=0.3,0.1

Type RM Length L Ch R = 1 ,930.3626,20.3,15.75,13.76
XS GIS Cut Line= 5
     642654.9133    4320996.5804     642480.0102    4321001.1841
     642458.5789     4320998.406     642438.3382    4320994.4373
     642299.0348    4321008.3279
#Sta/Elev= 30
       0 1139.24   12.28 1137.19   52.18 1133.35   61.39 1132.72   85.95 1131.75
   92.09 1131.27  107.43 1129.25  113.57 1128.08  128.92 1126.17  135.06 1125.08
  150.41 1123.26  168.82 1119.91  174.96 1117.53  191.17  1112.9  196.57 1106.07
  199.52  1105.1  214.25 1106.23  226.33 1106.06   238.5 1105.33  241.55 1105.62
  256.76 1109.02  275.02 1111.65  281.11 1113.99  293.28 1117.99  299.37 1121.12
  314.59  1126.8  320.67 1129.45  335.89 1133.24  341.98 1135.48  357.19 1139.15
#Mann= 3 , 0 , 0
       0      .1       0  196.57      .1       0  241.55      .1       0
Bank Sta=196.57,241.55
XS Rating Curve= 0 ,0
Exp/Cntr=0.3,0.1

Type RM Length L Ch R = 1 ,914.6118,95.1,91.44,111.13
XS GIS Cut Line= 6
      642666.212    4320938.8315     642464.1908     4320980.424
     642451.8893    4320981.6857     642448.0662    4320981.1553
     642442.9068    4320983.4042       642282.83    4320999.9504
#Sta/Elev= 30
       0 1142.99   12.13 1141.63    27.3  1138.1   33.37 1137.15   51.56 1136.17
   78.86 1133.58  112.23 1131.91  160.76 1125.88  181.99 1121.23  185.03 1119.93
  203.23 1114.48  206.26  1112.2   211.2 1106.69  213.68 1104.73  215.68 1104.42
  218.62  1104.3  228.11  1104.6   252.4 1104.34  279.73 1108.36  297.95 1111.82
   310.1 1116.09  313.13 1118.26  328.31 1124.09  331.35 1125.44  334.39 1127.82
  337.42 1128.97  349.57 1132.55  358.68 1135.87  373.86 1140.32  389.04 1143.66
#Mann= 3 , 0 , 0
       0      .1       0  215.68      .1       0   252.4      .1       0
Bank Sta=215.68,252.4
XS Rating Curve= 0 ,0
Exp/Cntr=0.3,0.1

Type RM Length L Ch R = 1 ,823.1716,82.47,91.44,96.66
XS GIS Cut Line= 5
     642540.6537    4320872.6591     642438.1443    4320889.2785
     642420.0348    4320897.9519      642402.434     4320904.383
      642330.971    4320885.8883
#Sta/Elev= 30
       0 1125.41    3.05 1124.34   18.33 1120.81   24.43 1118.55   39.71 1114.79
   45.82 1112.53   61.09 1111.53   85.52 1109.38   88.58 1108.73   91.63 1107.68
   97.74 1104.03  100.79 1102.53  103.85 1101.67  106.72 1101.13  121.06 1099.96
   126.6 1099.37  134.64 1099.76  147.79 1099.89  148.57 1099.95  151.52 1100.98
  154.48 1102.35  163.34 1105.02  172.19 1106.74  175.15 1107.72  189.91 1110.45
  192.86 1111.94  195.81 1113.82  210.58 1120.41  213.53 1122.01  216.48 1124.35
#Mann= 3 , 0 , 0
       0      .1       0  121.06      .1       0  147.79      .1       0
Bank Sta=121.06,147.79
XS Rating Curve= 0 ,0
Exp/Cntr=0.3,0.1

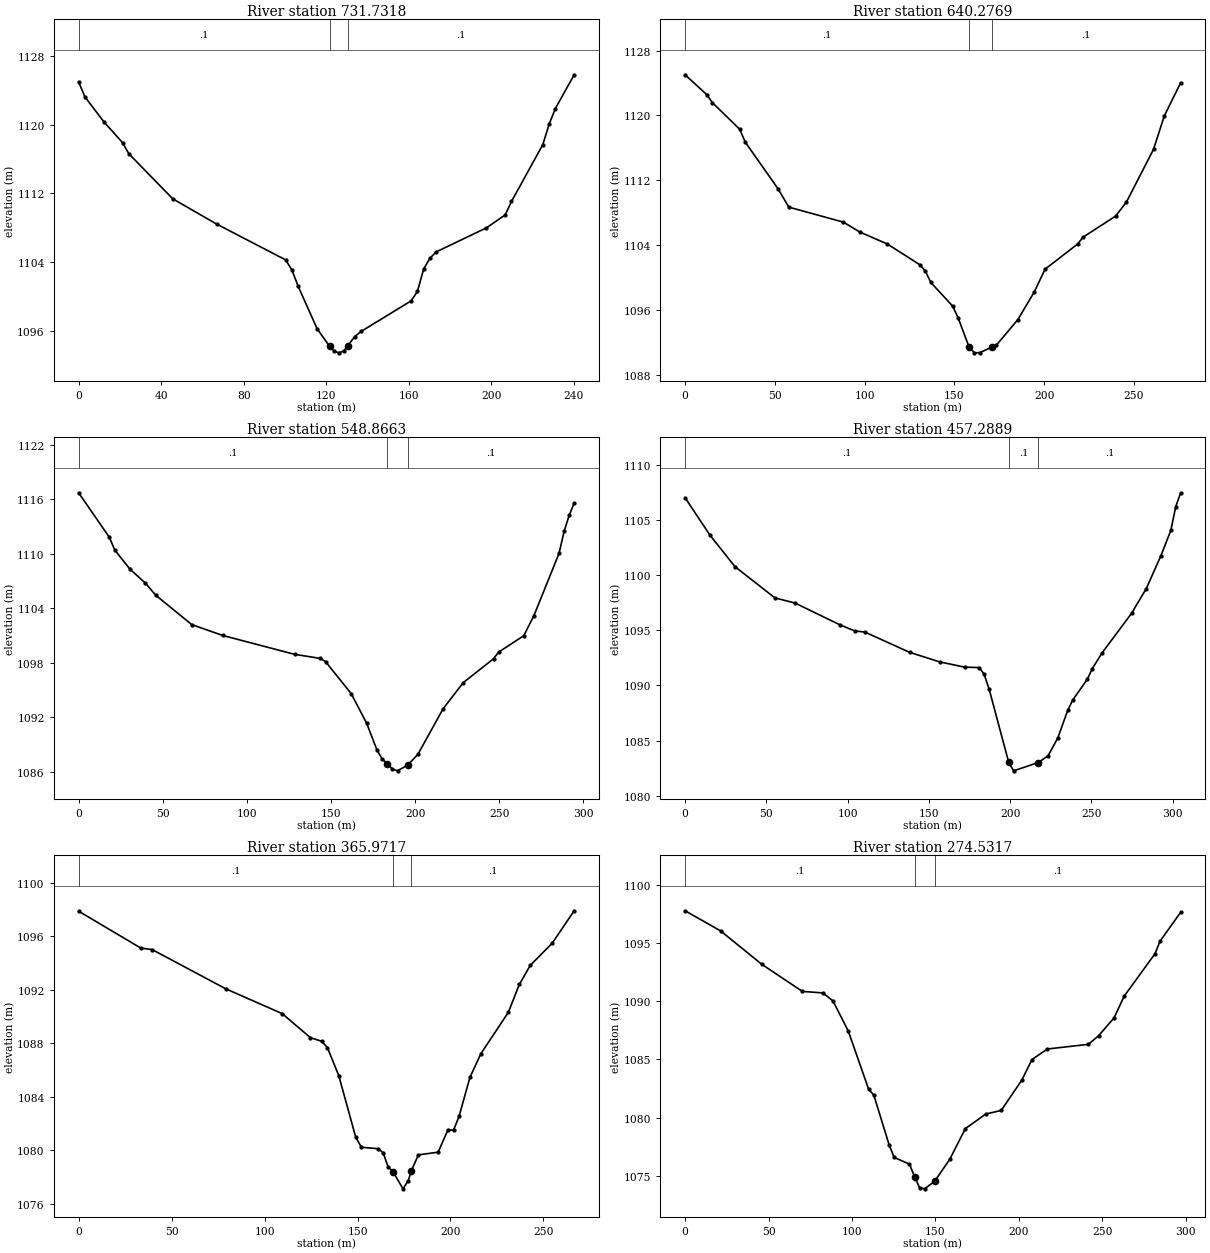
Type RM Length L Ch R = 1 ,731.7318,95.62,91.45,84.97
XS GIS Cut Line= 5
     642545.2839    4320852.1538     642428.9261    4320816.5982
     642422.4705    4320814.2417     642417.7318    4320811.8939
     642317.0804    4320777.4089
#Sta/Elev= 30
       0    1125    3.04 1123.28   12.17 1120.38   21.29 1117.93   24.33 1116.64
   45.63 1111.38   66.92 1108.43  100.38 1104.25  103.42 1103.06  106.46 1101.15
  115.59 1096.23  121.67 1094.16  123.96  1093.6  126.25 1093.41  128.54 1093.64
  130.39 1094.22  133.83  1095.3  136.87  1095.9  161.19 1099.47  164.23 1100.57
  167.27  1103.2  170.31 1104.45  173.35 1105.19  197.67 1107.99  206.79  1109.5
  209.83 1111.07  225.03 1117.71  228.07 1120.08   231.1 1121.91  240.22 1125.85
#Mann= 3 , 0 , 0
       0      .1       0  121.67      .1       0  130.39      .1       0
Bank Sta=121.67,130.39
XS Rating Curve= 0 ,0
Exp/Cntr=0.3,0.1

Type RM Length L Ch R = 1 ,640.2769,87.01,91.41,91.83
XS GIS Cut Line= 3
     642587.6174    4320770.1328     642436.0399    4320725.0083
     642320.3877    4320747.6432
#Sta/Elev= 30
       0 1125.01   12.17 1122.54   15.21 1121.57   30.41 1118.29   33.46 1116.72
    51.7 1110.97   57.79 1108.68    88.2 1106.83   97.32 1105.61  112.53 1104.15
  130.78 1101.57  133.82  1100.8  136.86 1099.39  149.03 1096.47  152.07 1095.03
  158.15 1091.43  161.17 1090.71   164.2 1090.74   170.7  1091.4  173.26 1091.62
  185.35 1094.82  194.41 1098.19  200.46 1101.02  218.59 1104.13  221.61 1104.97
  239.74 1107.57  245.78  1109.3  260.89 1115.81  266.93 1119.95     276 1124.02
#Mann= 3 , 0 , 0
       0      .1       0  158.15      .1       0   170.7      .1       0
Bank Sta=158.15,170.7
XS Rating Curve= 0 ,0
Exp/Cntr=0.3,0.1

Type RM Length L Ch R = 1 ,548.8663,96.27,91.58,89.58
XS GIS Cut Line= 3
     642635.2425     4320637.907     642439.6194    4320641.0092
     642340.8929    4320635.9227
#Sta/Elev= 30
       0 1116.72   18.34  1111.8    21.4 1110.44   30.57  1108.3   39.74 1106.77
   45.85 1105.44   67.25 1102.21    85.6 1101.02  128.39 1098.94  143.68 1098.49
  146.74 1098.14  162.02 1094.61  171.19 1091.35  177.31 1088.41  180.36 1087.44
  183.42 1086.88  186.48 1086.33  189.53 1086.12  195.65 1086.76  201.64 1087.94
  216.62 1092.95   228.6 1095.83  246.57 1098.45  249.57 1099.18  264.55 1100.99
  270.54 1103.18  285.52 1110.05  288.51 1112.46  291.51 1114.22  294.51 1115.59
#Mann= 3 , 0 , 0
       0      .1       0  183.42      .1       0  195.65      .1       0
Bank Sta=183.42,195.65
XS Rating Curve= 0 ,0
Exp/Cntr=0.3,0.1

Type RM Length L Ch R = 1 ,457.2889,67.97,91.32,104.16
XS GIS Cut Line= 3
     642624.6591    4320614.7559     642471.4633    4320536.6414
     642349.4919    4320589.6205
#Sta/Elev= 30
       0    1107   15.35  1103.6   30.71 1100.76   55.27 1097.93   67.56 1097.47
   95.19  1095.5  104.41 1094.94  110.55 1094.84  138.18    1093  156.61 1092.14
  171.96 1091.66  181.03 1091.62  184.05    1091  187.07 1089.68  199.16 1083.03
  202.18 1082.27   217.3 1083.02  223.34 1083.63  229.39 1085.26  235.43 1087.74
  238.45 1088.66  247.52 1090.57  250.54 1091.52  256.59 1092.95  274.72 1096.53
  283.79 1098.77  292.85 1101.77   298.9 1104.04  301.92 1106.19  304.94 1107.45
#Mann= 3 , 0 , 0
       0      .1       0  199.16      .1       0   217.3      .1       0
Bank Sta=199.16,217.3
XS Rating Curve= 0 ,0
Exp/Cntr=0.3,0.1

Type RM Length L Ch R = 1 ,365.9717,98.3,91.44,82.43
XS GIS Cut Line= 6
     642581.0028    4320582.3444     642444.4391    4320496.7085
     642443.2204    4320486.3219     642444.5469    4320478.0092
     642444.4391    4320459.4022     642393.1482    4320414.9951
#Sta/Elev= 30
       0 1097.86   33.46  1095.1   39.54 1094.99   79.08 1092.06  109.49  1090.2
   124.7  1088.4  130.78 1088.13  133.82 1087.65   139.9 1085.57  149.03 1080.96
  152.07 1080.21  161.19  1080.1  163.81 1079.79  166.42 1078.75  169.04 1078.39
  174.46  1077.1  177.26 1077.71  179.02 1078.47  182.73 1079.64  193.36 1079.84
  198.68 1081.53  201.63 1081.48  204.58 1082.51  210.47 1085.44  216.37 1087.21
  231.12  1090.3  237.02 1092.38  242.92 1093.81  254.72 1095.47  266.52 1097.89
#Mann= 3 , 0 , 0
       0      .1       0  169.04      .1       0  179.02      .1       0
Bank Sta=169.04,179.02
XS Rating Curve= 0 ,0
Exp/Cntr=0.3,0.1

Type RM Length L Ch R = 1 ,274.5317,95.32,91.44,85.1
XS GIS Cut Line= 5
     642596.2163    4320570.8879     642529.8635    4320450.3793
      642525.503    4320446.2478     642518.1549    4320440.9503
      642421.591    4320333.5562
#Sta/Elev= 30
       0 1097.77    21.4 1096.03   45.86 1093.18   70.31 1090.84   82.54 1090.71
   88.66 1090.02   97.83 1087.43  110.05 1082.42  113.11 1081.94  122.28 1077.66
  125.34 1076.57  134.51 1075.99  137.57 1074.91  140.57 1073.96  143.58 1073.87
  149.61 1074.52  158.78 1076.44     168 1079.05  180.29  1080.3  189.51 1080.61
   201.8  1083.2  207.94 1084.98  217.16 1085.89  241.75 1086.29  247.89 1087.03
  257.11 1088.56  263.26 1090.44  281.69 1094.08  284.77 1095.17  297.06 1097.64
#Mann= 3 , 0 , 0
       0      .1       0  137.57      .1       0  149.61      .1       0
Bank Sta=137.57,149.61
XS Rating Curve= 0 ,0
Exp/Cntr=0.3,0.1

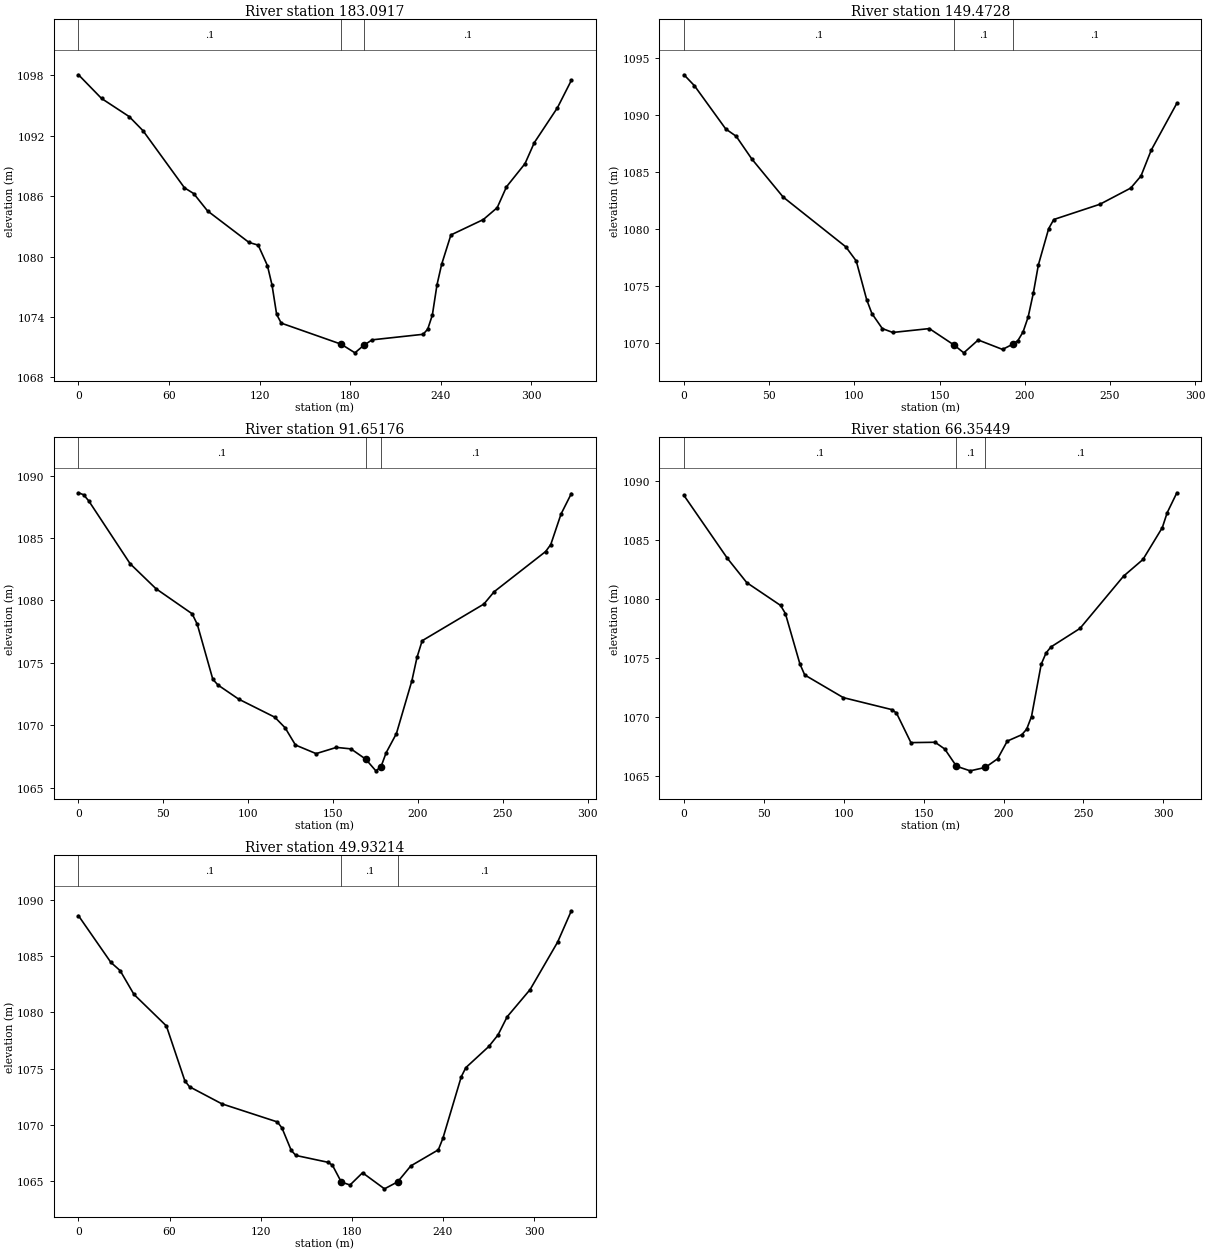
Type RM Length L Ch R = 1 ,183.0917,38.96,33.62,35
XS GIS Cut Line= 5
     642712.8978    4320466.1127     642561.6327    4320362.9448
     642550.5313    4320360.5124     642529.1159    4320358.8526
      642427.941    4320314.5062
#Sta/Elev= 30
       0 1098.04   15.26 1095.69   33.57 1093.89   42.72 1092.49   70.19 1086.82
   76.29 1086.25   85.45 1084.53  112.91  1081.4  119.01 1081.13  125.12  1079.1
  128.17 1077.17  131.22 1074.26  134.27 1073.39  173.94  1071.3   183.1 1070.44
  188.85 1071.18  194.46 1071.73  228.22 1072.28  231.28 1072.79  234.35 1074.19
  237.42 1077.19  240.49 1079.22  246.63 1082.14  268.11 1083.67  277.31 1084.85
  283.45 1086.92  295.72 1089.22  301.86  1091.3   317.2 1094.77  326.41 1097.49
#Mann= 3 , 0 , 0
       0      .1       0  173.94      .1       0  188.85      .1       0
Bank Sta=173.94,188.85
XS Rating Curve= 0 ,0
Exp/Cntr=0.3,0.1

Type RM Length L Ch R = 1 ,149.4728,51.23,57.82,59.93
XS GIS Cut Line= 4
     642690.1967    4320442.7292     642587.5381    4320333.1915
     642554.2006    4320327.3706     642461.0671     4320278.158
#Sta/Elev= 30
       0 1093.52    6.13 1092.56   24.51 1088.76   30.64 1088.12   39.83 1086.12
   58.21 1082.78   94.98 1078.41   101.1 1077.17  107.23 1073.77   110.3 1072.55
  116.42 1071.23  122.55 1070.89     144 1071.23  158.58 1069.78  164.23  1069.1
  172.69 1070.23  186.98  1069.4  192.99 1069.86     196 1070.18  199.01 1070.93
  202.02 1072.25  205.03 1074.33  208.04 1076.84  214.06 1080.01  217.07 1080.81
  244.16 1082.15  262.22 1083.57  268.24 1084.63  274.25  1086.9   289.3 1091.02
#Mann= 3 , 0 , 0
       0      .1       0  158.58      .1       0  192.99      .1       0
Bank Sta=158.58,192.99
XS Rating Curve= 0 ,0
Exp/Cntr=0.3,0.1

Type RM Length L Ch R = 1 ,91.65176,22.15,25.3,28.33
XS GIS Cut Line= 5
     642674.7977    4320423.2501     642606.9036    4320290.4577
     642592.2804    4320281.6575     642585.5548    4320275.6804
     642477.1536    4320236.7185
#Sta/Elev= 30
       0 1088.63    3.04 1088.47    6.09 1087.97   30.44 1082.94   45.66 1080.94
   66.96 1078.93   70.01 1078.08   79.14 1073.68   82.18 1073.22   94.36 1072.09
  115.66 1070.64  121.75 1069.79  127.84 1068.41  140.01 1067.72  151.99 1068.22
  160.52  1068.1  169.21 1067.28  175.21 1066.34  178.24 1066.67  181.27 1067.79
  187.33 1069.33  196.43 1073.56  199.46 1075.44  202.49 1076.77  238.86 1079.71
  244.93  1080.7  275.24 1083.92  278.27 1084.48  284.33 1086.93   290.4 1088.57
#Mann= 3 , 0 , 0
       0      .1       0  169.21      .1       0  178.24      .1       0
Bank Sta=169.21,178.24
XS Rating Curve= 0 ,0
Exp/Cntr=0.3,0.1

Type RM Length L Ch R = 1 ,66.35449,19.5,16.42,15.99
XS GIS Cut Line= 6
     642677.9994    4320419.1283      642608.943    4320267.9186
     642602.8576    4320256.5944     642600.1059    4320253.2078
     642589.5225    4320246.0111      642479.244    4320225.2677
#Sta/Elev= 30
       0 1088.74    27.2 1083.41   39.29 1081.36   60.45 1079.43   63.47 1078.74
   72.54 1074.48   75.56 1073.54   99.74 1071.62  129.96 1070.61  132.99 1070.32
  142.05 1067.81  157.17 1067.84  163.21 1067.27  170.54 1065.81  179.14 1065.42
  188.62 1065.71   196.3 1066.44  202.37 1067.94  211.46 1068.48   214.5 1068.95
  217.53 1070.02   223.6 1074.45  226.63  1075.4  229.66 1075.91  247.86 1077.48
  275.15 1081.91  287.28 1083.32  299.41 1086.02  302.45 1087.28  308.51 1088.97
#Mann= 3 , 0 , 0
       0      .1       0  170.54      .1       0  188.62      .1       0
Bank Sta=170.54,188.62
XS Rating Curve= 0 ,0
Exp/Cntr=0.3,0.1

Type RM Length L Ch R = 1 ,49.93214,34.32,49.93,27.43
XS GIS Cut Line= 6
     642679.9838    4320417.1968      642627.993    4320264.3997
     642615.6899    4320248.4188     642612.9382    4320243.7621
     642589.2315    4320222.5954     642483.8213    4320214.6579
#Sta/Elev= 30
       0  1088.6   21.32 1084.45   27.41 1083.72   36.54  1081.6   57.86  1078.8
   70.04 1073.91   73.09 1073.39    94.4 1071.87  130.95 1070.26  133.99 1069.72
  140.08 1067.73  143.13 1067.28  164.31 1066.67  167.21 1066.41  173.03 1064.92
  178.78 1064.65  187.03 1065.74  201.48 1064.31  210.14 1064.93  218.81 1066.35
  236.93 1067.78  239.95 1068.81  252.03 1074.28  255.05 1075.09  270.16 1076.97
   276.2 1077.99  282.24 1079.61  297.34 1082.03  315.46 1086.25  324.52 1089.04
#Mann= 3 , 0 , 0
       0      .1       0  173.03      .1       0  210.14      .1       0
Bank Sta=173.03,210.14
XS Rating Curve= 0 ,0
Exp/Cntr=0.3,0.1

River Reach=Red Creek       ,6
Reach XY= 30
     644352.9362    4325750.7263     644973.7154    4325409.9152
     645166.2001    4325069.7926     645185.2502    4324761.4201
     645288.4379    4324597.5104       645152.71    4324542.6275
     645082.8562     4324282.391     644901.0871     4324110.147
     644657.0085    4324070.8562     644403.1132    4323877.8494
     644397.4517    4323781.5338     644289.8984    4323843.4464
     644078.7605    4323298.1391     643966.8415     4323177.092
     643920.0101    4323215.9858     643931.2279    4322419.7278
     643804.5193    4321986.4646     643684.2659    4321944.3957
     643589.4126    4321770.1673     643682.2815    4321619.7513
     643596.1353    4321525.4823     643762.4502     4321303.979
     643592.1907    4321119.6878     643352.4777    4321093.8909
     643484.2405    4320922.0437     643383.8309    4320880.7686
     643226.2712    4320473.9709     643031.4052    4320337.0488
     642750.4172    4320324.3488     642638.3306    4320206.7709

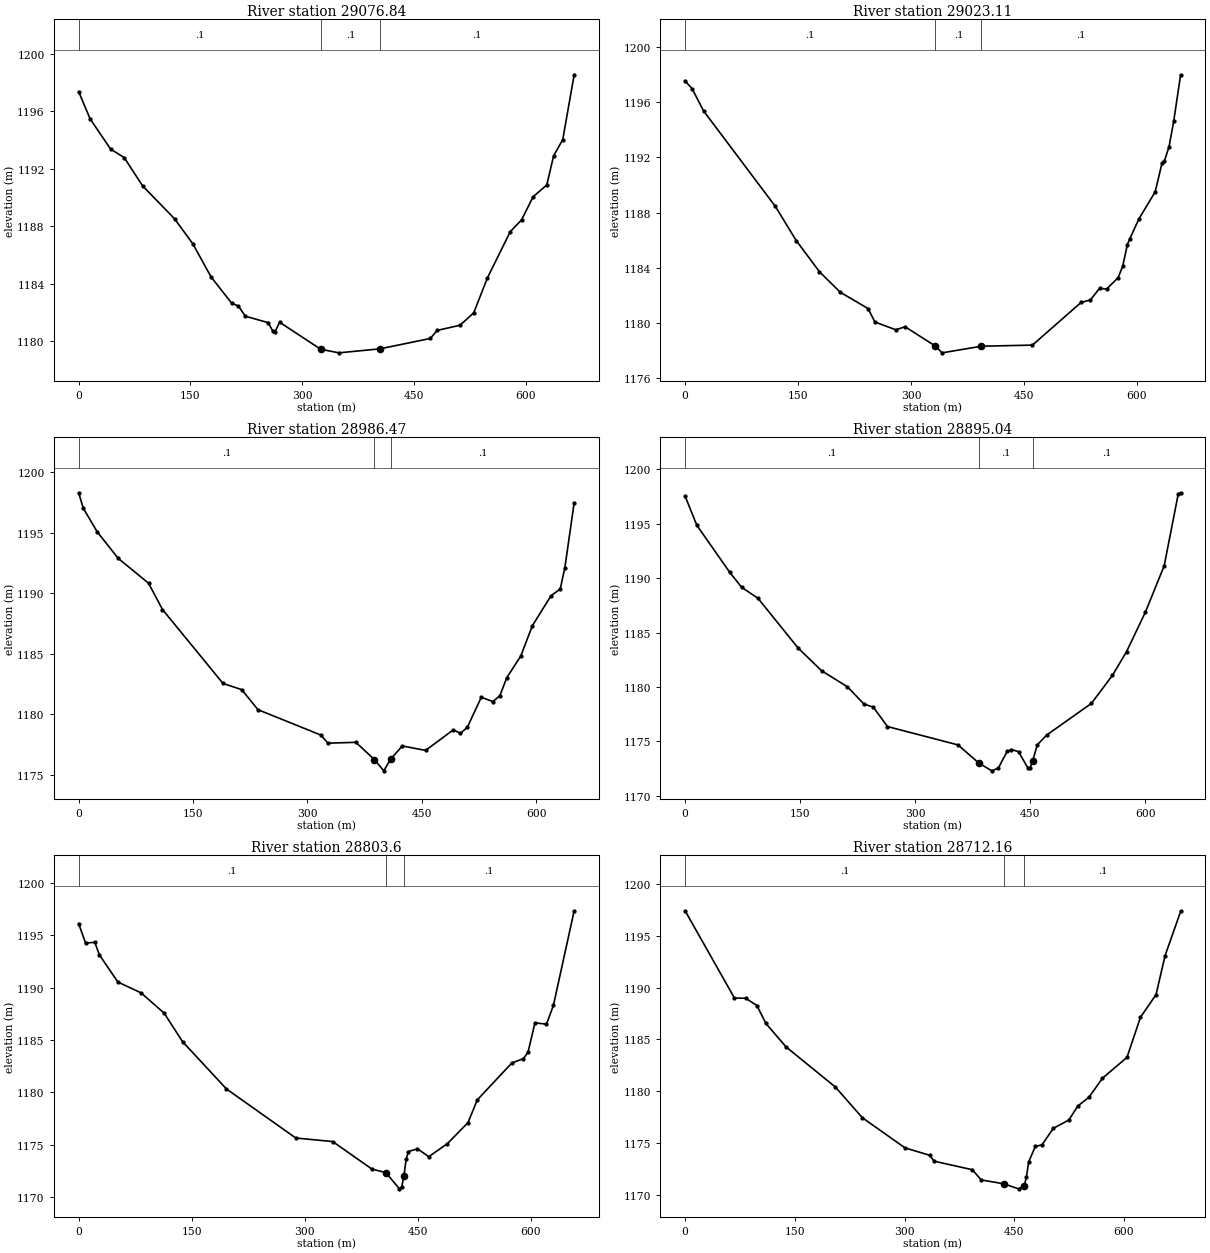
Type RM Length L Ch R = 1 ,29076.84,56.83,53.73,54.22
XS GIS Cut Line= 2
     644571.2864    4326069.6649     644287.6525    4325468.5304
#Sta/Elev= 30
       0 1197.36   15.32 1195.47   42.88 1193.36   61.26 1192.76   85.77  1190.8
  128.65 1188.51  153.15 1186.77  177.66 1184.46  205.23 1182.64  214.42 1182.43
  223.61 1181.73  254.24 1181.28  260.36  1180.7  263.43 1180.64  269.55 1181.31
  324.69 1179.43  349.19 1179.18  404.33 1179.46  471.71 1180.18   480.9 1180.74
  511.53  1181.1  529.91 1181.96  548.29 1184.39  578.92 1187.61  594.24 1188.44
  609.55 1190.04  627.93 1190.86  637.12 1192.89  649.37 1194.02  664.69 1198.53
#Mann= 3 , 0 , 0
       0      .1       0  324.69      .1       0  404.33      .1       0
Bank Sta=324.69,404.33
XS Rating Curve= 0 ,0
Exp/Cntr=0.3,0.1

Type RM Length L Ch R = 1 ,29023.11,36.46,36.63,37.3
XS GIS Cut Line= 2
      644604.705    4326063.3893      644355.467    4325454.5818
#Sta/Elev= 30
       0 1197.54    9.22 1196.99   24.59 1195.37  119.89 1188.45  147.56 1185.98
   178.3 1183.73  205.96 1182.24  242.85 1181.06  252.07 1180.08  279.74 1179.52
  292.04 1179.74     332 1178.35  341.22 1177.85  393.48 1178.33  461.11 1178.41
  525.67  1181.5  537.96 1181.68  550.26 1182.52  559.48 1182.47  574.85 1183.29
     581 1184.14  587.15 1185.69  590.22 1186.09  602.52 1187.56  624.04 1189.51
  633.26 1191.62  636.33 1191.74  642.48 1192.79  648.63 1194.62  657.85 1197.99
#Mann= 3 , 0 , 0
       0      .1       0     332      .1       0  393.48      .1       0
Bank Sta=332,393.48
XS Rating Curve= 0 ,0
Exp/Cntr=0.3,0.1

Type RM Length L Ch R = 1 ,28986.47,93.68,91.43,89.19
XS GIS Cut Line= 3
     644624.2031    4326059.0815     644489.6626    4325685.6298
     644418.8861    4325443.1303
#Sta/Elev= 30
       0 1198.32    6.11 1197.04   24.43 1195.08   51.91 1192.89    91.6 1190.84
  109.92 1188.66  189.31 1182.54  213.74 1182.03  235.11 1180.37  317.56 1178.27
  326.72  1177.6  363.36 1177.67  387.79 1176.24  399.99 1175.31  409.12 1176.29
  424.34 1177.37  454.78    1177   491.3 1178.71  500.43 1178.41  509.56 1178.92
  527.82  1181.4  543.04 1181.04  552.17 1181.53   561.3 1183.03  579.56 1184.81
  594.78 1187.32  619.13 1189.79   631.3 1190.36  637.39 1192.13  649.56  1197.5
#Mann= 3 , 0 , 0
       0      .1       0  387.79      .1       0  409.12      .1       0
Bank Sta=387.79,409.12
XS Rating Curve= 0 ,0
Exp/Cntr=0.3,0.1

Type RM Length L Ch R = 1 ,28895.04,86.46,91.44,102.73
XS GIS Cut Line= 5
     644713.1033    4326018.8648     644590.4116    4325665.0563
     644570.4513    4325644.7462     644553.2987    4325629.8213
     644463.3361    4325428.3136
#Sta/Elev= 30
       0 1197.54   15.35 1194.86   58.32 1190.53   73.67 1189.17   95.15 1188.15
  147.34 1183.59  178.03  1181.5  211.79 1180.02  233.28 1178.44  245.56 1178.15
  263.98 1176.37  356.06 1174.68  383.02 1173.02  400.11  1172.3  408.64 1172.56
  420.01 1174.08  425.69 1174.26  434.89 1174.06  447.15 1172.56  450.21  1172.6
  453.28 1173.21  459.41 1174.69  471.67 1175.59   529.9 1178.49  557.48 1181.08
  575.87 1183.26  600.39 1186.88  624.91 1191.14   643.3 1197.76  646.37 1197.85
#Mann= 3 , 0 , 0
       0      .1       0  383.02      .1       0  453.28      .1       0
Bank Sta=383.02,453.28
XS Rating Curve= 0 ,0
Exp/Cntr=0.3,0.1

Type RM Length L Ch R = 1 ,28803.6 ,95.53,91.44,87.75
XS GIS Cut Line= 4
     644742.7367    4326006.1648     644633.9892    4325613.4632
     644647.4455     4325558.143     644564.9363    4325383.8635
#Sta/Elev= 30
       0 1196.11    9.19 1194.25   21.45 1194.32   27.57 1193.12   52.08 1190.53
   82.72  1189.5  113.36 1187.57  137.87 1184.84  196.08 1180.33  287.99 1175.65
  337.01 1175.31   389.1 1172.68  407.48 1172.35  425.46  1170.8  428.46 1170.95
  431.45 1172.05  434.45 1173.64  437.45 1174.36  449.43 1174.62  464.41 1173.87
   488.9  1175.1  516.45 1177.12  528.69 1179.28   574.6 1182.81   589.9 1183.22
  596.02 1183.83  605.21 1186.64  620.51 1186.51  629.69  1188.3  657.24 1197.33
#Mann= 3 , 0 , 0
       0      .1       0  407.48      .1       0  431.45      .1       0
Bank Sta=407.48,431.45
XS Rating Curve= 0 ,0
Exp/Cntr=0.3,0.1

Type RM Length L Ch R = 1 ,28712.16,102.4,91.44,97.93
XS GIS Cut Line= 5
     644825.2869    4325995.5814     644719.7534    4325563.4958
     644713.1723    4325557.3805     644708.6681    4325552.3304
     644586.1031    4325373.2802
#Sta/Elev= 30
       0 1197.42   67.48 1188.99   82.82 1188.97   98.16 1188.27  110.43 1186.54
  138.04 1184.27  205.52 1180.39  242.33 1177.43  300.61 1174.52  334.36  1173.8
  340.49 1173.23  392.64 1172.41  404.91 1171.42  435.58 1171.05  455.95 1170.56
  463.59 1170.86  466.65 1171.67  469.71 1173.16  478.87 1174.66  488.04 1174.81
  503.32  1176.4  524.72 1177.21  536.94 1178.56  552.22 1179.41  570.56 1181.24
  604.17 1183.26  622.51 1187.12   643.9 1189.32  656.13 1193.06  677.52 1197.36
#Mann= 3 , 0 , 0
       0      .1       0  435.58      .1       0  463.59      .1       0
Bank Sta=435.58,463.59
XS Rating Curve= 0 ,0
Exp/Cntr=0.3,0.1