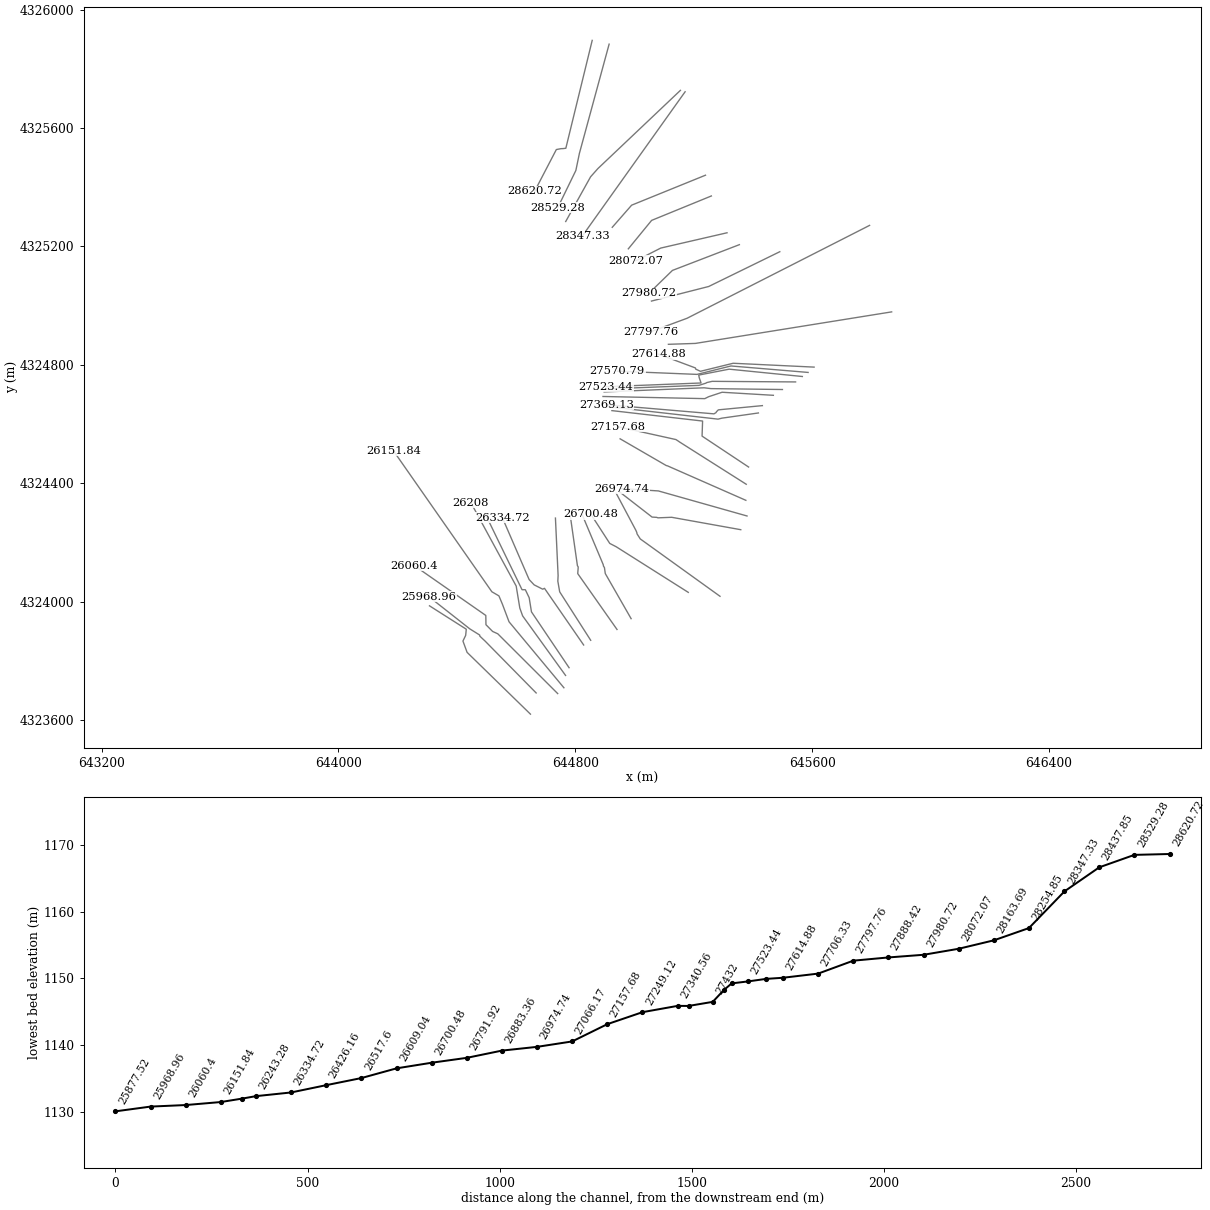
HEC-RAS study RedCreek.prj: RedCreek

--- RedCreek.g01 (geometry) --- (continued)

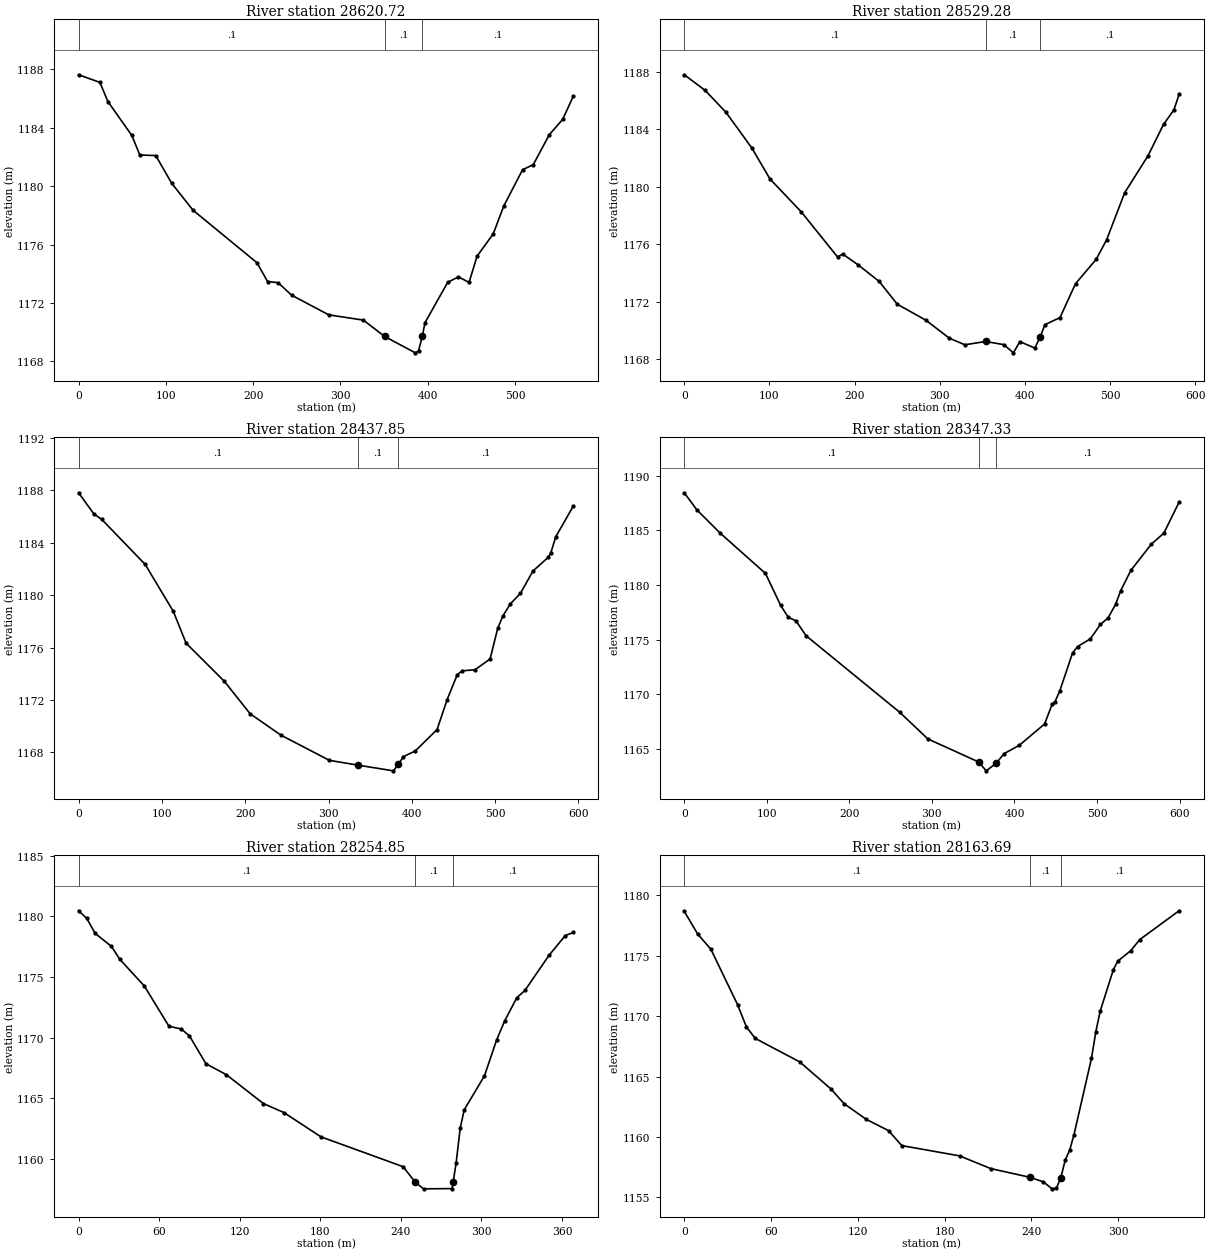
Type RM Length L Ch R = 1 ,28620.72,101.71,91.44,99.43
XS GIS Cut Line= 6
     644857.0369    4325896.0979     644767.9926    4325531.7391
     644758.9021    4325530.6294     644751.6619    4325530.3545
      644735.925    4325527.3999     644662.3032    4325385.9802
#Sta/Elev= 30
       0 1187.62    24.4  1187.1   33.54 1185.79   60.99 1183.47   70.14 1182.13
   88.43 1182.09  106.73 1180.19  131.13 1178.35  204.31 1174.76  216.51 1173.47
  228.71 1173.39  243.96 1172.54  286.65 1171.19  326.29 1170.83  350.69 1169.71
  385.84 1168.59  389.48 1168.72  393.84 1169.72  396.86 1170.65  422.86 1173.41
  435.13 1173.79  447.39 1173.41  456.59 1175.21  474.98 1176.72  487.25 1178.65
  508.71 1181.12  520.98 1181.47  539.37 1183.52   554.7 1184.57  566.97 1186.17
#Mann= 3 , 0 , 0
       0      .1       0  350.69      .1       0  393.84      .1       0
Bank Sta=350.69,393.84
XS Rating Curve= 0 ,0
Exp/Cntr=0.3,0.1

Type RM Length L Ch R = 1 ,28529.28,93.33,91.44,91.1
XS GIS Cut Line= 6
      644914.187    4325883.3979     644813.2375    4325512.3759
     644813.0301    4325510.3011      644812.627    4325508.6683
     644801.8392     4325456.744       644740.62    4325330.9468
#Sta/Elev= 30
       0  1187.8   24.41 1186.72   48.83  1185.2   79.34 1182.71  100.71 1180.55
  137.33 1178.27  180.05 1175.13  186.15 1175.33  204.46 1174.57  228.88 1173.43
  250.24 1171.84  283.81 1170.73  311.27 1169.48  329.58 1169.02  353.99 1169.25
  375.36 1169.03   386.6 1168.46  394.17 1169.24  411.85 1168.79  417.74 1169.53
  423.63 1170.42  441.31 1170.91  459.56 1173.27  483.89 1174.97  496.06 1176.32
  517.34  1179.6  544.72 1182.17  562.97 1184.35  575.13 1185.36  581.21 1186.44
#Mann= 3 , 0 , 0
       0      .1       0  353.99      .1       0  417.74      .1       0
Bank Sta=353.99,417.74
XS Rating Curve= 0 ,0
Exp/Cntr=0.3,0.1

Type RM Length L Ch R = 1 ,28437.85,89.58,90.52,90.92
XS GIS Cut Line= 4
     645154.9584    4325727.2934      644876.293    4325463.1541
     644851.5916    4325435.3292     644767.6076      4325284.38
#Sta/Elev= 30
       0 1187.81   18.43 1186.19   27.64 1185.79   79.86 1182.35  113.65 1178.77
  129.01 1176.34  175.08 1173.42   205.8 1170.96  242.66 1169.33  301.02  1167.4
  334.81 1167.04  377.81  1166.6  383.96  1167.1  389.68 1167.68  403.99 1168.11
  430.26 1169.75  442.38 1172.04   454.5 1173.94  460.56 1174.23  475.71 1174.31
   493.9 1175.13  502.99 1177.46  509.05 1178.39  518.14 1179.33  530.26 1180.13
  545.42 1181.85   563.6 1182.88  566.63 1183.19  572.69 1184.45  593.91 1186.81
#Mann= 3 , 0 , 0
       0      .1       0  334.81      .1       0  383.96      .1       0
Bank Sta=334.81,383.96
XS Rating Curve= 0 ,0
Exp/Cntr=0.3,0.1

Type RM Length L Ch R = 1 ,28347.33,94.76,92.47,109.9
XS GIS Cut Line= 2
     645170.8334    4325722.5309     644822.9056    4325234.3736
#Sta/Elev= 30
       0 1188.45   15.37 1186.88   43.04 1184.79   98.37 1181.07  116.82 1178.14
  126.04 1177.05  135.26 1176.74  147.56 1175.37   261.3 1168.35  295.12 1165.93
   356.6 1163.82  365.82 1163.01  378.12 1163.72  387.34 1164.58  405.79 1165.34
  436.53  1167.3  445.75 1169.12  448.83 1169.28  454.97 1170.33  470.35 1173.79
  476.49 1174.38  491.86 1175.08  504.16  1176.4  513.38    1177  522.61 1178.25
  528.75  1179.5  541.05 1181.35  565.64 1183.73  581.01 1184.76  599.46 1187.59
#Mann= 3 , 0 , 0
       0      .1       0   356.6      .1       0  378.12      .1       0
Bank Sta=356.6,378.12
XS Rating Curve= 0 ,0
Exp/Cntr=0.3,0.1

Type RM Length L Ch R = 1 ,28254.85,89.14,91.16,96.91
XS GIS Cut Line= 3
     645239.6252    4325440.7491     644990.2453    4325339.5352
     644924.7704    4325264.8008
#Sta/Elev= 30
       0 1180.46    6.12 1179.83   12.23 1178.61   24.47 1177.52   30.58 1176.47
   48.93 1174.26   67.28 1170.94   76.46 1170.71   82.58 1170.14   94.81 1167.85
   110.1 1166.94  137.63 1164.56  152.92 1163.82  180.44 1161.82  241.61 1159.36
  250.79 1158.07   256.9 1157.53  278.17 1157.55  278.92 1158.08  281.18 1159.68
  284.19 1162.54   287.2 1164.05  302.26 1166.85  311.29  1169.8  317.31 1171.38
  326.34 1173.29  332.37 1173.89  350.43  1176.8  362.47 1178.42   368.5 1178.67
#Mann= 3 , 0 , 0
       0      .1       0  250.79      .1       0  278.92      .1       0
Bank Sta=250.79,278.92
XS Rating Curve= 0 ,0
Exp/Cntr=0.3,0.1

Type RM Length L Ch R = 1 ,28163.69,95.46,91.62,85.56
XS GIS Cut Line= 3
      645259.469    4325370.6343     645057.6748    4325288.1316
     644979.0101    4325192.0402
#Sta/Elev= 30
       0 1178.67    9.21 1176.81   18.42 1175.53   36.85 1170.95   42.99  1169.1
   49.13 1168.15   79.83 1166.21  101.33 1163.98  110.54 1162.75  125.89 1161.45
  141.24 1160.52  150.46 1159.28  190.37 1158.43  211.87 1157.38  239.21 1156.65
   248.3 1156.28  254.35  1155.7  257.38 1155.76  260.41 1156.63  263.44 1158.08
  266.47 1158.88   269.5 1160.18  281.61 1166.51  284.64 1168.72  287.67 1170.43
  296.76 1173.85  299.79 1174.55  308.87 1175.43  314.93 1176.33  342.19 1178.72
#Mann= 3 , 0 , 0
       0      .1       0  239.21      .1       0  260.41      .1       0
Bank Sta=239.21,260.41
XS Rating Curve= 0 ,0
Exp/Cntr=0.3,0.1

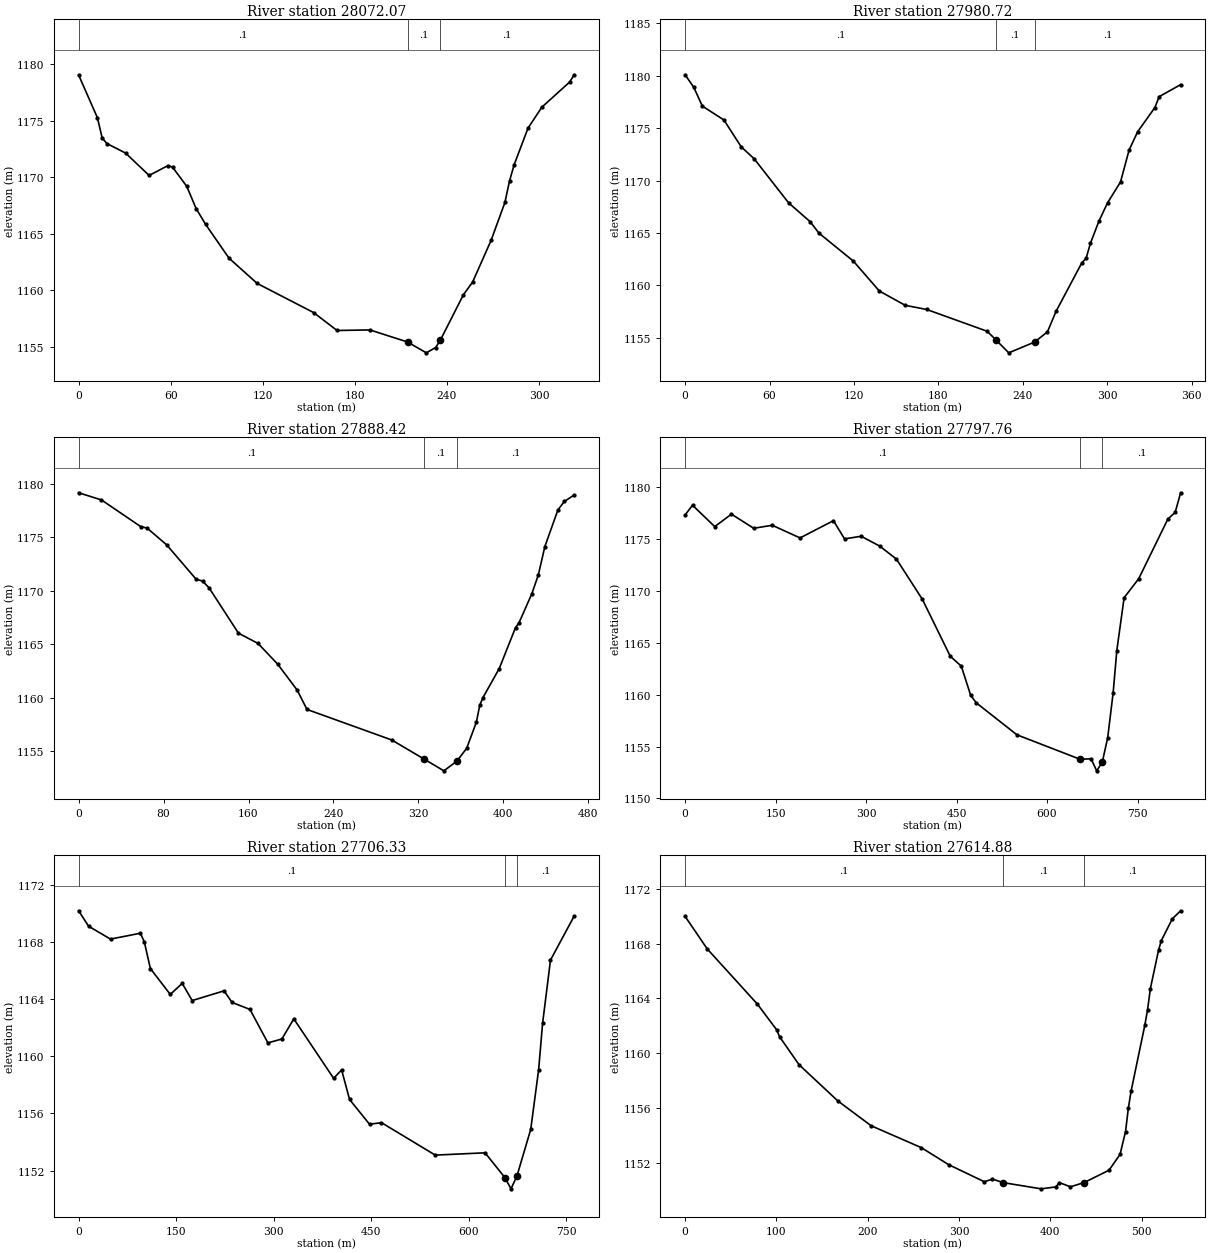
Type RM Length L Ch R = 1 ,28072.07,90.15,91.35,90.47
XS GIS Cut Line= 3
     645312.3858    4325246.2799     645088.5972     4325194.677
     645005.4685    4325152.3526
#Sta/Elev= 30
       0 1179.06   12.25 1175.27   15.31 1173.49   18.37 1172.99   30.62 1172.14
   45.93 1170.16   58.18 1171.03   61.24 1170.89   70.43  1169.2   76.55 1167.23
   82.68 1165.84   97.99 1162.83  116.36 1160.59  153.11 1158.01  168.42 1156.42
  189.85 1156.47  214.35  1155.4   226.6 1154.44  232.67 1154.91  235.68 1155.55
  250.72 1159.58  256.74 1160.71  268.78  1164.4  277.81 1167.77  280.82 1169.68
  283.83 1171.11  292.85 1174.35  301.88 1176.21  319.93 1178.43  322.94 1179.08
#Mann= 3 , 0 , 0
       0      .1       0  214.35      .1       0  235.68      .1       0
Bank Sta=214.35,235.68
XS Rating Curve= 0 ,0
Exp/Cntr=0.3,0.1

Type RM Length L Ch R = 1 ,27980.72,90.76,92.3,85.54
XS GIS Cut Line= 3
     645354.0908    4325206.1624     645128.0528    4325119.2065
     645049.2902    4325042.6496
#Sta/Elev= 30
       0  1180.1    6.13 1178.91   12.26 1177.11   27.59 1175.78   39.85 1173.22
   49.05 1172.08   73.58 1167.86    88.9 1166.06   95.04 1164.98  119.56  1162.3
  137.95 1159.45  156.35 1158.08  171.68 1157.68   214.6  1155.6  220.73 1154.79
  229.92 1153.54  248.29 1154.57  257.44 1155.55  263.54 1157.51  281.85 1162.14
   284.9 1162.57  287.95 1164.01  294.06 1166.14  300.16 1167.88  309.31 1169.86
  315.41 1172.91  321.51 1174.66  333.72 1176.97  336.77 1178.01  352.03 1179.16
#Mann= 3 , 0 , 0
       0      .1       0  220.73      .1       0  248.29      .1       0
Bank Sta=220.73,248.29
XS Rating Curve= 0 ,0
Exp/Cntr=0.3,0.1

Type RM Length L Ch R = 1 ,27888.42,89.83,90.65,87.85
XS GIS Cut Line= 3
     645490.6161    4325182.3498     645250.4949    4325064.8897
     645057.2277     4325015.662
#Sta/Elev= 30
       0 1179.18   21.51 1178.51   58.38 1176.02   64.52 1175.87   82.96  1174.3
  110.61 1171.09  116.76 1170.91   122.9 1170.27  150.55 1166.03  168.99 1165.07
  187.42 1163.14  205.86  1160.7  215.08 1158.89  294.93 1156.03  325.61 1154.23
  344.02 1153.14  356.29 1154.05   365.5 1155.25   374.7 1157.72  377.77 1159.27
  380.84    1160  396.18 1162.72  411.52 1166.56  414.59 1166.96  426.86 1169.72
     433 1171.49  439.13 1174.14  451.41 1177.57  457.54 1178.37  466.75 1178.97
#Mann= 3 , 0 , 0
       0      .1       0  325.61      .1       0  356.29      .1       0
Bank Sta=325.61,356.29
XS Rating Curve= 0 ,0
Exp/Cntr=0.3,0.1

Type RM Length L Ch R = 1 ,27797.76,92.69,91.44,89.77
XS GIS Cut Line= 3
     645793.8292      4325271.25     645177.5453    4324957.6225
     645055.6402    4324912.4743
#Sta/Elev= 30
       0 1177.31   12.29 1178.25   49.17 1176.19   76.83 1177.39  113.71 1176.03
  144.45 1176.32  190.55  1175.1  245.87 1176.76  264.31 1175.01  291.97 1175.26
   322.7 1174.31  350.36 1173.06  393.38 1169.18  439.48 1163.71  457.92 1162.74
  473.29 1159.96  482.51 1159.22  550.12 1156.13  654.62 1153.78  673.06 1153.82
  682.28 1152.66   691.5 1153.48  700.57 1155.85  709.64  1160.2  715.68 1164.25
  727.78 1169.34  751.96 1171.17  800.33 1176.92  812.42 1177.56  821.49 1179.45
#Mann= 3 , 0 , 0
       0      .1       0  654.62      .1       0   691.5      .1       0
Bank Sta=654.62,691.5
XS Rating Curve= 0 ,0
Exp/Cntr=0.3,0.1

Type RM Length L Ch R = 1 ,27706.33,94.91,91.45,89.02
XS GIS Cut Line= 3
     645868.4418    4324979.1494      645205.486    4324872.6282
     645114.3778    4324869.6117
#Sta/Elev= 30
       0 1170.18   15.33  1169.1   49.06  1168.2   95.05 1168.61  101.18 1167.99
  110.38 1166.14  141.04 1164.33  159.43  1165.1  174.76  1163.9  223.82 1164.58
  236.08 1163.77  263.68 1163.28  291.27 1160.94  312.73 1161.21  331.13 1162.62
  392.45 1158.46  404.72 1159.05  416.98 1156.98  447.64 1155.25  466.04 1155.36
  548.82 1153.09  625.47 1153.25  656.13 1151.51  665.33 1150.73   674.5 1151.62
  695.77 1154.89  707.92 1159.06     714  1162.3  726.16 1166.73  762.62 1169.81
#Mann= 3 , 0 , 0
       0      .1       0  656.13      .1       0   674.5      .1       0
Bank Sta=656.13,674.5
XS Rating Curve= 0 ,0
Exp/Cntr=0.3,0.1

Type RM Length L Ch R = 1 ,27614.88,43.09,44.1,42.46
XS GIS Cut Line= 6
     645606.5038    4324792.6178     645333.0438    4324805.6083
     645222.5428    4324778.4183     645206.6677    4324785.8267
     645205.6094    4324789.7954     645081.3048    4324836.2742
#Sta/Elev= 30
       0 1169.98   24.34  1167.6   79.09 1163.59  100.38  1161.7  103.42 1161.21
  124.72 1159.17   167.3 1156.52  203.81 1154.71  258.56 1153.12  288.74 1151.87
  327.67 1150.63  336.66 1150.82  348.63 1150.56  390.03 1150.11   405.9 1150.25
  410.01 1150.56  422.07 1150.26  437.15 1150.57   464.3 1151.47  476.36 1152.62
  482.39 1154.29  485.41 1155.97  488.43 1157.23  503.51 1162.05  506.52 1163.18
  509.54  1164.7  518.59 1167.54   521.6 1168.22  533.67 1169.81  542.72 1170.39
#Mann= 3 , 0 , 0
       0      .1       0  348.63      .1       0  437.15      .1       0
Bank Sta=348.63,437.15
XS Rating Curve= 0 ,0
Exp/Cntr=0.3,0.1

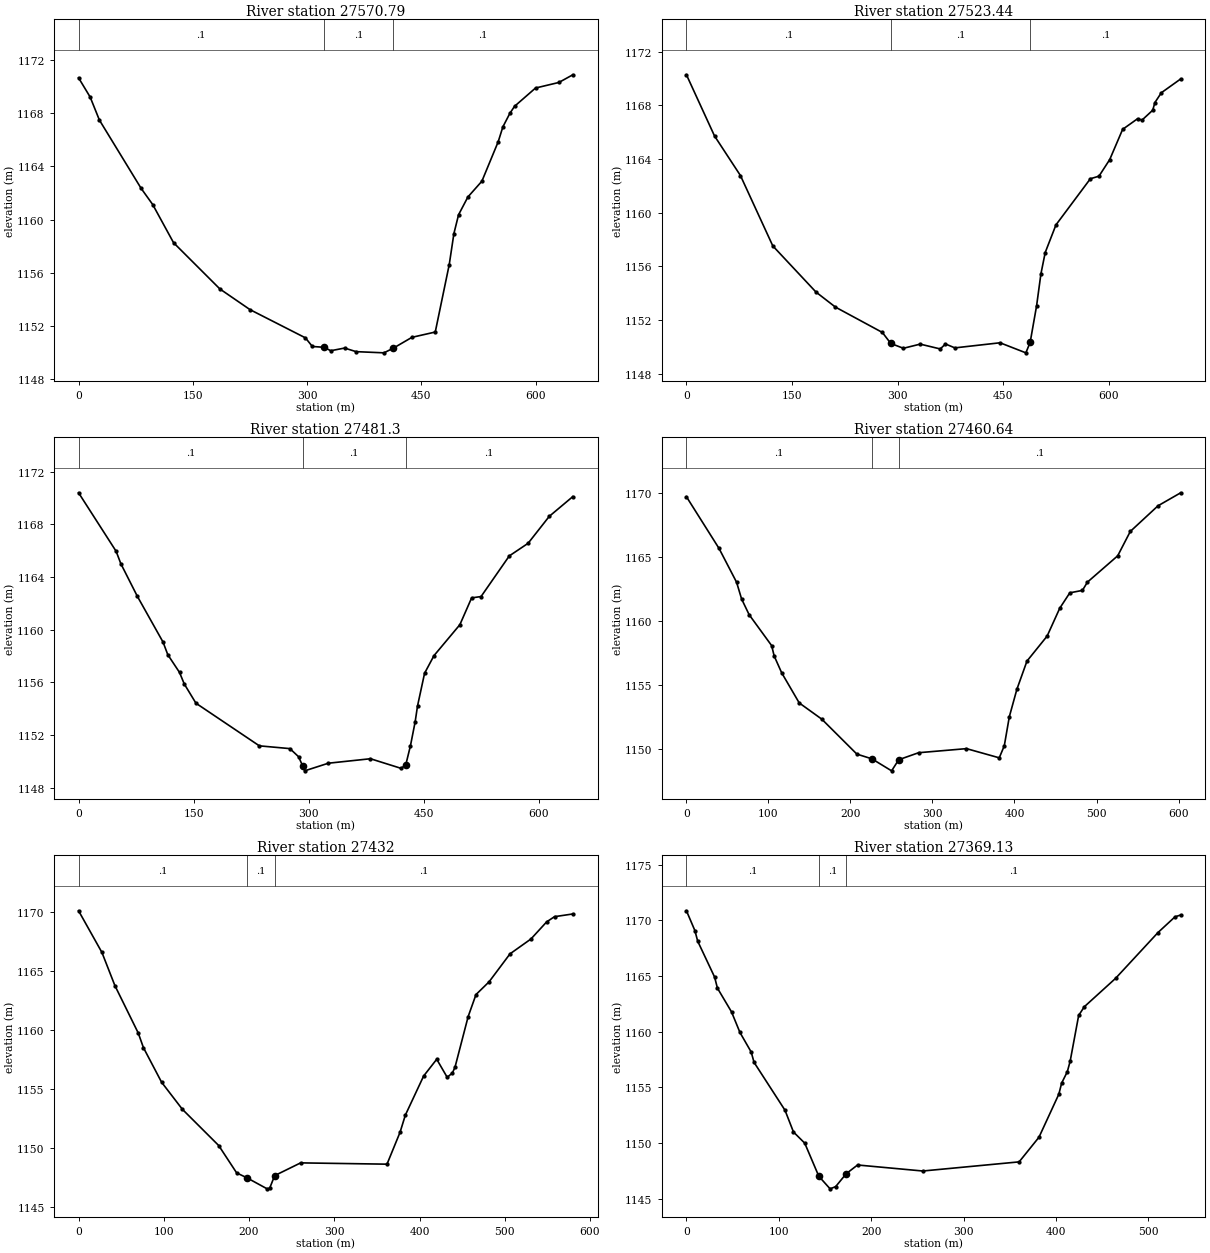
Type RM Length L Ch R = 1 ,27570.79,38.14,47.34,64.72
XS GIS Cut Line= 4
     645586.2295    4324774.6366     645325.6144    4324796.4647
     645211.1819     4324768.022     644942.0505     4324778.936
#Sta/Elev= 30
       0 1170.69   15.21 1169.24   27.37  1167.5   82.11 1162.35   97.31 1161.13
  124.68 1158.25   185.5 1154.76  225.04  1153.2  297.81 1151.07  306.88 1150.42
     322 1150.36  331.07  1150.1  349.21  1150.3  364.32 1150.03  400.87 1149.94
  413.11 1150.29   437.6 1151.11  468.21 1151.51  486.57  1156.6  492.69 1158.94
  498.81 1160.36  511.06  1161.7  529.42 1162.89  550.85 1165.87  556.97 1166.99
  566.15 1168.01  572.27 1168.54  599.82 1169.92  630.43 1170.34  648.79 1170.92
#Mann= 3 , 0 , 0
       0      .1       0     322      .1       0  413.11      .1       0
Bank Sta=322,413.11
XS Rating Curve= 0 ,0
Exp/Cntr=0.3,0.1

Type RM Length L Ch R = 1 ,27523.44,52.71,42.14,30.11
XS GIS Cut Line= 6
     645566.8162    4324760.8678     645319.4988    4324785.6502
     645216.8643    4324765.7224     645218.5485    4324756.6932
     645224.7055    4324738.9915     644904.0336    4324726.4718
#Sta/Elev= 30
       0 1170.29   39.89 1165.73   76.71 1162.78  122.74 1157.53  184.12 1154.09
  211.73 1152.97  278.43 1151.08  290.38 1150.26   308.3  1149.9   332.2 1150.21
   360.7 1149.85  368.09 1150.22  381.48 1149.93  445.66 1150.31  482.34 1149.56
  488.45 1150.34  497.62 1153.07  503.73 1155.44  509.85 1157.04  525.13  1159.1
  574.03 1162.54  586.25 1162.73  601.54 1163.97  619.87 1166.22  641.27 1167.02
  647.38 1166.91  662.66 1167.65  665.72 1168.22  674.89 1168.95   702.4 1169.98
#Mann= 3 , 0 , 0
       0      .1       0  290.38      .1       0  488.45      .1       0
Bank Sta=290.38,488.45
XS Rating Curve= 0 ,0
Exp/Cntr=0.3,0.1

Type RM Length L Ch R = 1 ,27481.3 ,22.02,20.66,17.08
XS GIS Cut Line= 6
     645543.9788    4324742.5558      645262.197    4324744.5401
     645244.2053    4324740.4391     645241.0303    4324738.4547
     645217.6146    4324730.9141     644901.6794    4324718.7432
#Sta/Elev= 30
       0 1170.41   49.01 1165.96   55.13 1165.02   76.57 1162.55  110.27 1159.05
  116.39  1158.1  131.71 1156.75  137.83 1155.88  153.15 1154.41  235.84 1151.17
  275.66 1150.96  287.06 1150.34  292.33 1149.64  294.97 1149.27  325.85 1149.85
  380.77 1150.19  420.67 1149.46  426.81 1149.72  432.95 1151.18  439.09    1153
  442.16  1154.2  451.37 1156.69  463.65 1158.03  497.41 1160.38  512.76 1162.42
  525.04 1162.52  561.88 1165.61  586.43 1166.57  614.06 1168.62  644.76 1170.12
#Mann= 3 , 0 , 0
       0      .1       0  292.33      .1       0  426.81      .1       0
Bank Sta=292.33,426.81
XS Rating Curve= 0 ,0
Exp/Cntr=0.3,0.1

Type RM Length L Ch R = 1 ,27460.64,26.85,28.64,32.46
XS GIS Cut Line= 4
     645499.5066    4324716.9352     645258.0739    4324719.9779
     645235.0551    4324722.7561     644897.3138    4324708.7464
#Sta/Elev= 30
       0 1169.74   39.73 1165.69   61.13 1163.04   67.24 1161.73   76.41  1160.5
  103.92 1158.07  106.97 1157.26  116.14 1155.94  137.54 1153.58  165.04 1152.31
  207.83 1149.57  226.17  1149.2  250.15 1148.26  258.84 1149.13  283.08 1149.68
  341.46    1150  381.41 1149.28  387.56 1150.22   393.7  1152.5  402.92 1154.65
  415.21 1156.86   439.8 1158.82  455.16    1161  467.46 1162.21  482.82  1162.4
  488.97 1163.05  525.84 1165.11  541.21 1167.02  575.01 1169.03  602.67 1170.05
#Mann= 3 , 0 , 0
       0      .1       0  226.17      .1       0  258.84      .1       0
Bank Sta=226.17,258.84
XS Rating Curve= 0 ,0
Exp/Cntr=0.3,0.1

Type RM Length L Ch R = 1 ,27432   ,59.9,62.87,70.42
XS GIS Cut Line= 5
     645468.9202    4324697.3676     645295.7051    4324707.6874
     645250.4192    4324692.6725     645237.2536    4324686.1315
     644893.4503    4324693.3989
#Sta/Elev= 30
       0 1170.07    27.4 1166.54   42.62 1163.73   70.02 1159.71   76.11 1158.47
   97.42 1155.54  121.77 1153.25  164.39 1150.18  185.45 1147.86  197.38 1147.45
  221.23 1146.51  224.17 1146.56  230.05 1147.63   260.5 1148.71  361.82  1148.6
  377.17 1151.31  383.31 1152.75   404.8 1156.07  420.15 1157.49  432.44 1155.96
  438.58 1156.33  441.65 1156.83     457  1161.1  466.21 1162.97  481.56 1164.05
  506.12 1166.42  530.69 1167.68  549.11 1169.13  558.32 1169.57  579.81  1169.8
#Mann= 3 , 0 , 0
       0      .1       0  197.38      .1       0  230.05      .1       0
Bank Sta=197.38,230.05
XS Rating Curve= 0 ,0
Exp/Cntr=0.3,0.1

Type RM Length L Ch R = 1 ,27369.13,33.85,28.57,25.52
XS GIS Cut Line= 6
     645431.7732      4324662.55      645283.077    4324648.2625
     645276.6212    4324641.7537     645275.3512     4324639.055
     645268.2074    4324634.7687     644904.4245    4324665.7449
#Sta/Elev= 30
       0 1170.85    9.15 1169.07   12.19 1168.12   30.49  1164.9   33.53 1163.91
   48.78 1161.78   57.92 1159.93   70.12 1158.17   73.17 1157.25   106.7 1152.95
  115.85    1151  128.04    1150  143.28 1147.03  155.49  1145.9  161.53  1146.1
  172.96 1147.26  185.24 1148.04   255.8  1147.5  360.12 1148.32  381.59 1150.53
  403.07 1154.39  406.14 1155.39  412.27 1156.41  415.34 1157.35  424.55 1161.46
  430.68 1162.24  464.43 1164.78  510.45  1168.9  528.86 1170.31     535 1170.47
#Mann= 3 , 0 , 0
       0      .1       0  143.28      .1       0  172.96      .1       0
Bank Sta=143.28,172.96
XS Rating Curve= 0 ,0
Exp/Cntr=0.3,0.1

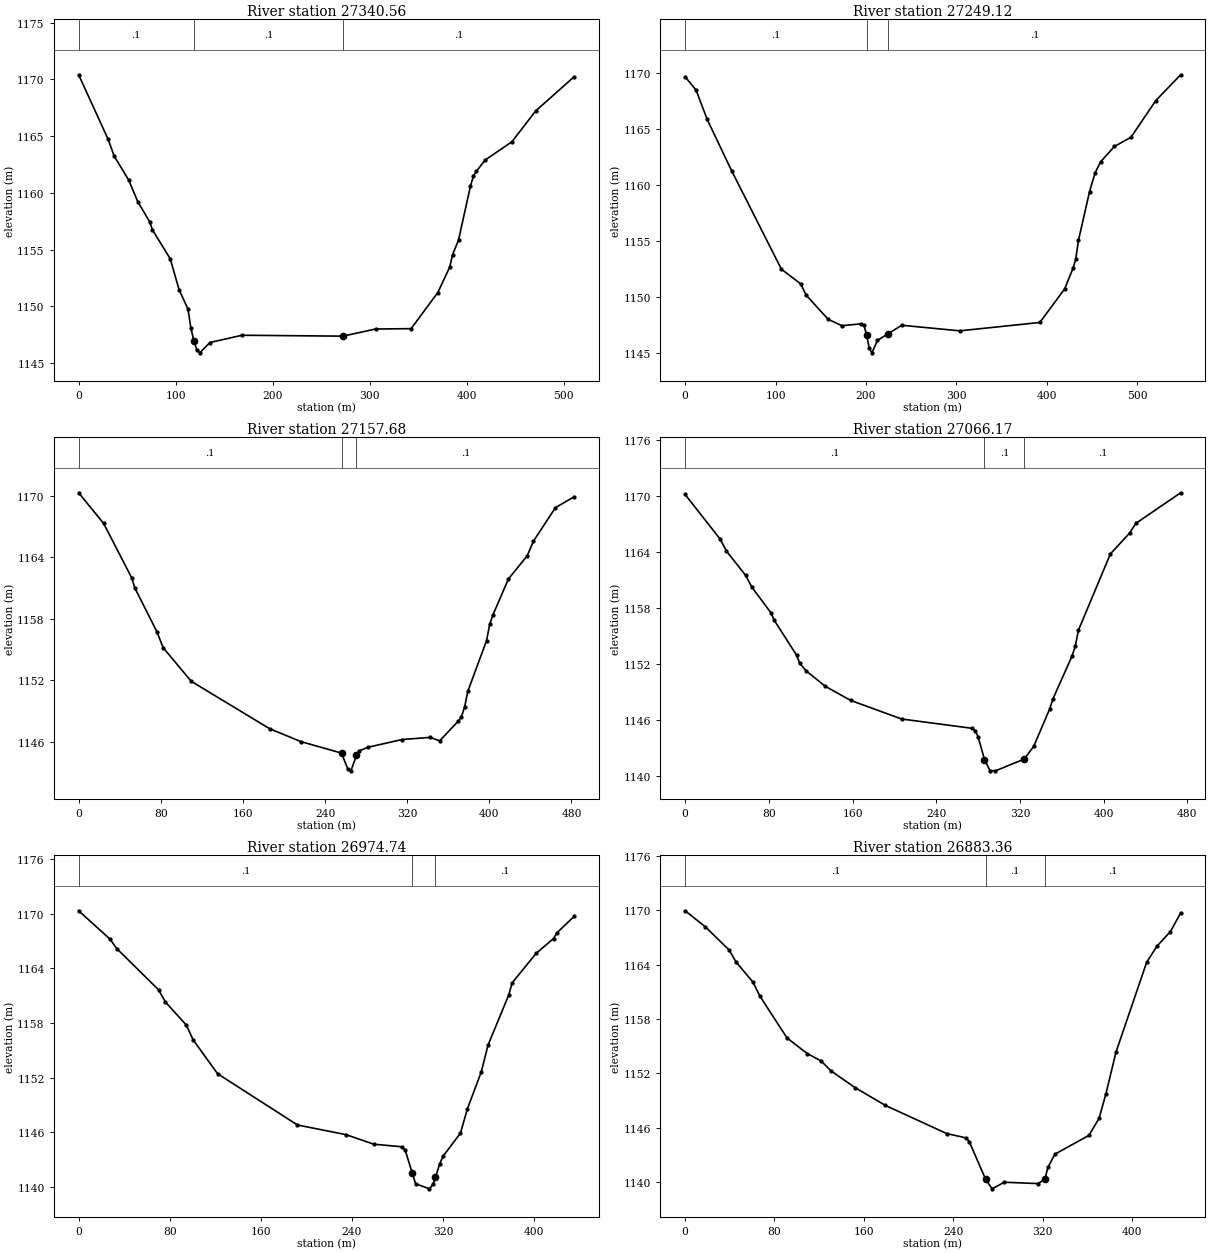
Type RM Length L Ch R = 1 ,27340.56,103.9,91.44,76.76
XS GIS Cut Line= 4
     645418.3185     4324637.726     645294.7223    4324620.1637
     645282.0508    4324616.8786     644911.6404    4324658.8927
#Sta/Elev= 30
       0 1170.41   30.45 1164.72   36.54 1163.26   51.76 1161.11    60.9 1159.23
   73.08 1157.48   76.12 1156.74   94.39  1154.2  103.52 1151.47  112.66 1149.78
   115.7 1148.09  118.75 1146.97  121.79 1146.18  124.84 1145.91  135.31 1146.82
  168.48 1147.46  272.38 1147.38  305.99 1148.01  342.65 1148.04  370.16 1151.22
  382.38 1153.45  385.43 1154.57  391.54 1155.86  403.77 1160.58  406.82 1161.48
  409.88 1161.91  419.05  1162.9  446.55 1164.51  470.99 1167.22  510.71 1170.24
#Mann= 3 , 0 , 0
       0      .1       0  118.75      .1       0  272.38      .1       0
Bank Sta=118.75,272.38
XS Rating Curve= 0 ,0
Exp/Cntr=0.3,0.1

Type RM Length L Ch R = 1 ,27249.12,86.13,91.45,99.44
XS GIS Cut Line= 4
     645385.2455    4324455.1631     645228.1034    4324559.5231
     645229.8596    4324610.4499     644923.5467    4324645.6635
#Sta/Elev= 30
       0  1169.7   12.17 1168.49   24.34 1165.89   51.72 1161.23  106.49 1152.46
  127.79 1151.15  133.87 1150.14  158.21 1147.97  173.43  1147.4  194.63 1147.57
  197.63 1147.47  200.63 1146.59  203.63 1145.37  206.62 1144.97  212.62 1146.08
  224.61 1146.69   239.6 1147.44   303.7 1146.94  392.23 1147.69  419.71  1150.7
  428.87 1152.54  431.92 1153.34  434.97 1155.05  447.19  1159.4  453.29 1161.08
   459.4 1162.07  474.66 1163.45  492.98 1164.27  520.45 1167.56  547.93 1169.87
#Mann= 3 , 0 , 0
       0      .1       0  200.63      .1       0  224.61      .1       0
Bank Sta=200.63,224.61
XS Rating Curve= 0 ,0
Exp/Cntr=0.3,0.1

Type RM Length L Ch R = 1 ,27157.68,89.83,91.5,91.92
XS GIS Cut Line= 5
      645377.308    4324396.9547     645150.7734     4324540.555
     645148.8787     4324541.995     645139.8118    4324547.9243
     644943.3905    4324591.4238
#Sta/Elev= 30
       0 1170.27   24.38 1167.28   51.81 1161.96   54.86 1160.97    76.2 1156.74
   82.29 1155.18  109.72  1151.9  185.92 1147.29   216.4 1146.03  256.02 1144.91
  262.12 1143.36  265.17 1143.18  270.59 1144.68   273.3 1145.12  281.43 1145.47
  314.96 1146.23  342.39 1146.44  351.54  1146.1  369.83 1148.03  372.87 1148.47
  375.92  1149.4  378.97 1150.91  397.26 1155.86  400.31 1157.44  403.36 1158.34
   418.6 1161.88  436.89 1164.13  442.98 1165.56  464.32 1168.82  482.61 1169.88
#Mann= 3 , 0 , 0
       0      .1       0  256.02      .1       0  270.59      .1       0
Bank Sta=256.02,270.59
XS Rating Curve= 0 ,0
Exp/Cntr=0.3,0.1

Type RM Length L Ch R = 1 ,27066.17,90.15,91.43,94.23
XS GIS Cut Line= 4
     645375.9851     4324342.715     645111.3286    4324459.1057
     645107.0892    4324460.1651      644951.328    4324550.4133
#Sta/Elev= 30
       0  1170.2   33.48 1165.42   39.56 1164.13   57.82 1161.54   63.91 1160.25
   82.17 1157.51   85.21 1156.72  106.52 1152.99  109.56 1152.11  115.65 1151.31
  133.91 1149.66  158.25 1148.14  206.95 1146.15   273.9 1145.16  276.95 1144.92
  279.99 1144.24  286.08 1141.81   291.3 1140.63  296.54  1140.6     324 1141.86
  333.15 1143.23  348.41 1147.24  351.46  1148.3  369.77  1152.9  372.82 1153.95
  375.87 1155.67  406.38 1163.83  424.69 1166.06  430.79 1167.11  473.51 1170.38
#Mann= 3 , 0 , 0
       0      .1       0  286.08      .1       0     324      .1       0
Bank Sta=286.08,324
XS Rating Curve= 0 ,0
Exp/Cntr=0.3,0.1

Type RM Length L Ch R = 1 ,26974.74,87.99,91.38,90.11
XS GIS Cut Line= 3
     645379.9539    4324289.7982     645080.4437    4324374.4305
     644956.6197    4324382.4026
#Sta/Elev= 30
       0 1170.32   27.46 1167.22   33.56 1166.16   70.18 1161.65   76.28  1160.3
   94.59 1157.77  100.69 1156.13  122.05 1152.43  192.24  1146.8  234.95 1145.74
  259.36 1144.69  283.78 1144.41  286.83 1144.06  292.93 1141.58  295.98 1140.35
  308.19 1139.79  311.24 1140.28  313.45 1141.05  317.29 1142.57  320.32  1143.4
  335.45 1145.91   341.5 1148.57  353.61 1152.59  359.66 1155.57  377.82 1161.07
  380.84 1162.41  402.03 1165.66  417.16 1167.27  420.19  1167.9  435.32 1169.71
#Mann= 3 , 0 , 0
       0      .1       0  292.93      .1       0  313.45      .1       0
Bank Sta=292.93,313.45
XS Rating Curve= 0 ,0
Exp/Cntr=0.3,0.1

Type RM Length L Ch R = 1 ,26883.36,103,91.44,79.5
XS GIS Cut Line= 6
     645358.7872    4324243.4961     645125.4307    4324285.3956
     645079.0921    4324283.5422     645074.8626    4324285.1643
     645059.2522    4324286.0904     644948.6822    4324371.8192
#Sta/Elev= 30
       0 1169.94   18.24 1168.16   39.51 1165.59   45.59 1164.29   60.79 1162.05
   66.87 1160.53   91.19  1155.9  109.43 1154.16  121.58 1153.37   130.7 1152.25
  151.98 1150.42  179.34 1148.44  234.05 1145.34  251.58 1144.85  254.48 1144.41
  268.97 1140.29  274.77 1139.23  285.73 1139.96   315.8 1139.81  321.88 1140.28
  324.92 1141.64  331.01 1143.06  361.42 1145.13  370.55 1147.02  376.63 1149.71
  385.75 1154.36  413.13 1164.25  422.25 1166.02  434.42 1167.65  443.54  1169.7
#Mann= 3 , 0 , 0
       0      .1       0  268.97      .1       0  321.88      .1       0
Bank Sta=268.97,321.88
XS Rating Curve= 0 ,0
Exp/Cntr=0.3,0.1

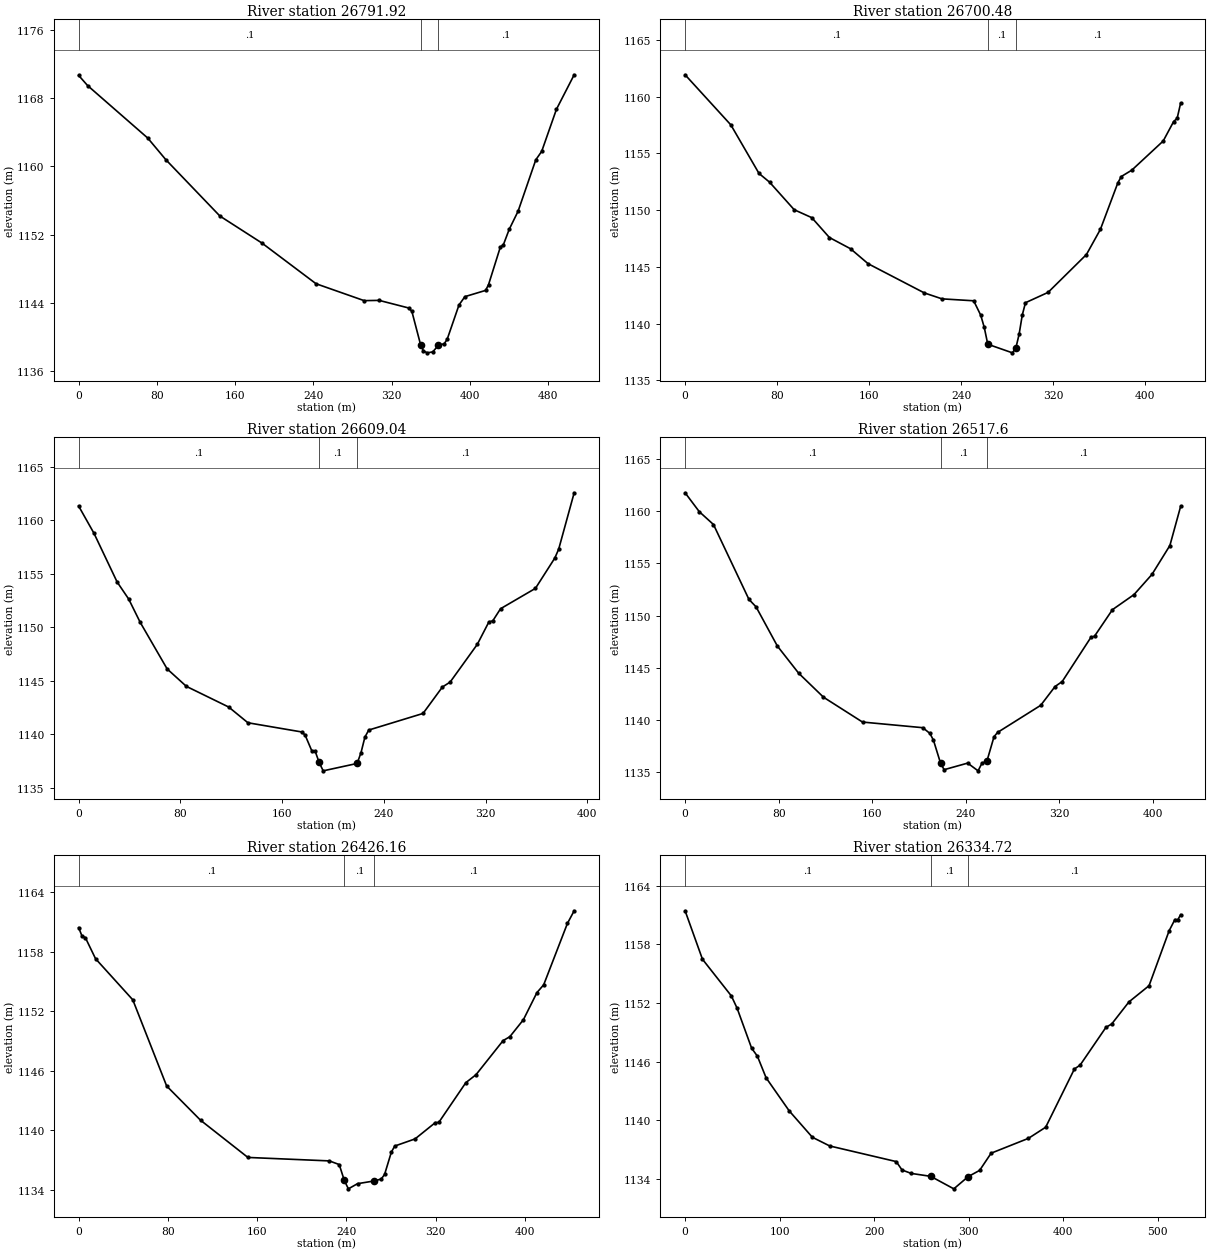
Type RM Length L Ch R = 1 ,26791.92,77.13,91.44,93.86
XS GIS Cut Line= 6
     645288.6724    4324018.5998     645019.4037    4324212.2891
     645008.2911    4324229.7516       645007.83     4324233.693
     645004.5996    4324241.2664     644938.0988    4324366.5276
#Sta/Elev= 30
       0 1170.68    9.21 1169.48   70.64 1163.33   89.07  1160.8  144.35 1154.19
  187.35 1151.02  242.63 1146.25  291.77 1144.27  307.12  1144.3  337.61  1143.4
  340.57    1143  349.44 1139.11  352.39 1138.37  356.36 1138.15  361.85 1138.26
  367.61 1139.02  373.65 1139.22  376.66 1139.75  388.73 1143.77  394.77 1144.74
  415.89 1145.47  418.91 1146.15  430.98 1150.56     434  1150.8  440.03 1152.63
  449.08 1154.75  467.19 1160.78  473.22 1161.77  488.31 1166.71  506.41 1170.75
#Mann= 3 , 0 , 0
       0      .1       0  349.44      .1       0  367.61      .1       0
Bank Sta=349.44,367.61
XS Rating Curve= 0 ,0
Exp/Cntr=0.3,0.1

Type RM Length L Ch R = 1 ,26700.48,94.53,91.44,80.46
XS GIS Cut Line= 4
      645181.516     4324031.829      644938.485    4324185.6289
     644916.3628    4324197.0998     644852.1091    4324296.4128
#Sta/Elev= 30
       0 1161.94   39.78 1157.52   64.25 1153.24   73.43 1152.47   94.85 1150.04
  110.15 1149.34  125.45 1147.59   143.8  1146.6   159.1 1145.28  208.06  1142.7
  223.36 1142.18  250.89 1142.01  257.01 1140.74  260.07 1139.67  263.13 1138.18
  284.55 1137.42  287.61 1137.87  290.38 1139.06  293.15 1140.76  295.91 1141.84
  315.56 1142.75  348.92 1146.09  361.06 1148.31  376.22 1152.41  379.25 1152.97
  388.35 1153.53  415.65  1156.1  424.75 1157.82  427.78  1158.1  430.81 1159.44
#Mann= 3 , 0 , 0
       0      .1       0  263.13      .1       0  287.61      .1       0
Bank Sta=263.13,287.61
XS Rating Curve= 0 ,0
Exp/Cntr=0.3,0.1

Type RM Length L Ch R = 1 ,26609.04,92.05,91.44,88.96
XS GIS Cut Line= 6
     644988.4579     4323943.017     644901.2344    4324095.3176
     644898.3495    4324115.5696     644895.1745    4324120.3321
     644894.3278    4324125.3063     644823.3576    4324293.8552
#Sta/Elev= 30
       0 1161.31    12.1 1158.76   30.26 1154.22   39.34 1152.63   48.42 1150.45
    69.6  1146.1   84.73 1144.47  118.01 1142.54  133.14 1141.07  175.51 1140.21
  178.12 1139.92  183.34 1138.46  185.95 1138.44  189.17 1137.36  192.34 1136.58
  219.04 1137.27  222.09 1138.28  225.14 1139.73  228.18 1140.39  270.86 1141.94
   286.1 1144.41  292.19 1144.87  313.53 1148.39  322.67 1150.49  325.72 1150.59
  331.82 1151.72  359.25 1153.62  374.49 1156.45  377.54 1157.28  389.73 1162.55
#Mann= 3 , 0 , 0
       0      .1       0  189.17      .1       0  219.04      .1       0
Bank Sta=189.17,219.04
XS Rating Curve= 0 ,0
Exp/Cntr=0.3,0.1

Type RM Length L Ch R = 1 ,26517.6 ,76.92,91.44,81.25
XS GIS Cut Line= 6
     644940.8328    4323906.5044     644808.1837    4324095.1702
     644809.6816    4324115.0526     644809.4336    4324118.4521
     644807.1254    4324121.8402       644783.67    4324285.9177
#Sta/Elev= 30
       0 1161.75   12.14 1159.94   24.28 1158.71   54.62 1151.54   60.69 1150.83
    78.9 1147.08   97.11 1144.48  118.35 1142.18  151.73  1139.8  203.32 1139.26
  209.39 1138.71  212.42 1138.06  218.49 1135.86  221.53 1135.24  241.67 1135.87
  250.57 1135.13  253.98 1135.88  258.08 1136.04  264.22  1138.4  267.29 1138.81
  304.12  1141.4   316.4  1143.2  322.53 1143.68  347.09 1147.91  350.16 1148.02
  365.51 1150.56  383.92    1152  399.27 1153.93  414.62  1156.7  423.82 1160.45
#Mann= 3 , 0 , 0
       0      .1       0  218.49      .1       0  258.08      .1       0
Bank Sta=218.49,258.08
XS Rating Curve= 0 ,0
Exp/Cntr=0.3,0.1

Type RM Length L Ch R = 1 ,26426.16,57.82,91.44,101.12
XS GIS Cut Line= 5
     644851.9327    4323869.9918     644747.2589    4324033.5768
     644740.9296    4324069.6713     644741.8998    4324088.7527
     644732.8699    4324282.7427
#Sta/Elev= 30
       0 1160.44    3.03 1159.59    6.07 1159.42   15.17  1157.3   48.55 1153.15
    78.9 1144.45  109.24    1141  151.72 1137.24  224.75 1136.89  233.58 1136.52
  238.12 1134.92  241.77 1134.07  249.96 1134.59  265.13 1134.87   271.2 1135.06
  274.23 1135.52   280.3 1137.78  283.34 1138.39  301.54 1139.11  319.75 1140.76
  322.78 1140.77  347.06 1144.79  356.16 1145.59  380.44 1149.03  386.51 1149.43
  398.64 1151.14  410.78 1153.88  416.85 1154.67  438.09 1160.86  444.16 1162.14
#Mann= 3 , 0 , 0
       0      .1       0  238.12      .1       0  265.13      .1       0
Bank Sta=238.12,265.13
XS Rating Curve= 0 ,0
Exp/Cntr=0.3,0.1

Type RM Length L Ch R = 1 ,26334.72,98.18,91.44,46.53
XS GIS Cut Line= 6
     644828.1201    4323854.1168     644695.8635    4324045.5272
     644689.9368    4324042.5639     644660.9384    4324057.1689
      644644.005    4324075.1606     644553.4821    4324284.3302
#Sta/Elev= 30
       0 1161.45   18.37 1156.49   48.98 1152.73    55.1 1151.46   70.41 1147.38
   76.53 1146.56   85.72 1144.35  110.21 1140.96   134.7 1138.26  153.06 1137.37
  223.47 1135.77   229.6 1134.91  239.28 1134.56  259.95 1134.26   284.4 1132.98
  299.57 1134.23  311.72 1134.87  323.88 1136.63  363.38 1138.15  381.62 1139.29
  412.01 1145.25  418.08 1145.65  445.43 1149.52  451.51 1149.86  469.74 1152.12
  491.02 1153.78  512.29 1159.41  518.37 1160.55  521.41 1160.53  524.45 1161.05
#Mann= 3 , 0 , 0
       0      .1       0  259.95      .1       0  299.57      .1       0
Bank Sta=259.95,299.57
XS Rating Curve= 0 ,0
Exp/Cntr=0.3,0.1

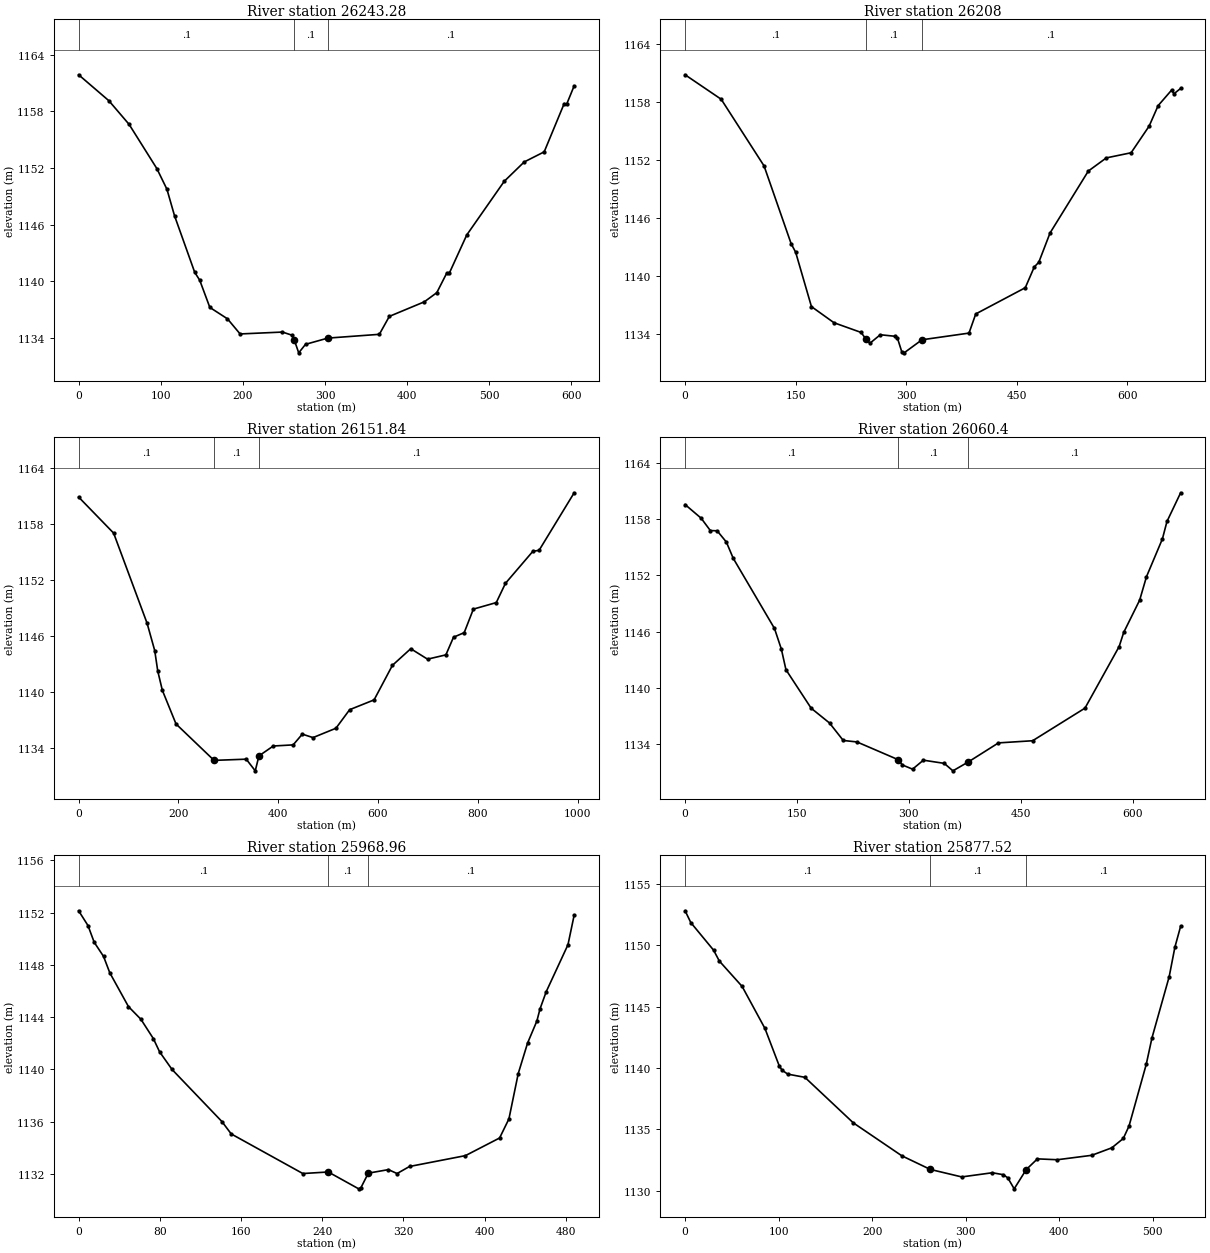
Type RM Length L Ch R = 1 ,26243.28,33.07,35.29,28.53
XS GIS Cut Line= 6
     644778.9075    4323777.3875     644651.8976    4323965.9973
     644644.2161    4324013.6323     644631.1965    4324040.8004
      644620.084    4324040.8004     644495.2736    4324298.0885
#Sta/Elev= 30
       0 1161.87   36.87 1159.12   61.46 1156.62   95.26 1151.94  107.55 1149.75
  116.77 1146.95  141.35 1140.96  147.49 1140.12  159.79 1137.24   181.3 1136.03
  196.66 1134.43  248.28 1134.63  259.77  1134.3  262.53 1133.82  268.05 1132.43
  276.33 1133.33  303.45 1133.99  366.25 1134.39  378.42 1136.29  421.01 1137.83
  436.22  1138.8  448.38 1140.88  451.43 1140.86  472.72 1144.91  518.35 1150.59
  542.69 1152.64  567.03 1153.71  591.37 1158.82  594.41 1158.76  603.54  1160.7
#Mann= 3 , 0 , 0
       0      .1       0  262.53      .1       0  303.45      .1       0
Bank Sta=262.53,303.45
XS Rating Curve= 0 ,0
Exp/Cntr=0.3,0.1

Type RM Length L Ch R = 1 ,26208   ,50.66,56.15,90.46
XS GIS Cut Line= 5
     644767.0944    4323751.2328     644622.1025    4323952.3165
     644612.5774    4323978.7749     644600.2743    4324053.2553
     644447.1596    4324335.0635
#Sta/Elev= 30
       0 1160.81   48.97 1158.28  107.12 1151.39  143.85 1143.35  149.97 1142.47
  171.39 1136.85     202 1135.18  238.72 1134.18  244.85 1133.54  250.72 1133.06
  264.78 1133.94  285.09 1133.78  288.11 1133.58  294.14 1132.13  297.16 1132.07
  321.32 1133.42  385.12 1134.11  394.28 1136.09  461.48  1138.8  473.69 1140.95
   479.8 1141.43  495.08 1144.46     547 1150.86  571.44 1152.22  605.04 1152.75
  629.47  1155.5  641.69 1157.62  660.02 1159.23  663.07 1158.84  672.23  1159.4
#Mann= 3 , 0 , 0
       0      .1       0  244.85      .1       0  321.32      .1       0
Bank Sta=244.85,321.32
XS Rating Curve= 0 ,0
Exp/Cntr=0.3,0.1

Type RM Length L Ch R = 1 ,26151.84,75.59,91.44,81.21
XS GIS Cut Line= 6
      644761.445     4323709.654     644576.1472    4323932.4692
      644553.508     4323992.568      644541.953    4324019.9704
     644518.1405     4324033.861     644185.1813     4324510.814
#Sta/Elev= 30
       0 1160.87   70.16 1157.01  137.27 1147.35  152.52 1144.43  158.63 1142.23
  167.78 1140.18  195.23 1136.57  271.49 1132.67  335.94  1132.8  354.05 1131.55
  361.41 1133.15  390.19 1134.21     430 1134.33  448.37 1135.48   469.8 1135.11
  515.72 1136.11  543.27  1138.1  592.26 1139.15     629 1142.85  665.73 1144.63
  699.41 1143.51  736.15 1143.97  751.45 1145.86  772.88 1146.35  791.25 1148.87
  837.17 1149.57  855.54 1151.63  910.65 1155.07   922.9 1155.16  993.31 1161.33
#Mann= 3 , 0 , 0
       0      .1       0  271.49      .1       0  361.41      .1       0
Bank Sta=271.49,361.41
XS Rating Curve= 0 ,0
Exp/Cntr=0.3,0.1

Type RM Length L Ch R = 1 ,26060.4 ,45.36,91.44,81.38
XS GIS Cut Line= 6
     644740.4594    4323690.0024     644538.1122    4323891.9206
     644520.6496    4323899.8581     644498.2159    4323922.5787
     644497.7025    4323953.8877      644256.619    4324121.8757
#Sta/Elev= 30
       0 1159.59   21.52 1158.13   33.81 1156.81   43.03 1156.78   55.33 1155.58
   64.55 1153.84  119.88 1146.33   129.1 1144.12  135.25 1141.92  169.06  1137.8
  193.65 1136.22  212.09 1134.35  230.53 1134.19  285.86 1132.29  291.34 1131.73
  305.04 1131.28  319.55 1132.24   347.5  1131.9  359.15  1131.1  379.96 1132.06
  420.24 1134.09  466.05 1134.32  536.28 1137.81  582.09  1144.4  588.19 1145.91
  609.57 1149.36  618.73 1151.87  640.11 1155.92  646.21 1157.78  664.54 1160.85
#Mann= 3 , 0 , 0
       0      .1       0  285.86      .1       0  379.96      .1       0
Bank Sta=285.86,379.96
XS Rating Curve= 0 ,0
Exp/Cntr=0.3,0.1

Type RM Length L Ch R = 1 ,25968.96,81.47,91.44,17.98
XS GIS Cut Line= 6
     644667.7088    4323692.1221     644495.2231     4323867.376
     644477.3637    4323884.0448     644477.2551    4323887.5426
      644443.497    4323908.6511     644306.3607    4324016.5713
#Sta/Elev= 30
       0 1152.14    9.21 1151.01   15.34 1149.73   24.55 1148.65   30.68  1147.4
    49.1 1144.81   61.37 1143.84   73.64 1142.36   79.78 1141.35   92.05    1140
  141.15 1136.02  150.36 1135.07  220.93 1132.04  245.99 1132.16  275.98 1130.87
  278.05 1130.94  285.44 1132.07  305.28 1132.34  313.78 1132.04  326.03 1132.58
  381.14 1133.41  414.81 1134.76     424 1136.22  433.18 1139.69  442.37 1142.02
  451.55 1143.71  454.61 1144.63  460.74 1145.95  482.17 1149.54  488.29 1151.81
#Mann= 3 , 0 , 0
       0      .1       0  245.99      .1       0  285.44      .1       0
Bank Sta=245.99,285.44
XS Rating Curve= 0 ,0
Exp/Cntr=0.3,0.1

Type RM Length L Ch R = 1 ,25877.52,25.26,91.44,73.75
XS GIS Cut Line= 6
      644648.466    4323620.5477      644434.457    4323829.2671
      644420.487    4323867.3672     644429.6945     4323886.576
     644431.7583    4323907.3723     644307.4974    4323986.3778
#Sta/Elev= 30
       0  1152.8     6.1 1151.84    30.5 1149.59    36.6 1148.71   61.01 1146.64
   85.41 1143.22  100.66 1140.18  103.71 1139.82  109.81  1139.5  128.12 1139.24
  179.97 1135.53  231.83 1132.85  262.33 1131.74  295.89 1131.13  328.64 1131.47
   340.5 1131.31  345.23 1131.05  352.02 1130.16  364.92 1131.73  376.86  1132.6
  398.17 1132.53  434.98 1132.89  456.46  1133.5  468.73 1134.26  474.86 1135.27
  493.27 1140.29  499.41 1142.45  517.81 1147.43  523.95 1149.84  530.08 1151.54
#Mann= 3 , 0 , 0
       0      .1       0  262.33      .1       0  364.92      .1       0
Bank Sta=262.33,364.92
XS Rating Curve= 0 ,0
Exp/Cntr=0.3,0.1