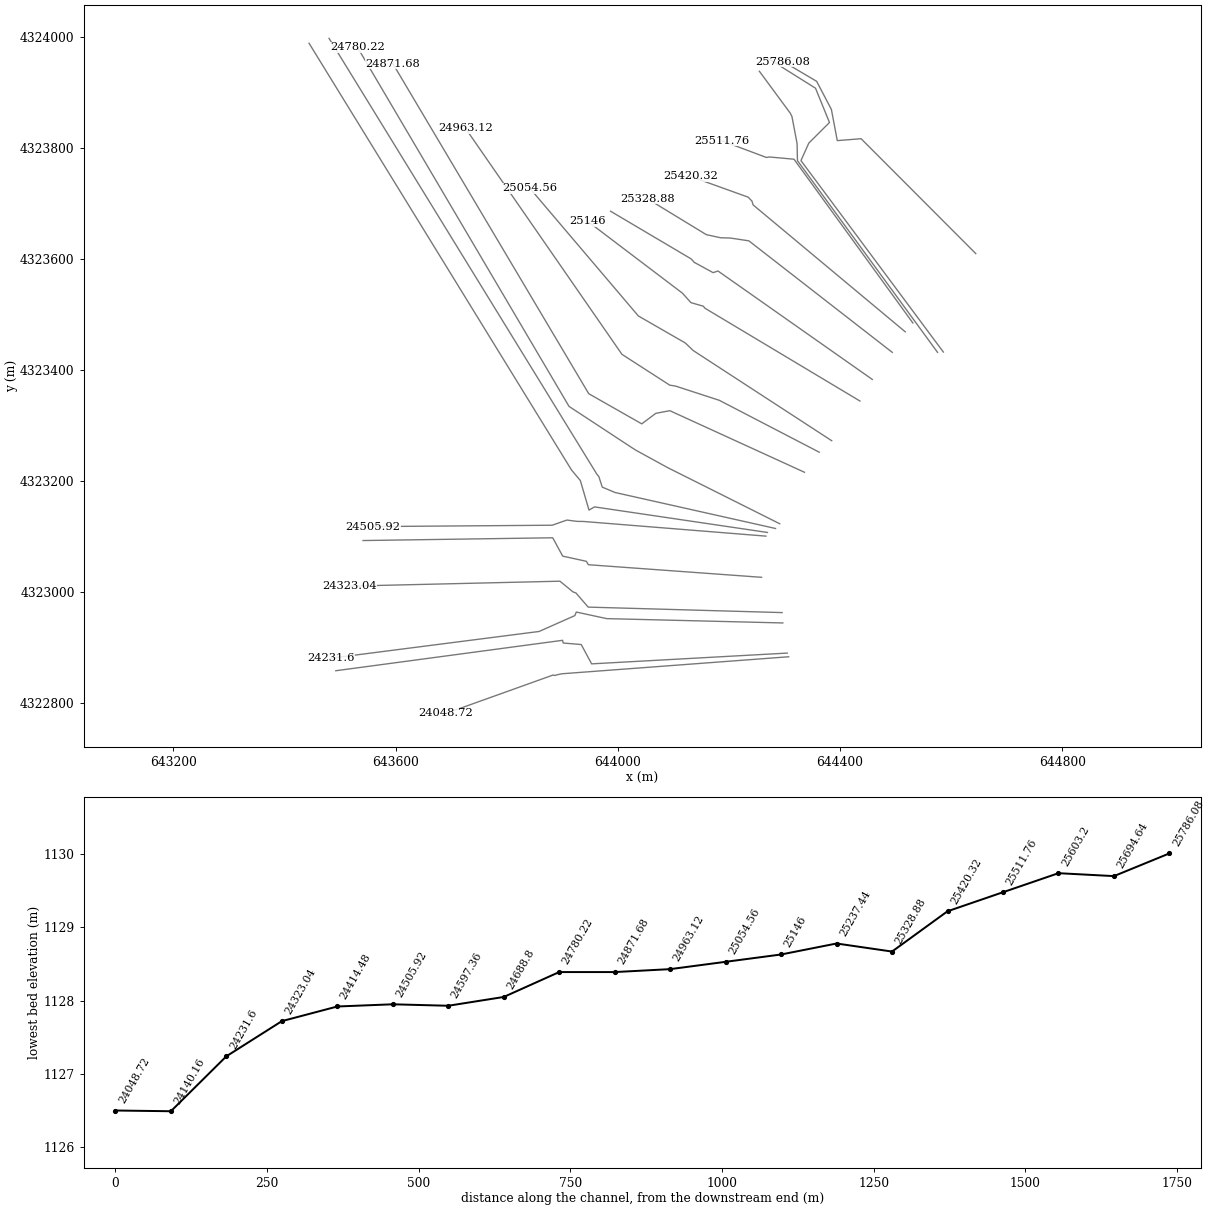
HEC-RAS study RedCreek.prj: RedCreek

--- RedCreek.g01 (geometry) --- (continued)

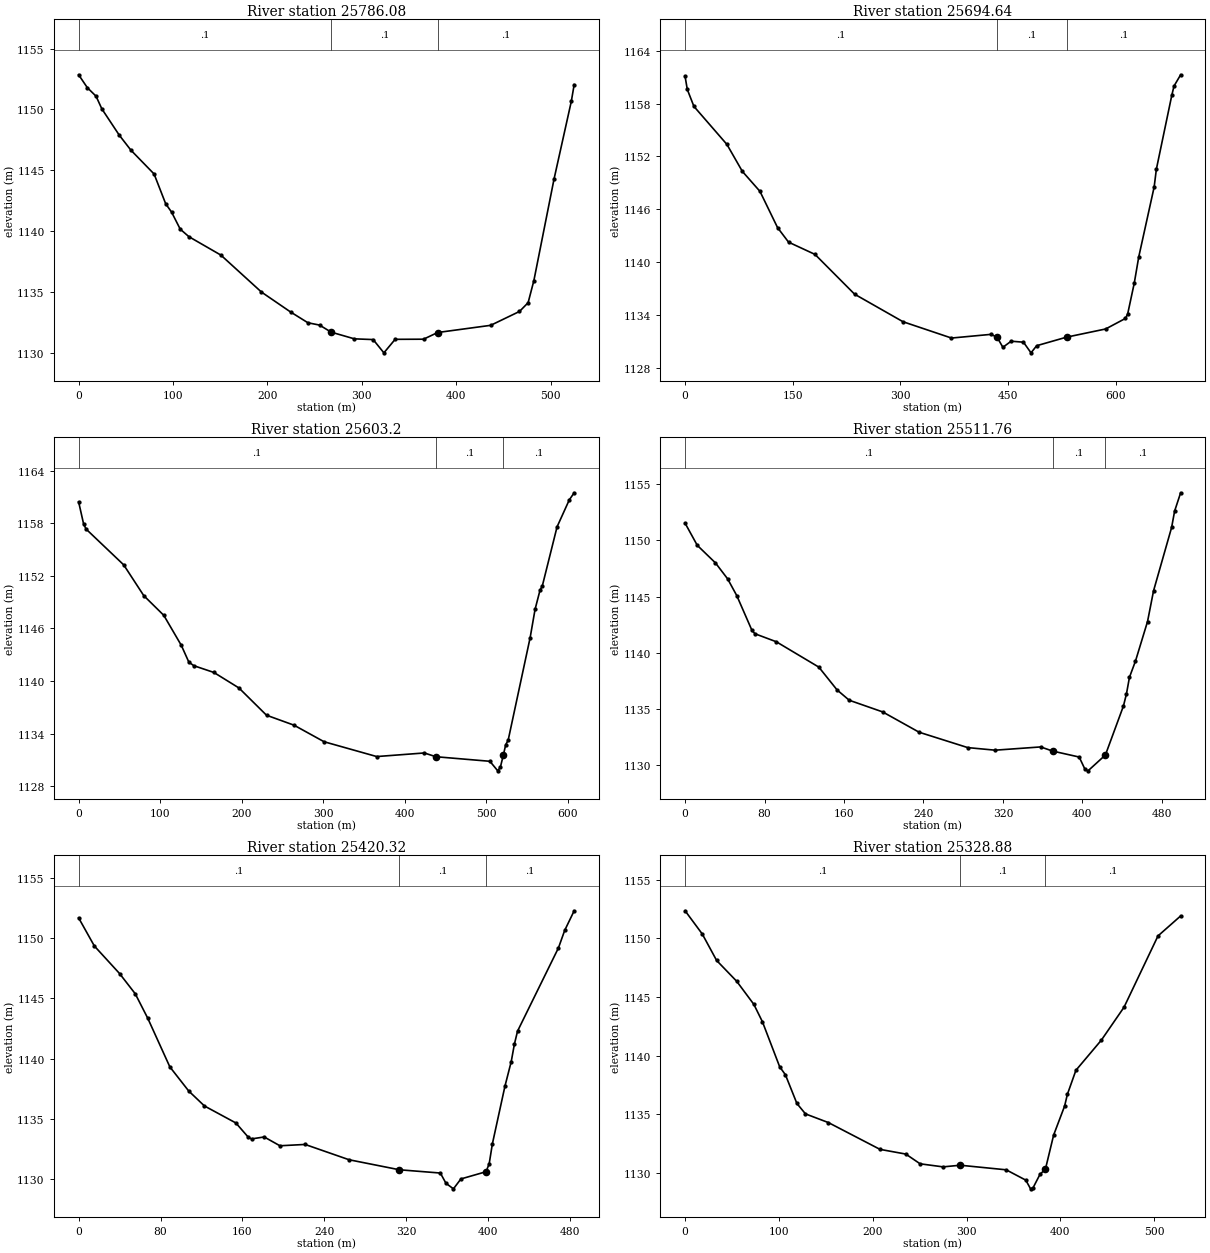
Type RM Length L Ch R = 1 ,25786.08,148.16,91.44,43.76
XS GIS Cut Line= 6
     644644.1052    4323609.5204     644437.7787     4323816.215
     644394.9161    4323812.7754     644384.3327    4323868.8672
     644357.8082    4323919.4468     644297.4725    4323955.1292
#Sta/Elev= 30
       0 1152.85    9.22 1151.79   18.45 1151.09   24.59 1150.05   43.04 1147.89
   55.34 1146.66   79.93  1144.7   92.23 1142.25   98.37 1141.58   107.6 1140.17
  116.82 1139.55  150.64 1138.04  193.68    1135  224.42 1133.37  242.86 1132.48
  255.16 1132.29  267.46 1131.71  292.05 1131.16  311.95  1131.1  323.32 1130.01
  335.24 1131.12  365.28 1131.13   380.3 1131.68  436.43 1132.27  466.96 1133.41
   476.1 1134.13   482.2 1135.95  503.53 1144.28  521.82 1150.66  524.87 1152.04
#Mann= 3 , 0 , 0
       0      .1       0  267.46      .1       0   380.3      .1       0
Bank Sta=267.46,380.3
XS Rating Curve= 0 ,0
Exp/Cntr=0.3,0.1

Type RM Length L Ch R = 1 ,25694.64,28.06,91.44,91.33
XS GIS Cut Line= 6
     644585.7613    4323432.3701     644329.5478    4323776.8519
     644343.7012    4323808.3167      644380.892    4323845.3777
     644355.7577    4323907.0996     644269.8482    4323961.0087
#Sta/Elev= 30
       0 1161.09    3.07 1159.61   12.27 1157.69   58.26 1153.37   79.73 1150.31
  104.26 1148.04   128.8 1143.92  144.13 1142.27  180.93 1140.88  236.12 1136.36
  303.59 1133.23  371.05 1131.38  426.25  1131.8  434.64 1131.46  442.62 1130.33
  454.16 1131.02  471.28 1130.91  481.81  1129.7  489.69 1130.51  531.25 1131.48
  585.77 1132.41  613.39 1133.61  616.46 1134.12  625.68 1137.64  631.83 1140.58
  653.34 1148.54  656.42 1150.56  677.93 1158.96     681    1160  690.22 1161.28
#Mann= 3 , 0 , 0
       0      .1       0  434.64      .1       0  531.25      .1       0
Bank Sta=434.64,531.25
XS Rating Curve= 0 ,0
Exp/Cntr=0.3,0.1

Type RM Length L Ch R = 1 ,25603.2 ,33.15,91.44,96.66
XS GIS Cut Line= 6
     644575.3896    4323431.7351     644323.2602    4323776.7237
     644322.5987    4323807.4815     644313.3515     4323856.165
     644310.3055    4323862.1752      644254.714    4323937.6195
#Sta/Elev= 30
       0 1160.44    6.15  1157.9    9.22 1157.33   55.33 1153.25   79.93 1149.74
  104.52 1147.49  126.04 1144.06  135.26 1142.15  141.41 1141.74     166 1140.97
  196.74  1139.2  230.56 1136.09  264.37 1134.95  301.26 1133.06  365.82 1131.37
  424.23 1131.78  438.49 1131.35  504.71 1130.83  514.36 1129.74  517.66 1130.19
  521.14 1131.51  524.14 1132.72  527.14 1133.24  554.14 1144.96  560.14 1148.17
  566.14 1150.33  569.14 1150.88  587.14 1157.59  602.14 1160.67  608.14 1161.48
#Mann= 3 , 0 , 0
       0      .1       0  438.49      .1       0  521.14      .1       0
Bank Sta=438.49,521.14
XS Rating Curve= 0 ,0
Exp/Cntr=0.3,0.1

Type RM Length L Ch R = 1 ,25511.76,115.5,91.44,80.73
XS GIS Cut Line= 5
     644530.9395    4323484.6519     644317.0389    4323779.3306
     644272.7241    4323783.3591      644267.347    4323782.4717
     644187.9201    4323812.2732
#Sta/Elev= 30
       0 1151.54   12.24 1149.57    30.6    1148   42.84 1146.58   52.02 1145.09
   67.32 1141.99   70.38 1141.69    91.8 1140.98  134.64 1138.72  152.99 1136.69
  165.23 1135.77  198.89 1134.73  235.61 1132.92  284.57 1131.55  312.11 1131.32
  358.01 1131.61  370.06 1131.24  396.76 1130.71  402.69  1129.6  405.66 1129.48
  423.16 1130.89  441.34 1135.26  444.37 1136.34   447.4 1137.82  453.46 1139.26
  465.58 1142.78  471.64 1145.52  489.82 1151.16  492.85 1152.62  498.91 1154.25
#Mann= 3 , 0 , 0
       0      .1       0  370.06      .1       0  423.16      .1       0
Bank Sta=370.06,423.16
XS Rating Curve= 0 ,0
Exp/Cntr=0.3,0.1

Type RM Length L Ch R = 1 ,25420.32,64.29,91.44,92.47
XS GIS Cut Line= 5
     644517.1812    4323468.7769     644243.5322    4323697.0398
     644241.3665    4323703.9859     644234.6269    4323710.9951
     644130.5318    4323748.4688
#Sta/Elev= 30
       0 1151.68   15.36 1149.35   39.94 1147.07    55.3 1145.39   67.58 1143.35
   89.09 1139.33  107.52 1137.33  122.88 1136.09   153.6 1134.68  165.89 1133.48
  168.96 1133.36  181.25 1133.52  196.61 1132.79  221.18  1132.9  264.19 1131.63
  313.35  1130.8  353.28 1130.53  358.78 1129.68  366.06 1129.22  373.35 1130.04
  397.94 1130.64  401.01 1131.31  404.08 1132.94  416.38 1137.73  422.52 1139.77
   425.6 1141.21  428.67 1142.29  468.62 1149.19  474.77 1150.65  483.99 1152.27
#Mann= 3 , 0 , 0
       0      .1       0  313.35      .1       0  397.94      .1       0
Bank Sta=313.35,397.94
XS Rating Curve= 0 ,0
Exp/Cntr=0.3,0.1

Type RM Length L Ch R = 1 ,25328.88,87.15,91.44,75.52
XS GIS Cut Line= 6
     644493.8978    4323431.7351     644235.8461    4323632.4196
     644202.5085    4323637.4996     644184.9069    4323637.9824
     644159.2719    4323643.5821     644053.6302    4323707.9607
#Sta/Elev= 30
       0 1152.34   18.33 1150.36   33.61 1148.11   54.99 1146.34   73.32 1144.37
   82.49 1142.88  100.82 1139.06  106.93 1138.38  119.15 1135.94  128.32 1135.05
  152.76 1134.31  207.75 1132.03  235.25 1131.63  250.52  1130.8  274.96 1130.54
   293.3 1130.68  342.23 1130.29  363.17 1129.41  368.25 1128.67  370.79 1128.74
  378.27  1129.9   384.1 1130.35  392.85 1133.25  404.51 1135.71  407.52 1136.72
  416.58 1138.76  443.73 1141.33  467.87 1144.13  504.08  1150.2  528.22  1151.9
#Mann= 3 , 0 , 0
       0      .1       0   293.3      .1       0   384.1      .1       0
Bank Sta=293.3,384.1
XS Rating Curve= 0 ,0
Exp/Cntr=0.3,0.1

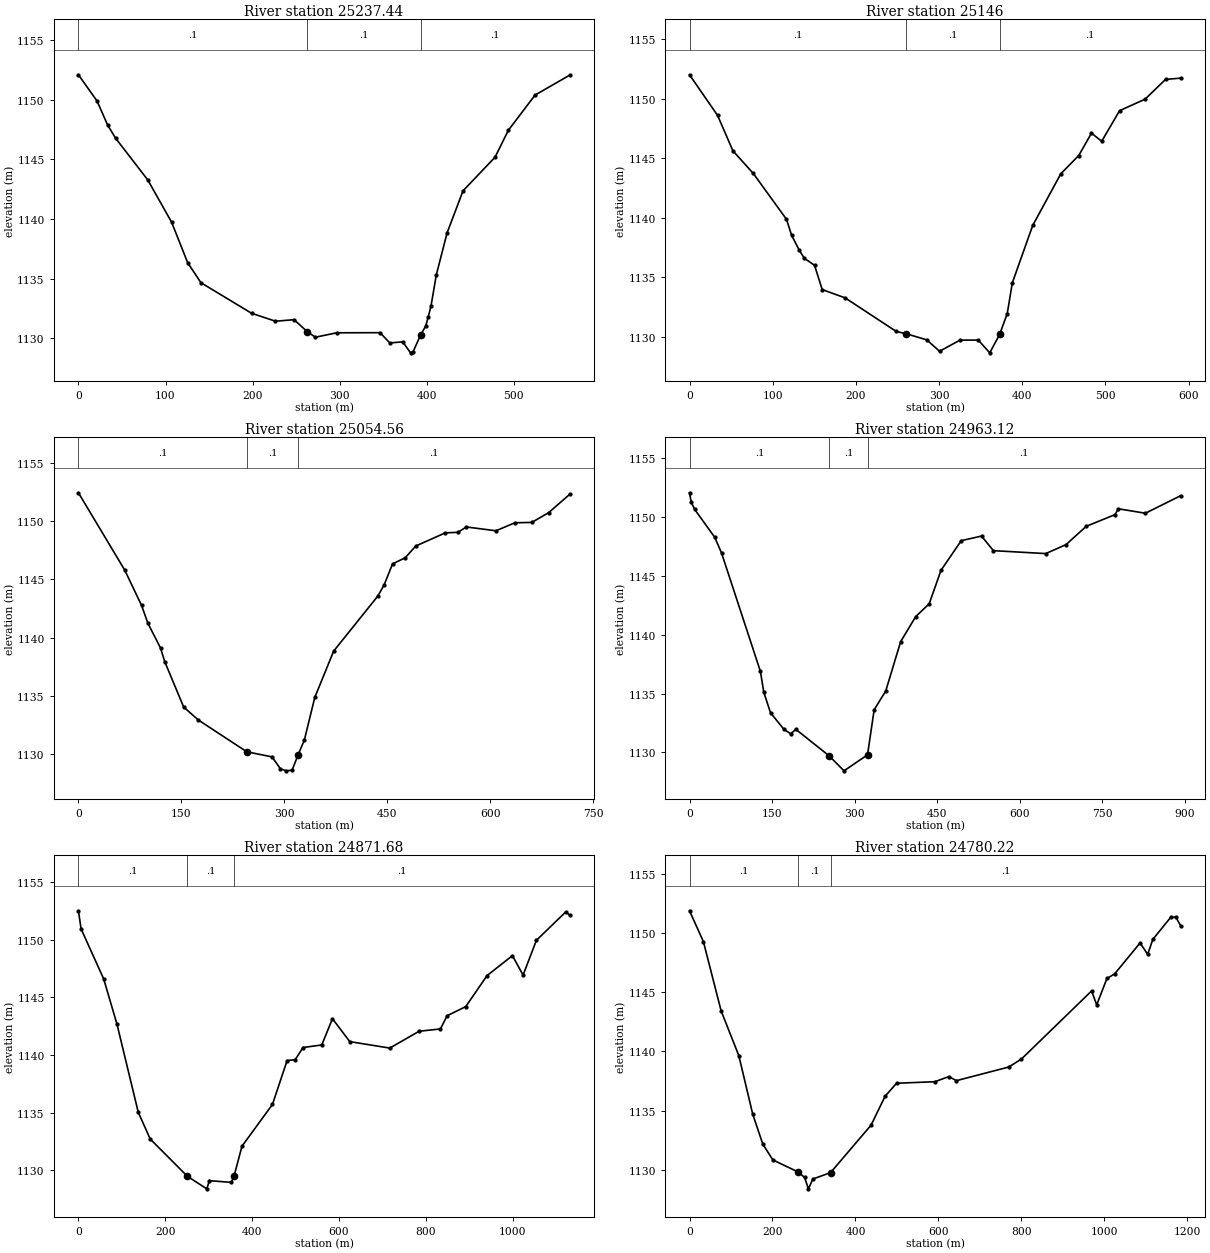
Type RM Length L Ch R = 1 ,25237.44,73.85,91.44,88.18
XS GIS Cut Line= 6
     644457.9144    4323383.0517     644180.2341    4323578.1887
       644171.51    4323575.1856     644137.5805    4323593.7336
      644131.974    4323599.9375     643986.9551    4323685.7356
#Sta/Elev= 30
       0 1152.09    21.4 1149.89   33.63 1147.86   42.81 1146.76    79.5 1143.29
  107.01 1139.73  125.36 1136.35  140.65 1134.66  198.74  1132.1  226.26 1131.43
  247.66 1131.56  262.95 1130.54  272.12 1130.09  296.58 1130.46  346.31 1130.47
  357.54 1129.61  372.41  1129.7  381.33 1128.78  384.31 1128.88  392.86 1130.27
  398.71 1131.02  401.77 1131.82  404.84 1132.71  410.96 1135.32  423.22 1138.82
   441.6 1142.36  478.36 1145.18  493.68 1147.44  524.32 1150.39  564.14 1152.06
#Mann= 3 , 0 , 0
       0      .1       0  262.95      .1       0  392.86      .1       0
Bank Sta=262.95,392.86
XS Rating Curve= 0 ,0
Exp/Cntr=0.3,0.1

Type RM Length L Ch R = 1 ,25146   ,87.14,91.44,85.2
XS GIS Cut Line= 6
     644435.6893    4323344.2108     644156.7628     4323511.227
     644153.8903    4323514.7927     644131.5594    4323521.2485
     644116.3297    4323538.2429     643945.1509    4323668.0614
#Sta/Elev= 30
       0 1152.01   33.74 1148.59   52.14 1145.62   76.68 1143.71  116.55 1139.86
  122.68 1138.52  131.88 1137.26  138.02 1136.58  150.29 1135.99  159.49 1133.95
  187.09 1133.25  248.43 1130.43   260.7 1130.23  285.24 1129.72  300.57 1128.76
  325.11  1129.7  347.12  1129.7  360.88 1128.63   372.8 1130.18  381.91 1131.93
  388.05 1134.52   412.6 1139.35  446.36 1143.69  467.85 1145.22  483.19  1147.1
  495.47 1146.42  516.95 1148.99  547.64 1149.96   572.2 1151.62  590.61 1151.73
#Mann= 3 , 0 , 0
       0      .1       0   260.7      .1       0   372.8      .1       0
Bank Sta=260.7,372.8
XS Rating Curve= 0 ,0
Exp/Cntr=0.3,0.1

Type RM Length L Ch R = 1 ,25054.56,76.28,91.44,86.7
XS GIS Cut Line= 5
     644384.8892    4323272.7731     644135.6761    4323435.0494
     644121.6341    4323448.5299      644036.946    4323497.2943
     643841.9631    4323726.7991
#Sta/Elev= 30
       0 1152.45   67.45  1145.8   91.98 1142.76  101.17 1141.23  119.57  1139.1
   125.7 1137.93  153.29 1134.02  174.75  1132.9  245.27 1130.17  282.06 1129.73
  294.32  1128.7  302.95 1128.53  311.29 1128.59  319.91 1129.89  329.07 1131.17
  344.34 1134.85  371.83 1138.83  436.09 1143.56  445.31 1144.52   457.6 1146.33
  476.04 1146.86   491.4 1147.87  534.42    1149  552.86 1149.05  565.15 1149.51
  608.18 1149.18  635.83 1149.87  660.42  1149.9     685 1150.74  715.73 1152.32
#Mann= 3 , 0 , 0
       0      .1       0  245.27      .1       0  319.91      .1       0
Bank Sta=245.27,319.91
XS Rating Curve= 0 ,0
Exp/Cntr=0.3,0.1

Type RM Length L Ch R = 1 ,24963.12,53.33,91.44,98.52
XS GIS Cut Line= 6
     644362.3996    4323252.1356     644182.7092     4323345.446
     644103.7825    4323371.1231     644093.4694    4323372.7466
     644007.4619    4323428.1996     643726.0754    4323834.7493
#Sta/Elev= 30
       0 1152.07    3.07 1151.27     9.2 1150.67   46.02 1148.27   58.29 1146.94
  128.85 1136.89  134.98 1135.12  147.25 1133.37   171.8 1131.95  184.07 1131.58
  193.27 1131.96  253.99  1129.7  280.89 1128.43  323.65 1129.79  335.69 1133.62
  356.76 1135.22  383.85 1139.41  411.18 1141.54  435.75 1142.63  457.25 1145.48
   494.1    1148  530.95 1148.39  552.45 1147.15  647.65  1146.9   684.5 1147.66
  721.35 1149.22  773.56 1150.21   779.7 1150.71  828.84 1150.33  893.33 1151.83
#Mann= 3 , 0 , 0
       0      .1       0  253.99      .1       0  323.65      .1       0
Bank Sta=253.99,323.65
XS Rating Curve= 0 ,0
Exp/Cntr=0.3,0.1

Type RM Length L Ch R = 1 ,24871.68,95.52,91.46,57.42
XS GIS Cut Line= 6
     644335.9412    4323215.9758     644093.6181     4323326.797
     644068.3504    4323322.0345     644043.0826    4323303.1168
     643947.6786    4323357.3929     643595.1064    4323951.5189
#Sta/Elev= 30
       0 1152.51    6.13 1150.94   58.19  1146.6   88.82 1142.67  137.82 1135.03
  165.39 1132.71  251.15 1129.47  295.62 1128.39  301.67  1129.1  352.32 1128.95
  358.42 1129.49  376.71 1132.09  446.88 1135.71  480.66 1139.52  499.08 1139.59
   517.5 1140.65  560.49 1140.87  585.06 1143.15  624.97 1141.16  717.09  1140.6
  784.64 1142.06  833.77 1142.26  849.12  1143.4  892.11  1144.2  941.23 1146.89
  999.57 1148.62 1024.14 1146.93 1054.84 1149.95 1122.39 1152.41  1131.6 1152.13
#Mann= 3 , 0 , 0
       0      .1       0  251.15      .1       0  358.42      .1       0
Bank Sta=251.15,358.42
XS Rating Curve= 0 ,0
Exp/Cntr=0.3,0.1

Type RM Length L Ch R = 1 ,24780.22,86.81,91.42,77.55
XS GIS Cut Line= 6
     644291.3588    4323123.3715     644089.8665    4323224.2598
     644033.4397    4323255.1647      644026.943    4323259.2121
     643912.2255    4323334.5449     643531.6063    4323980.6232
#Sta/Elev= 30
       0 1151.88    33.5 1149.27   76.13 1143.43  118.76 1139.65  152.26 1134.71
  176.62 1132.17  200.98 1130.83   262.1 1129.81  277.42 1129.35  286.61 1128.39
  297.33 1129.22  340.03 1129.76  437.64 1133.77  471.45 1136.21  499.11 1137.31
   591.3 1137.44  625.11 1137.87  643.55 1137.53  769.55 1138.68  800.28 1139.36
  969.31 1145.11   981.6 1143.93 1006.18 1146.16 1024.62 1146.54 1086.09 1149.16
 1104.53  1148.2 1116.82 1149.46 1159.84 1151.32 1172.14 1151.35 1184.43 1150.59
#Mann= 3 , 0 , 0
       0      .1       0   262.1      .1       0  340.03      .1       0
Bank Sta=262.1,340.03
XS Rating Curve= 0 ,0
Exp/Cntr=0.3,0.1

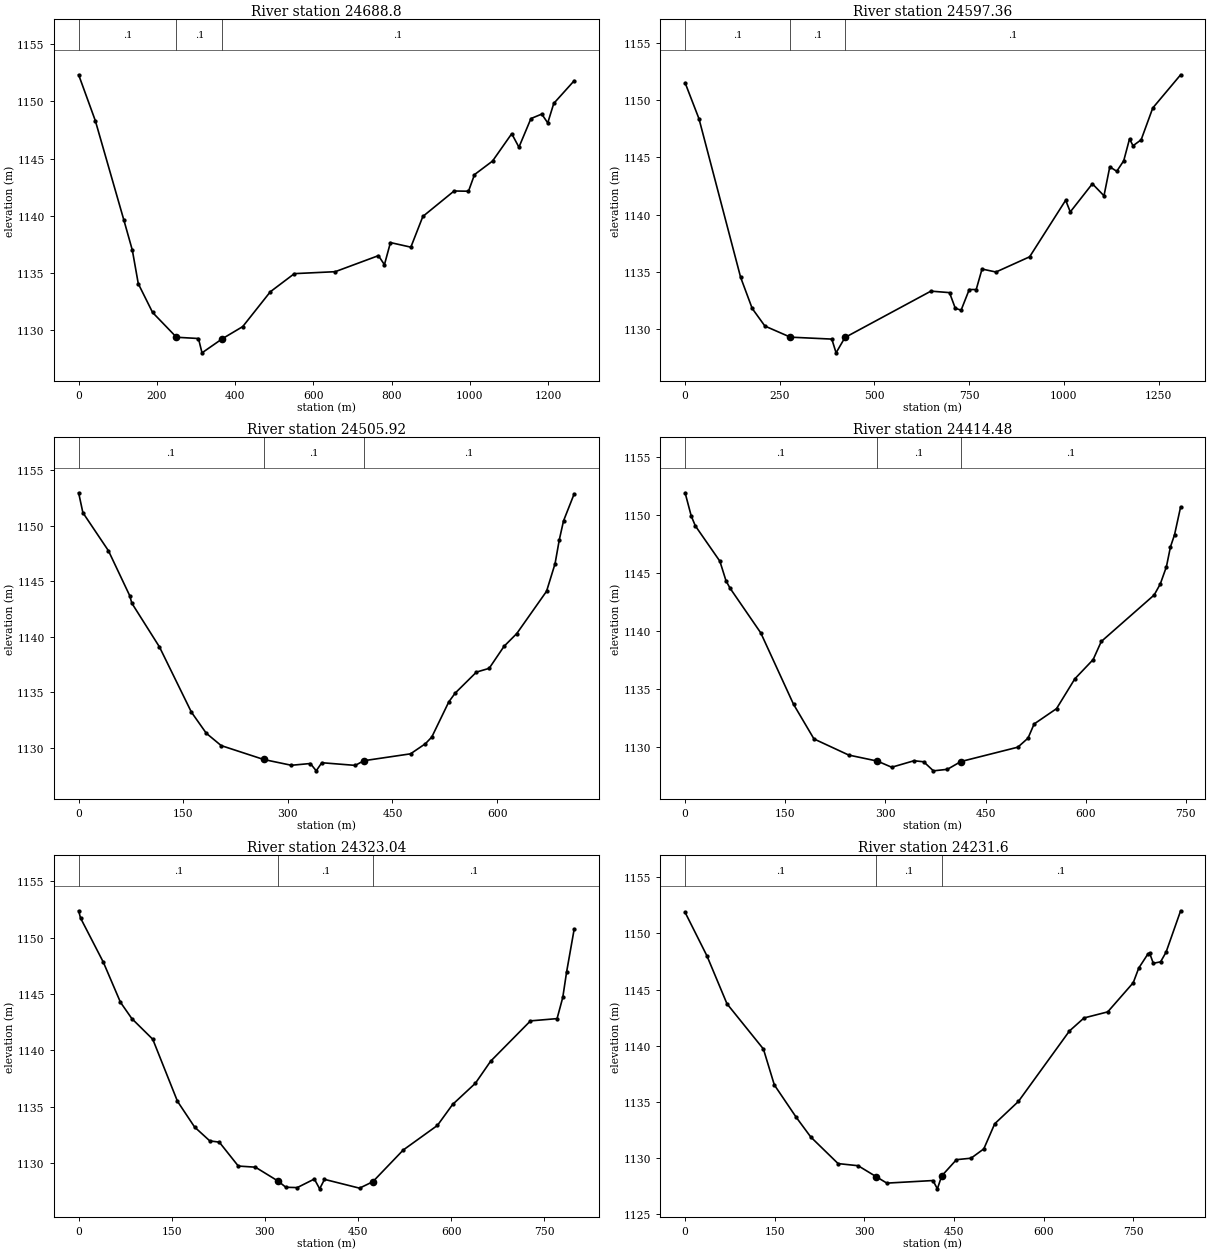
Type RM Length L Ch R = 1 ,24688.8 ,65.92,91.44,60.47
XS GIS Cut Line= 6
     644283.8182    4323114.8386      643995.054    4323179.5966
     643972.0352    4323189.2539     643965.8175    4323208.4362
     643962.6425    4323212.0081     643480.4093    4323996.8289
#Sta/Elev= 30
       0 1152.31   42.71  1148.3  115.93  1139.6  137.29 1137.01  152.54 1134.08
  189.16 1131.57  250.17 1129.41  306.37  1129.3  315.46 1128.05  367.37 1129.28
  419.57 1130.34  490.19 1133.38   551.6 1134.96  655.99 1135.13  766.53 1136.53
  781.88 1135.74  797.23 1137.67  849.43 1137.27  880.13 1139.95  959.97 1142.17
  996.81 1142.15 1012.16  1143.6 1058.22 1144.78 1107.35 1147.17 1125.77 1145.99
 1156.47 1148.49 1184.11 1148.88 1199.46 1148.11 1214.81 1149.81 1267.01 1151.79
#Mann= 3 , 0 , 0
       0      .1       0  250.17      .1       0  367.37      .1       0
Bank Sta=250.17,367.37
XS Rating Curve= 0 ,0
Exp/Cntr=0.3,0.1

Type RM Length L Ch R = 1 ,24597.36,25.8,91.44,122.8
XS GIS Cut Line= 6
      644269.222    4323107.6949     643958.0586     4323153.685
     643948.1808    4323147.9303      643932.542    4323201.2085
     643916.7416     4323220.025     643444.4259    4323987.9654
#Sta/Elev= 30
       0 1151.52   36.65 1148.38  146.58 1134.53  177.12 1131.81  210.71 1130.27
   277.9  1129.3  387.41 1129.13  398.61 1127.93  422.08 1129.27  649.01 1133.32
  698.07 1133.19  713.41 1131.82  728.74 1131.66   750.2 1133.46   768.6 1133.46
  783.94 1135.25  820.73 1134.99  909.66 1136.32 1004.73 1141.26 1016.99 1140.24
 1075.26  1142.7 1105.92 1141.65 1121.25 1144.18 1139.65 1143.79 1158.05 1144.71
 1173.39 1146.62 1182.58 1146.02 1204.05 1146.54 1234.72 1149.32 1308.31 1152.22
#Mann= 3 , 0 , 0
       0      .1       0   277.9      .1       0  422.08      .1       0
Bank Sta=277.9,422.08
XS Rating Curve= 0 ,0
Exp/Cntr=0.3,0.1

Type RM Length L Ch R = 1 ,24505.92,78.14,91.44,34.23
XS GIS Cut Line= 6
     644266.5761    4323101.0803     643938.1266     4323127.478
      643926.953    4323127.6124     643908.4642    4323130.0056
     643881.8231    4323120.7046     643558.8143    4323118.2782
#Sta/Elev= 30
       0 1152.96     6.1 1151.17   42.71 1147.75   73.22 1143.71   76.28 1143.03
  115.94 1139.09   161.7 1133.23  183.06 1131.33  204.42 1130.22  265.44 1128.97
   305.1 1128.45   332.3 1128.61  340.68 1127.95  348.67 1128.68  396.69 1128.44
  408.88 1128.86  475.92 1129.48  497.25 1130.39  506.39 1130.99  530.77 1134.15
  539.91 1134.94  570.38 1136.83  588.67 1137.17     610 1139.15  628.28  1140.3
  670.95  1144.1  683.14 1146.58  689.23 1148.73  695.33 1150.44  710.56 1152.86
#Mann= 3 , 0 , 0
       0      .1       0  265.44      .1       0  408.88      .1       0
Bank Sta=265.44,408.88
XS Rating Curve= 0 ,0
Exp/Cntr=0.3,0.1

Type RM Length L Ch R = 1 ,24414.48,88.97,91.44,92.77
XS GIS Cut Line= 6
     644258.6386    4323026.9968     643947.0007    4323049.6467
     643943.4024     4323055.785     643900.8573    4323065.0983
     643882.8656    4323098.1184     643541.6164    4323093.1427
#Sta/Elev= 30
       0 1151.89    9.19 1149.89   15.32 1149.04   52.08 1145.99   61.27  1144.3
   67.39 1143.66  113.34 1139.81  162.36 1133.66  192.99 1130.67  245.07 1129.28
  287.95 1128.76   309.4 1128.23   342.8 1128.79  357.32  1128.7  371.82 1127.92
  392.75 1128.05  412.99 1128.72  498.32 1129.96  513.55 1130.74  522.69 1131.96
  556.21 1133.28  583.64 1135.85  611.06 1137.51  623.25 1139.07  702.48 1143.08
  711.62 1144.03  720.76 1145.51  726.86 1147.23  732.95 1148.27  742.09 1150.68
#Mann= 3 , 0 , 0
       0      .1       0  287.95      .1       0  412.99      .1       0
Bank Sta=287.95,412.99
XS Rating Curve= 0 ,0
Exp/Cntr=0.3,0.1

Type RM Length L Ch R = 1 ,24323.04,31.54,91.44,109.01
XS GIS Cut Line= 6
     644295.6804    4322963.4967     643946.7156    4322973.3574
     643924.6381    4322998.8307     643919.4568    4323000.6345
     643895.8514    4323019.9974     643516.4809    4323011.1218
#Sta/Elev= 30
       0 1152.37    3.06 1151.73   39.81 1147.81   67.37 1144.26   85.74 1142.81
  119.43 1140.98  159.24 1135.48   186.8  1133.2   211.3 1131.97  226.61 1131.86
  257.23 1129.74   284.8 1129.64  321.54  1128.4  333.79 1127.86  352.17 1127.83
  379.75 1128.59   388.3 1127.72  396.09 1128.56  452.52 1127.78  473.94 1128.35
  522.91 1131.16  577.99 1133.34  602.48  1135.2   639.2 1137.08  663.68 1139.03
  727.95 1142.61  770.79 1142.81  779.97 1144.69  786.09 1146.93  798.33 1150.74
#Mann= 3 , 0 , 0
       0      .1       0  321.54      .1       0  473.94      .1       0
Bank Sta=321.54,473.94
XS Rating Curve= 0 ,0
Exp/Cntr=0.3,0.1

Type RM Length L Ch R = 1 ,24231.6 ,128.72,91.44,66.84
XS GIS Cut Line= 6
      644296.893    4322944.8655      643980.012    4322952.6432
      643925.296      4322964.47      643922.756      4322958.12
     643858.4092     4322929.545     643483.2977    4322881.3654
#Sta/Elev= 30
       0 1151.88   36.57    1148    70.1 1143.73  131.06  1139.7  149.34  1136.5
  185.92 1133.62   210.3 1131.86  256.02 1129.49  289.55  1129.3  319.92 1128.32
   337.6 1127.75  414.77 1127.98  422.17 1127.24  429.41 1128.39   454.1 1129.84
   478.5 1129.97  499.85  1130.8  518.15 1133.04   557.8 1135.03   643.2 1141.31
   667.6 1142.47  707.25 1143.01  749.95 1145.61   759.1 1146.91  774.35 1148.16
   777.4 1148.24   783.5 1147.34   795.7 1147.47  804.85 1148.33  829.25 1152.02
#Mann= 3 , 0 , 0
       0      .1       0  319.92      .1       0  429.41      .1       0
Bank Sta=319.92,429.41
XS Rating Curve= 0 ,0
Exp/Cntr=0.3,0.1

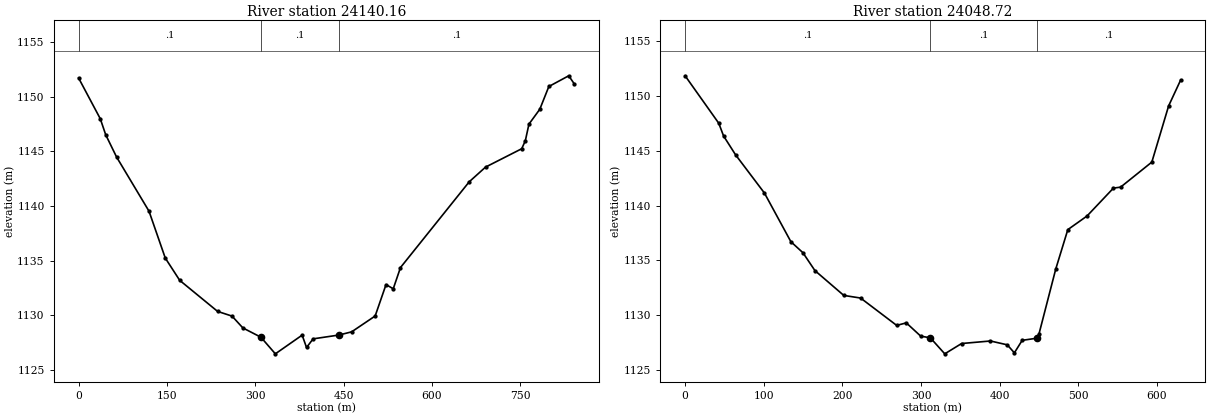
Type RM Length L Ch R = 1 ,24140.16,29.07,91.44,78.07
XS GIS Cut Line= 6
     644304.8306    4322890.6258     643952.9073    4322871.2405
     643934.1729    4322906.0078     643901.7745    4322908.7487
     643900.6104     4322913.617     643492.5581    4322858.8758
#Sta/Elev= 30
       0  1151.7   36.78 1147.98   45.97 1146.52   64.36 1144.49  119.53 1139.53
  147.11 1135.25  171.63 1133.21  235.99 1130.37  260.51 1129.94   278.9 1128.86
  309.55 1128.01  334.07 1126.49  379.58  1128.2  387.02 1127.07  398.23 1127.86
  442.13 1128.21  463.63  1128.5  503.58 1129.95  522.01 1132.82   534.3 1132.44
  546.59 1134.38  663.34 1142.22     691 1143.56  752.44 1145.24  758.59 1145.97
  764.73 1147.49  783.17 1148.85  798.53 1150.93  832.33 1151.91  841.54 1151.18
#Mann= 3 , 0 , 0
       0      .1       0  309.55      .1       0  442.13      .1       0
Bank Sta=309.55,442.13
XS Rating Curve= 0 ,0
Exp/Cntr=0.3,0.1

Type RM Length L Ch R = 1 ,24048.72,29.7,91.44,99.38
XS GIS Cut Line= 6
     644307.4764    4322884.0113     643898.9263    4322853.3667
     643890.1443    4322851.4451     643886.8757    4322850.2784
     643883.5275    4322851.1442      643690.996    4322782.1465
#Sta/Elev= 30
       0 1151.82    42.8  1147.5   48.92 1146.34   64.21 1144.62   100.9 1141.14
  134.53 1136.71  149.81 1135.71   165.1 1134.08  201.79 1131.82  223.19 1131.58
  269.06 1129.09  281.29 1129.32  299.63 1128.11  311.86 1127.96   330.2  1126.5
  351.61 1127.44   388.3 1127.67   409.7 1127.32  418.69 1126.59  428.67 1127.73
  446.98 1127.92  450.04 1128.32   471.4 1134.24  486.67 1137.81  511.09 1139.05
  544.67 1141.59  553.82 1141.68  593.51 1143.96  614.88 1149.08  630.14 1151.43
#Mann= 3 , 0 , 0
       0      .1       0  311.86      .1       0  446.98      .1       0
Bank Sta=311.86,446.98
XS Rating Curve= 0 ,0
Exp/Cntr=0.3,0.1