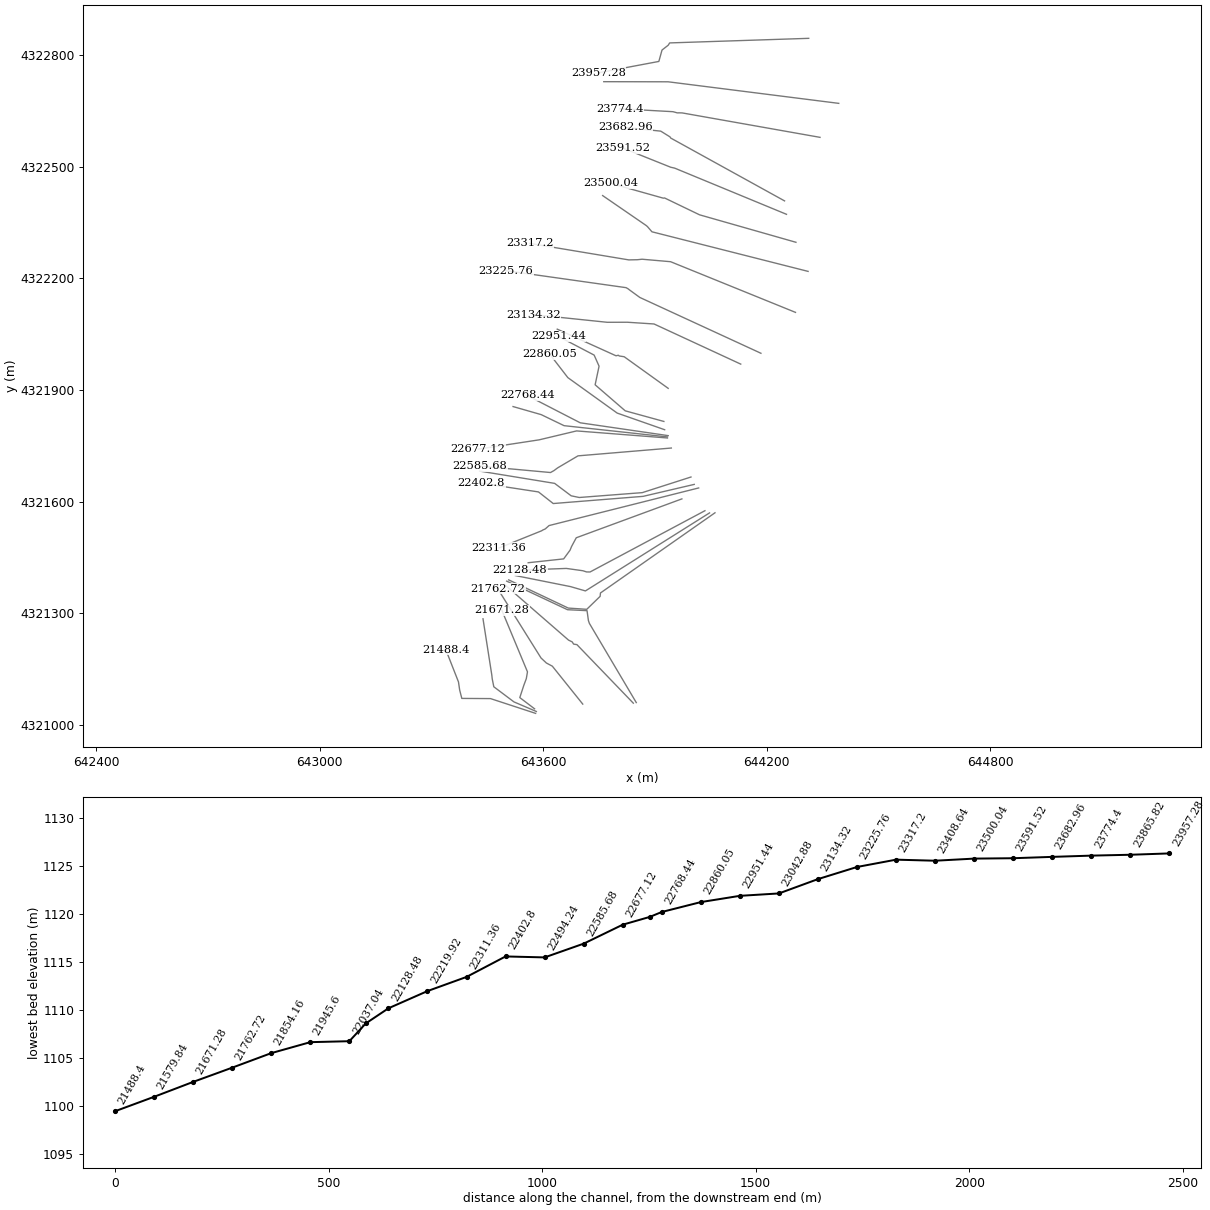
HEC-RAS study RedCreek.prj: RedCreek

--- RedCreek.g01 (geometry) --- (continued)

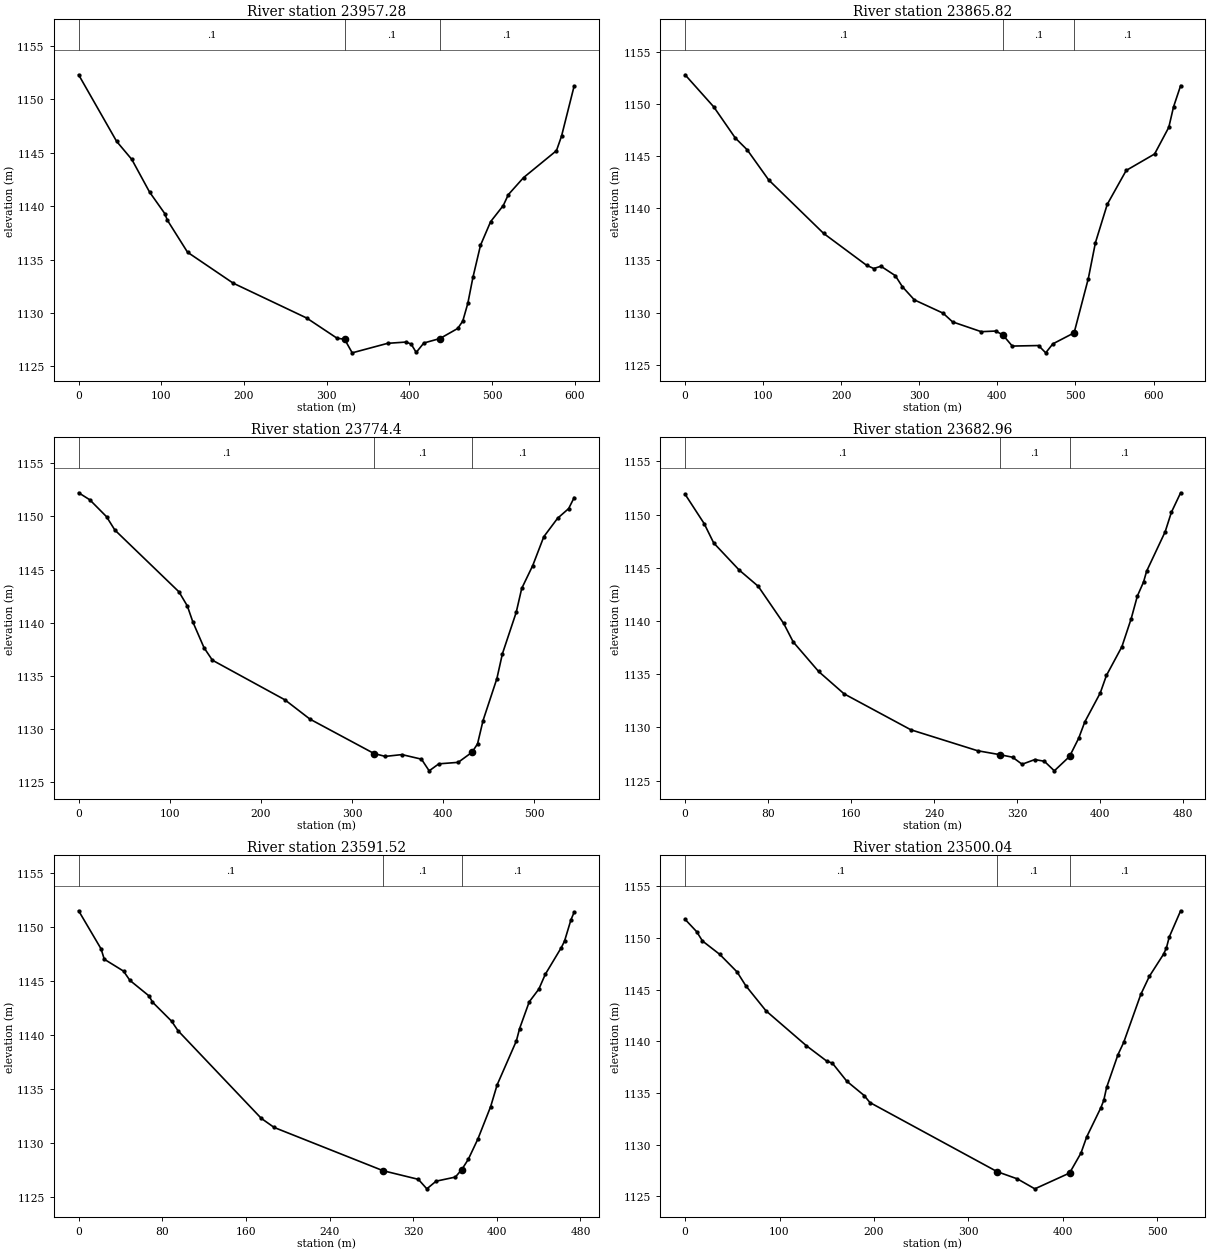
Type RM Length L Ch R = 1 ,23957.28,121.2,91.46,77.3
XS GIS Cut Line= 6
     644312.7681    4322844.3237      643939.326    4322832.0158
      643935.516    4322825.8775     643918.8346    4322812.8716
     643910.3276    4322782.2741     643747.8815    4322751.7193
#Sta/Elev= 30
       0 1152.28   45.94 1146.05   64.32 1144.36   85.75 1141.31  104.13  1139.3
  107.19 1138.69  131.69 1135.68  186.82 1132.79  275.64 1129.53  312.39 1127.64
  321.58 1127.54  330.77 1126.27  373.64 1127.16  395.98 1127.28  402.02 1127.09
  408.16 1126.31  417.38 1127.19  436.91 1127.61  458.34 1128.55  464.46 1129.24
  470.59 1130.91  476.71 1133.32  485.89 1136.33  498.13 1138.54  513.44 1140.05
  519.56 1141.07  537.93 1142.66  577.72 1145.18  583.84 1146.53  599.15 1151.24
#Mann= 3 , 0 , 0
       0      .1       0  321.58      .1       0  436.91      .1       0
Bank Sta=321.58,436.91
XS Rating Curve= 0 ,0
Exp/Cntr=0.3,0.1

Type RM Length L Ch R = 1 ,23865.82,82.62,91.42,87.02
XS GIS Cut Line= 3
     644393.4662    4322669.6983     643935.2373    4322727.6077
     643762.4336    4322727.9068
#Sta/Elev= 30
       0 1152.81   36.71 1149.73   64.23 1146.75   79.53 1145.61  107.06 1142.72
  177.41 1137.59  232.47 1134.53  241.64 1134.22  250.82 1134.44  269.17 1133.54
  278.35 1132.47  293.64 1131.21  330.35 1129.94  342.58  1129.1  379.29 1128.16
  397.64 1128.22  406.82 1127.86  419.05 1126.78   452.7 1126.83  461.87 1126.13
  470.97 1126.99  498.25 1128.05  516.44 1133.26  525.54  1136.7   540.7 1140.38
  564.95 1143.63  601.33 1145.21  619.52 1147.77  625.58 1149.73  634.68 1151.77
#Mann= 3 , 0 , 0
       0      .1       0  406.82      .1       0  498.25      .1       0
Bank Sta=406.82,498.25
XS Rating Curve= 0 ,0
Exp/Cntr=0.3,0.1

Type RM Length L Ch R = 1 ,23774.4 ,89.38,91.44,80.86
XS GIS Cut Line= 6
     644343.1952    4322578.4169     643972.9441    4322644.0363
     643964.4821    4322644.2477     643959.9839    4322644.1228
     643948.2088    4322647.3405       643806.09    4322655.1462
#Sta/Elev= 30
       0 1152.23   12.23 1151.57   30.57 1149.98   39.74 1148.72  110.05  1142.9
  119.23 1141.57  125.34 1140.05  137.57 1137.63  146.74 1136.46  226.22 1132.73
  253.74 1130.91  324.05 1127.67  336.28  1127.4  354.62 1127.57  376.02 1127.14
  384.49 1126.04  395.09  1126.7  416.33 1126.84  431.48 1127.79  437.53 1128.58
  443.59 1130.78  458.73 1134.72  464.79 1137.06  479.93 1140.96  485.99 1143.22
   498.1 1145.38  510.21 1148.09  525.35 1149.83  537.47 1150.74  543.53 1151.78
#Mann= 3 , 0 , 0
       0      .1       0  324.05      .1       0  431.48      .1       0
Bank Sta=324.05,431.48
XS Rating Curve= 0 ,0
Exp/Cntr=0.3,0.1

Type RM Length L Ch R = 1 ,23682.96,82.73,91.44,91.39
XS GIS Cut Line= 5
      644247.945    4322407.7603     643942.2424     4322576.529
     643940.3466    4322579.6054     643915.4617    4322595.0894
     643820.6421    4322604.8753
#Sta/Elev= 30
       0 1151.91   18.38 1149.15   27.57 1147.33   52.07 1144.79   70.45 1143.26
   94.96 1139.77  104.15 1138.03  128.65 1135.25  153.16 1133.15  217.48 1129.77
  281.81  1127.8  303.25 1127.43   315.5 1127.19  324.69 1126.53  336.94 1126.97
  346.13 1126.81  355.74 1125.91  370.39 1127.26  379.19 1128.97   385.1 1130.51
  399.99 1133.23  405.95 1134.88  420.84 1137.58  429.78 1140.21  435.74 1142.34
  441.69 1143.66  444.67 1144.68  462.55 1148.39   468.5 1150.21  477.44 1152.05
#Mann= 3 , 0 , 0
       0      .1       0  303.25      .1       0  370.39      .1       0
Bank Sta=303.25,370.39
XS Rating Curve= 0 ,0
Exp/Cntr=0.3,0.1

Type RM Length L Ch R = 1 ,23591.52,94.89,91.48,90.39
XS GIS Cut Line= 4
     644253.1176    4322371.7372     643952.7782     4322495.777
     643942.2078    4322498.1499     643813.9084    4322549.5376
#Sta/Elev= 30
       0 1151.54   21.46 1148.01   24.52 1147.05   42.92 1145.95   49.05 1145.09
   67.44 1143.64   70.51 1143.09    88.9 1141.31   95.03 1140.43  174.73  1132.3
     187 1131.46  291.22 1127.45  324.95 1126.65  333.07 1125.77  341.92 1126.48
  360.35 1126.86  366.49 1127.56  372.63 1128.49  381.85 1130.38  394.13  1133.4
  400.28  1135.4   418.7 1139.48  421.78 1140.62  430.99  1143.1   440.2 1144.28
  446.35 1145.65   461.7 1148.13  464.77 1148.73  470.92 1150.71  473.99 1151.41
#Mann= 3 , 0 , 0
       0      .1       0  291.22      .1       0  366.49      .1       0
Bank Sta=291.22,366.49
XS Rating Curve= 0 ,0
Exp/Cntr=0.3,0.1

Type RM Length L Ch R = 1 ,23500.04,98.19,91.4,87.07
XS GIS Cut Line= 5
     644278.5177    4322296.5954     644019.5985    4322370.3945
     643925.6591    4322415.6613     643922.1407    4322415.1296
     643779.8653    4322455.1252
#Sta/Elev= 30
       0 1151.81   12.24 1150.62   18.36 1149.72   36.71 1148.42   55.07 1146.72
   64.25 1145.39   85.66 1142.96   128.5 1139.58  149.91  1138.1  156.03 1137.89
  171.33 1136.14  189.69 1134.76   195.8 1134.08  330.57 1127.39  352.04 1126.69
  370.44 1125.73  407.23 1127.26  419.29 1129.19  425.32 1130.75  440.41 1133.59
  443.42 1134.29  446.44 1135.54   458.5 1138.72  464.53  1139.9  482.63 1144.54
  491.68 1146.29  506.76 1148.44  509.78 1149.04  512.79  1150.1  524.86 1152.64
#Mann= 3 , 0 , 0
       0      .1       0  330.57      .1       0  407.23      .1       0
Bank Sta=330.57,407.23
XS Rating Curve= 0 ,0
Exp/Cntr=0.3,0.1

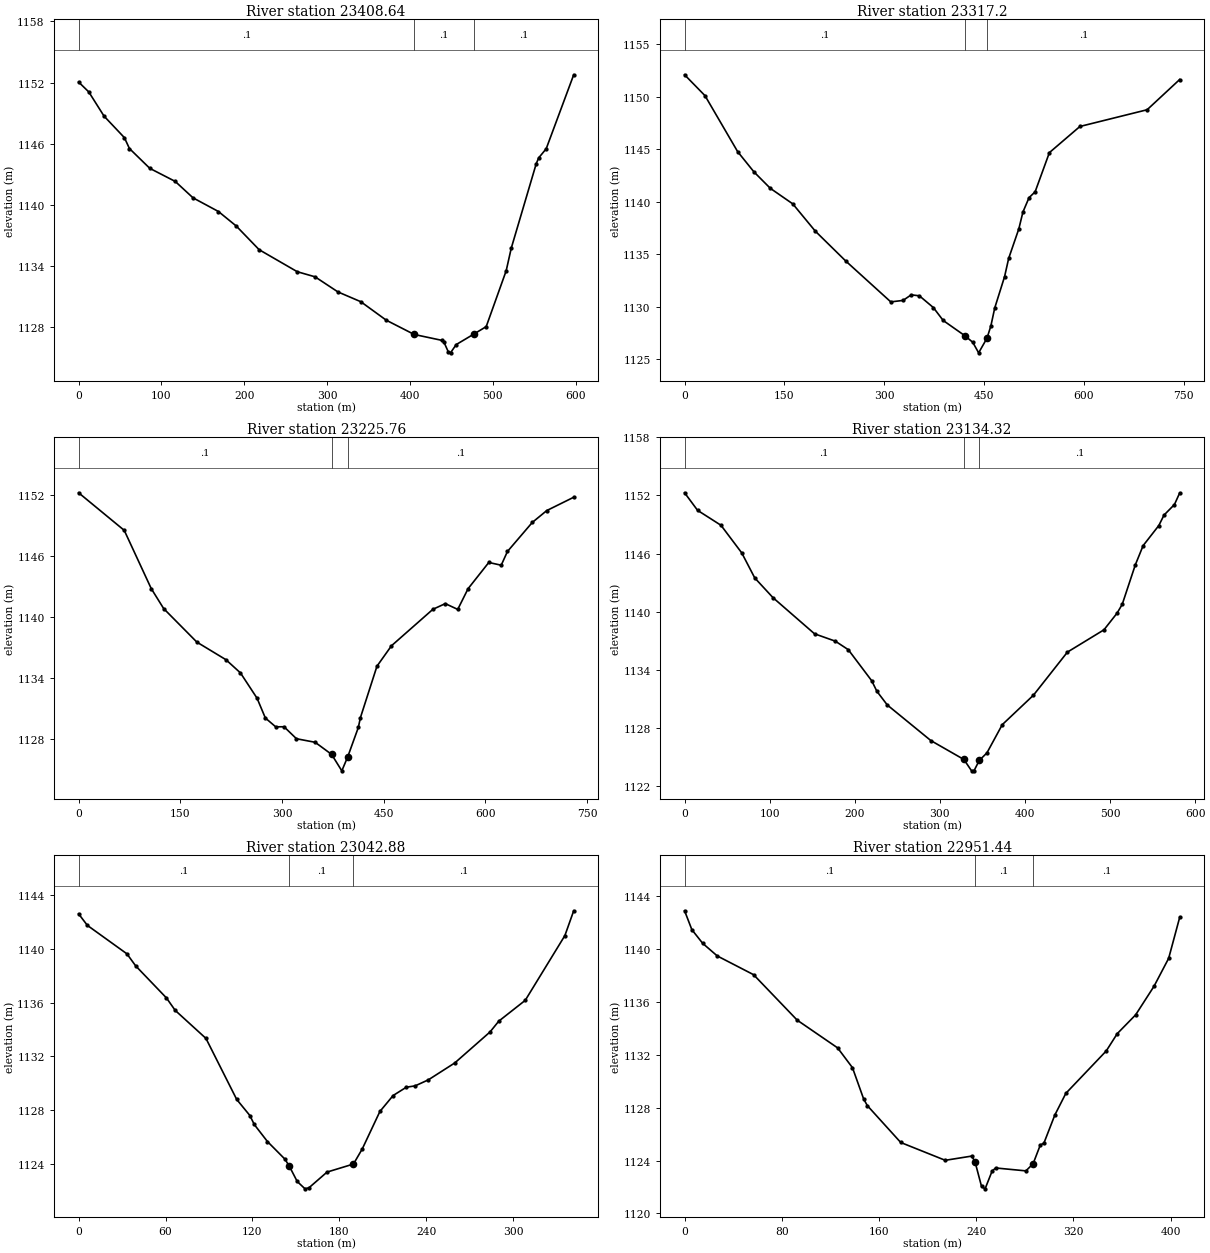
Type RM Length L Ch R = 1 ,23408.64,79.23,91.44,111.64
XS GIS Cut Line= 5
     644311.1497     4322218.455     643891.8114     4322324.787
     643879.4215    4322339.0542     643876.2126    4322341.7337
     643759.3601    4322422.0522
#Sta/Elev= 30
       0 1152.05   12.27 1151.08   30.68 1148.71   55.23  1146.6   61.36 1145.53
   85.91 1143.59  116.59 1142.31  138.07  1140.7  168.75 1139.36  190.23 1137.94
  217.84 1135.62  263.86 1133.46  285.34 1132.96  312.95 1131.48  340.56 1130.52
  371.25 1128.71     405 1127.31  438.01 1126.74  440.71 1126.59  446.11 1125.61
  448.81 1125.51  455.69 1126.32   476.8 1127.34  491.89 1128.08  516.02 1133.56
  522.06 1135.75  552.23 1144.04  555.24 1144.62  564.29 1145.51  597.48 1152.76
#Mann= 3 , 0 , 0
       0      .1       0     405      .1       0   476.8      .1       0
Bank Sta=405,476.8
XS Rating Curve= 0 ,0
Exp/Cntr=0.3,0.1

Type RM Length L Ch R = 1 ,23317.2 ,101.5,91.44,84.91
XS GIS Cut Line= 6
      644277.283    4322108.3881     643941.8436     4322244.464
     643865.2397    4322251.1274     643852.7129    4322249.7856
     643829.5209    4322249.3246     643563.9649    4322293.5968
#Sta/Elev= 30
       0 1152.09   30.68  1150.1   79.76 1144.77   104.3 1142.84  128.84 1141.28
  162.59  1139.8  196.33 1137.21  242.35 1134.35  309.84 1130.47  328.24 1130.61
  340.52 1131.14  352.79 1131.05  373.82 1129.93  388.61  1128.7  421.14 1127.25
  432.97 1126.63  441.86 1125.62  454.44 1127.02  460.24 1128.18  466.04 1129.89
  480.86 1132.88  486.98 1134.61  502.28 1137.43  508.39 1139.02  517.57 1140.39
  526.75 1140.95  548.17 1144.68  594.06 1147.17  695.01 1148.76  743.96 1151.64
#Mann= 3 , 0 , 0
       0      .1       0  421.14      .1       0  454.44      .1       0
Bank Sta=421.14,454.44
XS Rating Curve= 0 ,0
Exp/Cntr=0.3,0.1

Type RM Length L Ch R = 1 ,23225.76,81.14,91.44,96.28
XS GIS Cut Line= 6
     644184.5022    4321998.5417     643859.2667     4322148.452
     643831.3485     4322168.805     643827.9578    4322171.4907
     643822.3662    4322174.7499     643498.7009    4322220.5275
#Sta/Elev= 30
       0 1152.23   67.34 1148.53  107.13  1142.8   125.5 1140.83  174.47 1137.53
  217.32  1135.8  238.75  1134.5  263.23 1132.01  275.48 1130.06  290.78 1129.19
  303.03  1129.2  321.39 1128.02  348.94 1127.67   373.2 1126.48  388.27 1124.86
     397 1126.24  412.64 1129.13  415.69 1130.09  440.13 1135.16  461.52 1137.17
  522.62 1140.76  540.95 1141.32  559.28 1140.75  574.55 1142.79   605.1 1145.37
  623.43  1145.1   632.6 1146.45  669.26 1149.31  690.64 1150.48  730.36 1151.79
#Mann= 3 , 0 , 0
       0      .1       0   373.2      .1       0     397      .1       0
Bank Sta=373.2,397
XS Rating Curve= 0 ,0
Exp/Cntr=0.3,0.1

Type RM Length L Ch R = 1 ,23134.32,95.22,91.44,91.33
XS GIS Cut Line= 5
     644130.2625    4321969.4374     643897.4272     4322077.231
     643825.8622     4322081.884     643771.7534    4322081.7477
     643573.3135    4322102.3908
#Sta/Elev= 30
       0 1152.27   15.27 1150.46   42.76 1148.92    67.2 1146.07   82.47 1143.49
  103.85 1141.46  152.72 1137.73  177.16 1136.97  192.43 1136.09  219.92 1132.89
  226.03  1131.8  238.25 1130.39  289.45 1126.72  328.29 1124.77  337.31  1123.6
  340.32 1123.63  346.33 1124.67  355.35 1125.45  373.38 1128.36  410.03  1131.4
  449.93 1135.84   492.9 1138.14  508.25 1139.85  514.39 1140.77  529.73 1144.83
  538.94 1146.82  557.36 1148.89   563.5 1149.97  575.77 1151.06  581.91 1152.25
#Mann= 3 , 0 , 0
       0      .1       0  328.29      .1       0  346.33      .1       0
Bank Sta=328.29,346.33
XS Rating Curve= 0 ,0
Exp/Cntr=0.3,0.1

Type RM Length L Ch R = 1 ,23042.88,103.82,91.44,61.63
XS GIS Cut Line= 6
     643935.4211    4321904.3634     643817.2126    4321989.2529
      643803.842    4321991.3104     643801.5742    4321993.3044
     643795.3391    4321991.7883      643637.442    4322063.3316
#Sta/Elev= 30
       0 1142.62    6.06 1141.76   33.35 1139.64   39.41 1138.74   60.64 1136.35
    66.7 1135.42   87.93 1133.33  109.15 1128.78  118.24 1127.58  121.28 1126.91
  130.37 1125.64   142.5 1124.32  145.53 1123.79  150.94 1122.66  156.35 1122.11
  159.06 1122.19  171.54 1123.36  189.78 1123.96  195.87 1125.09  208.03 1127.88
  217.16 1129.07  226.28 1129.69  232.36 1129.79  241.49 1130.24  259.73  1131.5
  284.06 1133.81  290.14 1134.62  308.39 1136.17  335.76    1141  341.85 1142.85
#Mann= 3 , 0 , 0
       0      .1       0  145.53      .1       0  189.78      .1       0
Bank Sta=145.53,189.78
XS Rating Curve= 0 ,0
Exp/Cntr=0.3,0.1

Type RM Length L Ch R = 1 ,22951.44,75.5,91.39,95.62
XS GIS Cut Line= 6
      643923.821    4321815.4662     643820.0486     4321843.977
     643739.2019    4321913.8796     643749.7852     4321963.886
      643736.556    4321993.6605     643640.1871    4322044.0666
#Sta/Elev= 30
       0 1142.91    5.98 1141.48   14.95 1140.44    26.9 1139.49    56.8 1138.07
   92.67 1134.63  125.94 1132.53  138.15 1131.03  147.31 1128.67  150.37 1128.16
  177.85 1125.37  214.49 1124.02  236.29 1124.34  238.98 1123.91  244.35 1122.04
  247.26 1121.86  253.07 1123.21  255.98 1123.44  280.86 1123.22  286.78 1123.76
  292.71 1125.18  295.67 1125.32  304.67 1127.45  313.73 1129.09  346.97  1132.3
  356.03 1133.61  371.13 1135.03  386.24 1137.19  398.32 1139.31  407.39 1142.41
#Mann= 3 , 0 , 0
       0      .1       0  238.98      .1       0  286.78      .1       0
Bank Sta=238.98,286.78
XS Rating Curve= 0 ,0
Exp/Cntr=0.3,0.1

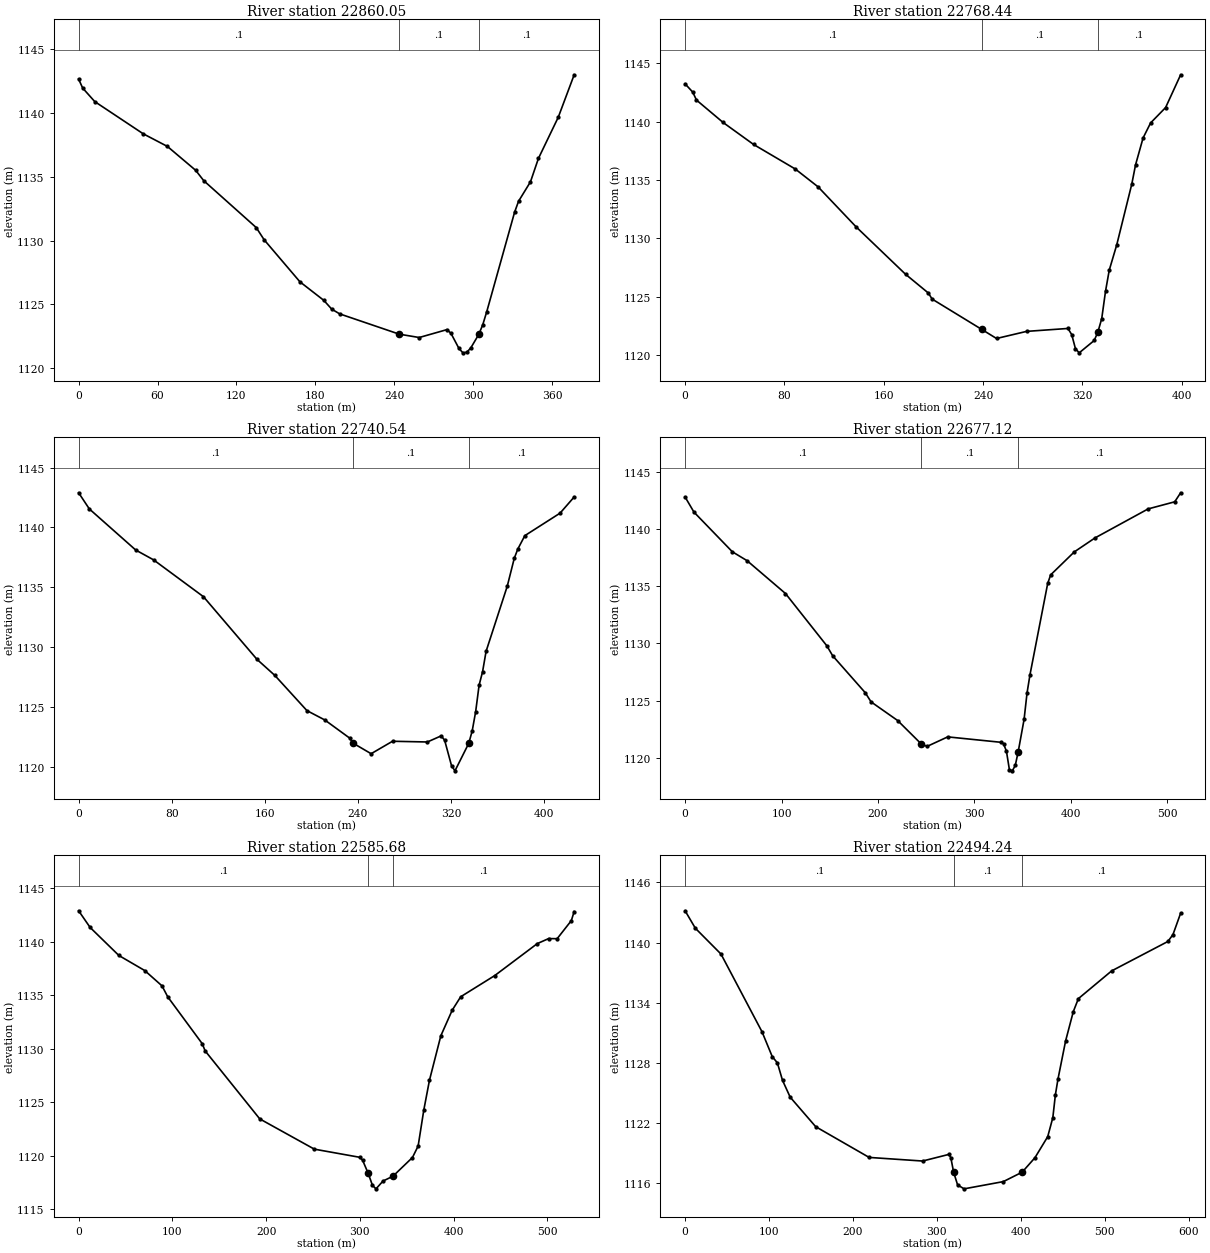
Type RM Length L Ch R = 1 ,22860.05,90.28,91.6,95.6
XS GIS Cut Line= 4
     643925.9377    4321793.2411     643798.4906     4321837.898
     643665.9148    4321933.1781      643617.962    4321995.3832
#Sta/Elev= 30
       0 1142.64    3.07 1141.94   12.28 1140.88   49.11 1138.36   67.52 1137.37
   89.01  1135.5   95.14 1134.69  135.04 1131.02  141.09 1130.06   168.3 1126.77
  186.44 1125.32  192.49 1124.63  198.54 1124.26  243.89 1122.67     259 1122.41
  280.17 1123.03  283.19 1122.73  289.24 1121.55  292.26 1121.21  295.28 1121.26
  298.31 1121.61  304.35 1122.66  307.37 1123.42  310.39 1124.44  331.54 1132.22
  334.56 1133.08  343.62  1134.6  349.66 1136.43  364.77 1139.66  376.85 1142.98
#Mann= 3 , 0 , 0
       0      .1       0  243.89      .1       0  304.35      .1       0
Bank Sta=243.89,304.35
XS Rating Curve= 0 ,0
Exp/Cntr=0.3,0.1

Type RM Length L Ch R = 1 ,22768.44,27.58,27.91,28.16
XS GIS Cut Line= 3
     643935.4627    4321777.3661     643699.1648    4321811.8261
     643556.5786    4321885.3163
#Sta/Elev= 30
       0 1143.24    6.12 1142.54    9.18 1141.85   30.62 1139.93   55.11 1138.05
   88.78 1135.94  107.15 1134.41  137.77 1130.98  177.57 1126.92  195.94 1125.31
     199 1124.79   238.8  1122.2   250.9 1121.41  275.12 1122.02  308.41 1122.27
  311.44 1121.75  314.46 1120.54  317.49 1120.18   329.6 1121.24  332.62 1121.99
  335.65 1123.12  338.68 1125.45   341.7 1127.27  347.76 1129.45  359.86 1134.65
  362.89  1136.3  368.94  1138.6     375 1139.89   387.1 1141.21  399.21 1144.02
#Mann= 3 , 0 , 0
       0      .1       0   238.8      .1       0  332.62      .1       0
Bank Sta=238.8,332.62
XS Rating Curve= 0 ,0
Exp/Cntr=0.3,0.1

Type RM Length L Ch R = 1 ,22740.54,48.72,63.42,65.49
XS GIS Cut Line= 4
     643933.0996    4321773.9557     643655.8157    4321804.1183
     643594.4323    4321833.7517     643518.7613    4321855.4475
#Sta/Elev= 30
       0 1142.89     9.2 1141.54   49.04 1138.11   64.37 1137.29  107.28 1134.21
  153.25 1128.98  168.58 1127.64  196.16  1124.7  211.49 1123.92  232.94  1122.4
  236.01 1121.97  251.33  1121.1  269.72 1122.14  299.66 1122.08  311.52 1122.59
  314.48 1122.23  320.41  1120.1  323.37 1119.67  335.23 1121.97  338.19 1123.01
  341.15 1124.61  344.12 1126.83  347.08 1127.94  350.11 1129.65  368.28 1135.08
  374.33 1137.42  377.36 1138.19  383.41 1139.31  413.69 1141.19   425.8 1142.54
#Mann= 3 , 0 , 0
       0      .1       0  236.01      .1       0  335.23      .1       0
Bank Sta=236.01,335.23
XS Rating Curve= 0 ,0
Exp/Cntr=0.3,0.1

Type RM Length L Ch R = 1 ,22677.12,84.94,91.44,93.82
XS GIS Cut Line= 4
     643933.5312    4321771.0558     643689.3651     4321790.016
     643588.6358     4321766.033     643425.1333    4321741.0916
#Sta/Elev= 30
       0 1142.81    9.18 1141.49   48.98 1138.02   64.29 1137.24  104.08 1134.37
  146.94  1129.8  153.06 1128.92  186.74  1125.7  192.86 1124.89  220.41 1123.26
   244.9 1121.21  250.99    1121  272.31 1121.83  327.13 1121.36  330.17 1121.24
  333.22 1120.57  336.26 1118.97  339.31 1118.86  342.36 1119.33   345.4 1120.53
  351.51 1123.36  354.57 1125.67  357.63 1127.27  376.01 1135.26  379.07    1136
  403.58 1138.01  425.02 1139.23  480.15 1141.77  507.71 1142.39  513.84 1143.18
#Mann= 3 , 0 , 0
       0      .1       0   244.9      .1       0   345.4      .1       0
Bank Sta=244.9,345.4
XS Rating Curve= 0 ,0
Exp/Cntr=0.3,0.1

Type RM Length L Ch R = 1 ,22585.68,96.72,91.44,37.15
XS GIS Cut Line= 6
       643943.85    4321744.0682     643693.2376    4321723.0736
     643638.5284    4321690.7803     643628.6357    4321683.4539
     643619.3834    4321678.2873      643429.499    4321695.6494
#Sta/Elev= 30
       0 1142.89   12.27 1141.33   42.94 1138.71   70.54  1137.3   88.94 1135.87
   95.08 1134.84  131.88 1130.46  134.95 1129.79  193.22 1123.43  251.49  1120.6
  299.84 1119.84  302.86 1119.58   308.9 1118.34  313.48 1117.21  317.24 1116.89
  324.73 1117.62  335.31 1118.07  356.12 1119.82  362.18 1120.89  368.23 1124.26
  374.28 1127.05  386.39  1131.2   398.5 1133.59  407.58 1134.85  443.89 1136.83
  489.29 1139.82   501.4 1140.29  510.48 1140.28  525.61 1141.97  528.64 1142.82
#Mann= 3 , 0 , 0
       0      .1       0   308.9      .1       0  335.31      .1       0
Bank Sta=308.9,335.31
XS Rating Curve= 0 ,0
Exp/Cntr=0.3,0.1

Type RM Length L Ch R = 1 ,22494.24,91.13,91.44,50.93
XS GIS Cut Line= 6
     643996.6345    4321666.2541     643865.7804    4321624.2814
     643696.5338    4321611.2323      643674.851    4321615.7858
      643630.443    4321649.1699     643429.1021    4321682.1291
#Sta/Elev= 30
       0 1143.16   12.22 1141.42   42.75 1138.85   91.61 1131.11  103.83 1128.63
  109.94 1128.01  116.04 1126.27  125.21 1124.59  155.61 1121.65  219.26 1118.59
  282.92 1118.23   314.2 1118.89  316.54 1118.57  319.94 1117.11  324.64 1115.85
   332.4 1115.46   379.1 1116.18  401.56 1117.12  416.78 1118.56  432.01 1120.66
   438.1 1122.56  441.14 1124.83  444.19 1126.38  453.32  1130.2  462.46 1133.11
  468.55 1134.41  508.14 1137.17  575.13  1140.1  581.22 1140.79  590.35 1142.92
#Mann= 3 , 0 , 0
       0      .1       0  319.94      .1       0  401.56      .1       0
Bank Sta=319.94,401.56
XS Rating Curve= 0 ,0
Exp/Cntr=0.3,0.1

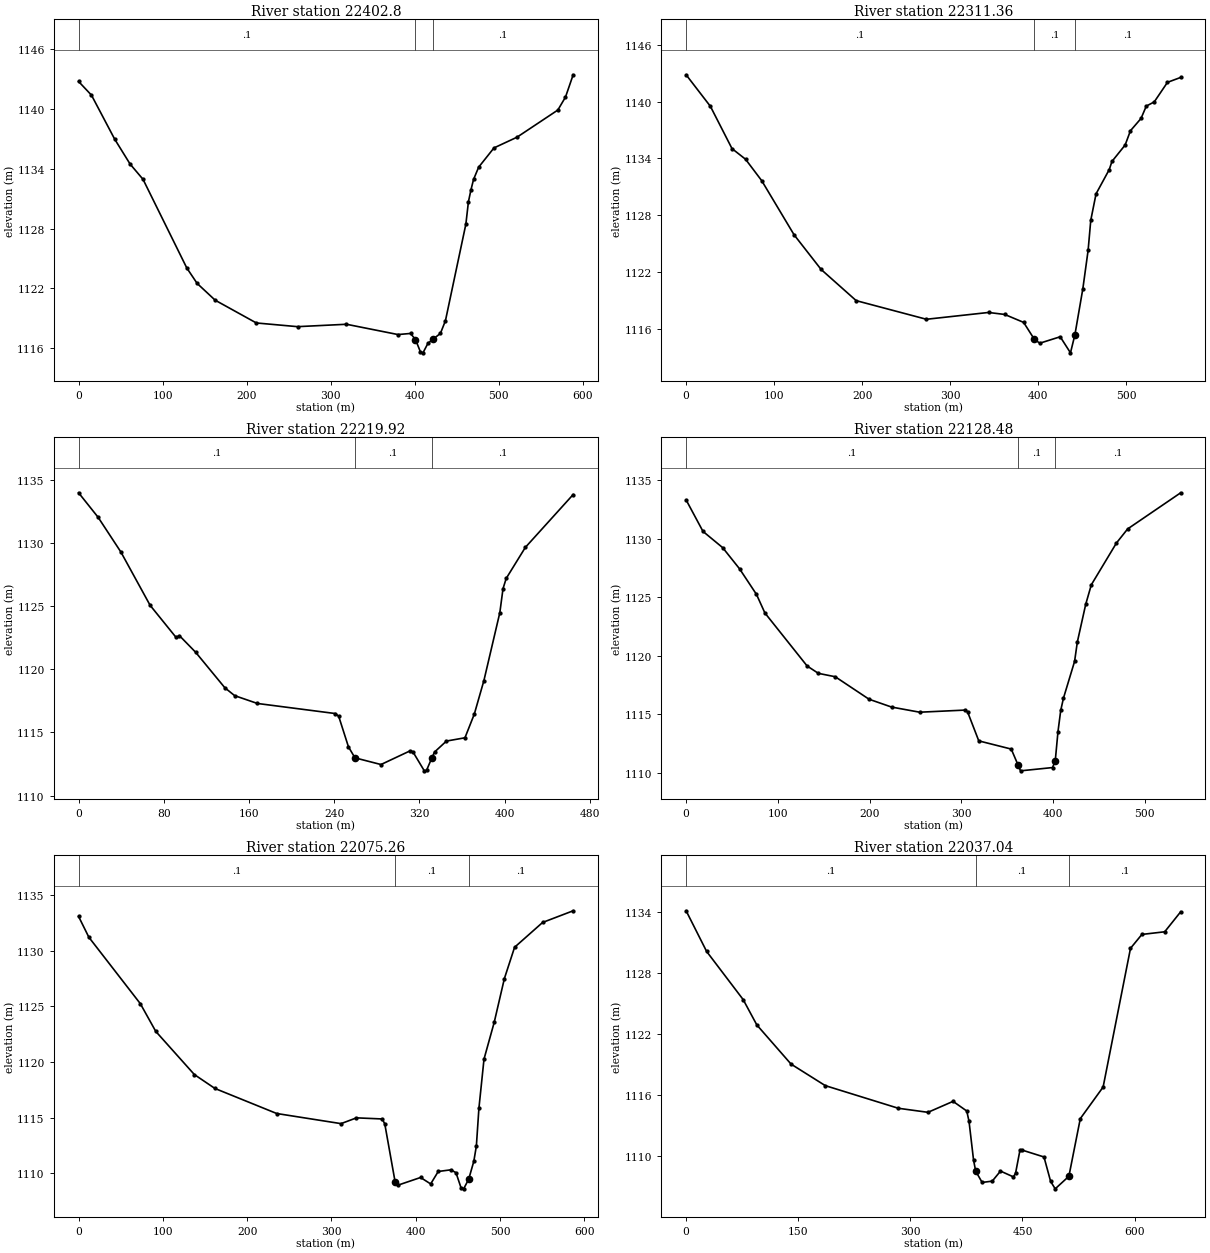
Type RM Length L Ch R = 1 ,22402.8 ,79.39,91.44,108.87
XS GIS Cut Line= 5
     644005.3657    4321646.4103      643868.013    4321614.2883
     643626.6862    4321595.0077     643587.1172    4321626.1576
     643433.8646    4321649.5853
#Sta/Elev= 30
       0 1142.72   15.33 1141.35   42.93 1136.95   61.33 1134.45   76.66 1132.93
  128.79 1124.05  141.06 1122.51  162.51 1120.83  211.54 1118.55  260.57 1118.18
   318.8 1118.42  380.09 1117.39     395  1117.5  400.93 1116.89  406.85 1115.64
  409.82 1115.56  415.74 1116.51  421.66 1116.92  430.55  1117.5  436.55 1118.77
  460.87 1128.44  463.91 1130.68  466.95 1131.88  469.99 1132.91  476.07 1134.14
  494.31 1136.07  521.67 1137.14  570.31 1139.86  579.43 1141.16  588.55 1143.39
#Mann= 3 , 0 , 0
       0      .1       0  400.93      .1       0  421.66      .1       0
Bank Sta=400.93,421.66
XS Rating Curve= 0 ,0
Exp/Cntr=0.3,0.1

Type RM Length L Ch R = 1 ,22311.36,83.01,91.44,97.7
XS GIS Cut Line= 6
      644017.272    4321636.8853     643615.4506     4321535.855
     643605.2906    4321526.8062     643598.9457    4321524.0088
     643595.5358    4321521.8376     643481.2251    4321475.7537
#Sta/Elev= 30
       0 1142.84   27.62  1139.5   52.17 1135.03   67.52 1133.91   85.93 1131.64
  122.76 1125.91  153.45 1122.25  193.35 1118.95  273.15 1116.98  343.74  1117.7
  362.15 1117.49  383.64 1116.65  395.91 1114.85  402.05 1114.45  425.21 1115.13
  436.89 1113.43  441.92 1115.34  450.93  1120.2  456.95 1124.28  459.95 1127.45
  465.97 1130.25     481 1132.82     484 1133.67  499.03 1135.41  505.04 1136.92
  517.07 1138.22  523.08 1139.53   532.1 1139.97  547.13 1142.04  562.16 1142.56
#Mann= 3 , 0 , 0
       0      .1       0  395.91      .1       0  441.92      .1       0
Bank Sta=395.91,441.92
XS Rating Curve= 0 ,0
Exp/Cntr=0.3,0.1

Type RM Length L Ch R = 1 ,22219.92,105.62,91.44,67.89
XS GIS Cut Line= 6
     643972.1869      4321607.49     643688.5198    4321503.0598
     643675.9559    4321479.6857      643671.851    4321469.7223
     643654.6863    4321446.3585     643559.4361    4321436.0397
#Sta/Elev= 30
       0    1134   18.32 1132.06   39.69 1129.31   67.17 1125.08    91.6 1122.53
   94.65 1122.68  109.92 1121.36   137.4 1118.54  146.56 1117.92  167.93  1117.3
  241.21  1116.5  244.27 1116.28  253.43 1113.86  259.53 1112.99  283.96 1112.46
  310.96 1113.53  313.86 1113.48  324.65 1111.96  326.75    1112  331.55 1112.95
  334.24 1113.45  345.43 1114.32  362.82 1114.58  371.61 1116.46   380.6 1119.11
  395.57  1124.5  398.56  1126.4  401.55 1127.21  419.52 1129.67  464.43 1133.86
#Mann= 3 , 0 , 0
       0      .1       0  259.53      .1       0  331.55      .1       0
Bank Sta=259.53,331.55
XS Rating Curve= 0 ,0
Exp/Cntr=0.3,0.1

Type RM Length L Ch R = 1 ,22128.48,43.97,53.22,49.24
XS GIS Cut Line= 6
     644034.0995      4321575.74     643725.5704    4321411.1963
     643716.1563    4321411.3371     643706.2747    4321414.5289
     643661.9108    4321420.7416      643537.211    4321416.1959
#Sta/Elev= 30
       0 1133.32    18.4 1130.63   39.87 1129.24   58.28 1127.43   76.68 1125.25
   85.88 1123.66  131.89 1119.13  144.16  1118.5  162.56 1118.21  199.37 1116.29
  223.91 1115.62  254.58 1115.18  303.66 1115.36  306.72 1115.22  318.99 1112.73
  354.37 1112.03  361.79 1110.67   364.5 1110.17  399.34 1110.45  402.32 1111.01
  405.31 1113.52   408.3 1115.33  411.28 1116.38   423.4 1119.52  426.44 1121.19
  435.57 1124.41  441.66 1126.07  469.05 1129.64  481.23 1130.84  539.05 1133.93
#Mann= 3 , 0 , 0
       0      .1       0  361.79      .1       0  402.32      .1       0
Bank Sta=361.79,402.32
XS Rating Curve= 0 ,0
Exp/Cntr=0.3,0.1

Type RM Length L Ch R = 1 ,22075.26,33.68,38.22,96.71
XS GIS Cut Line= 4
     644046.5179    4321569.8733     643713.1422    4321360.3229
     643672.9255    4321371.9646     643524.7585     4321401.598
#Sta/Elev= 30
       0 1133.07   12.21  1131.2   73.26 1125.23   91.57 1122.74  137.36 1118.86
  161.78 1117.61  235.04 1115.36  311.35 1114.45  329.66 1114.97  360.19 1114.87
  363.24 1114.43  375.45 1109.24   378.5 1108.91  405.73 1109.61  417.69 1109.03
  426.66 1110.15  441.68  1110.3  447.72 1110.04  453.77 1108.67  456.79 1108.59
  462.83 1109.46  468.88 1111.07   471.9 1112.44  474.92 1115.83  480.96 1120.25
  493.05 1123.55  505.14 1127.49  517.23  1130.3  550.47 1132.53  586.73 1133.58
#Mann= 3 , 0 , 0
       0      .1       0  375.45      .1       0  462.83      .1       0
Bank Sta=375.45,462.83
XS Rating Curve= 0 ,0
Exp/Cntr=0.3,0.1

Type RM Length L Ch R = 1 ,22037.04,121.69,91.44,40.44
XS GIS Cut Line= 6
     644061.0871    4321570.1837      643753.506    4321354.8135
     643752.6358    4321345.7683       643716.75    4321310.9617
      643667.083    4321314.2825     643507.0485    4321390.0021
#Sta/Elev= 30
       0 1134.15   27.47 1130.14   76.32  1125.4   94.63  1122.9  140.43 1119.04
  186.22 1116.92   283.9 1114.69  323.59 1114.29  357.17 1115.37  375.49 1114.42
  378.52  1113.4  384.57 1109.59  387.45 1108.49  396.07 1107.38  409.61 1107.51
  420.63  1108.5  437.82 1107.93  440.74 1108.27   446.6 1110.53  449.53 1110.57
  478.81 1109.89  487.72 1107.48  493.82 1106.75  512.14 1107.99   527.4 1113.67
  557.93 1116.78  594.56 1130.45  609.82 1131.82  640.34 1132.08  661.71 1134.05
#Mann= 3 , 0 , 0
       0      .1       0  387.45      .1       0  512.14      .1       0
Bank Sta=387.45,512.14
XS Rating Curve= 0 ,0
Exp/Cntr=0.3,0.1

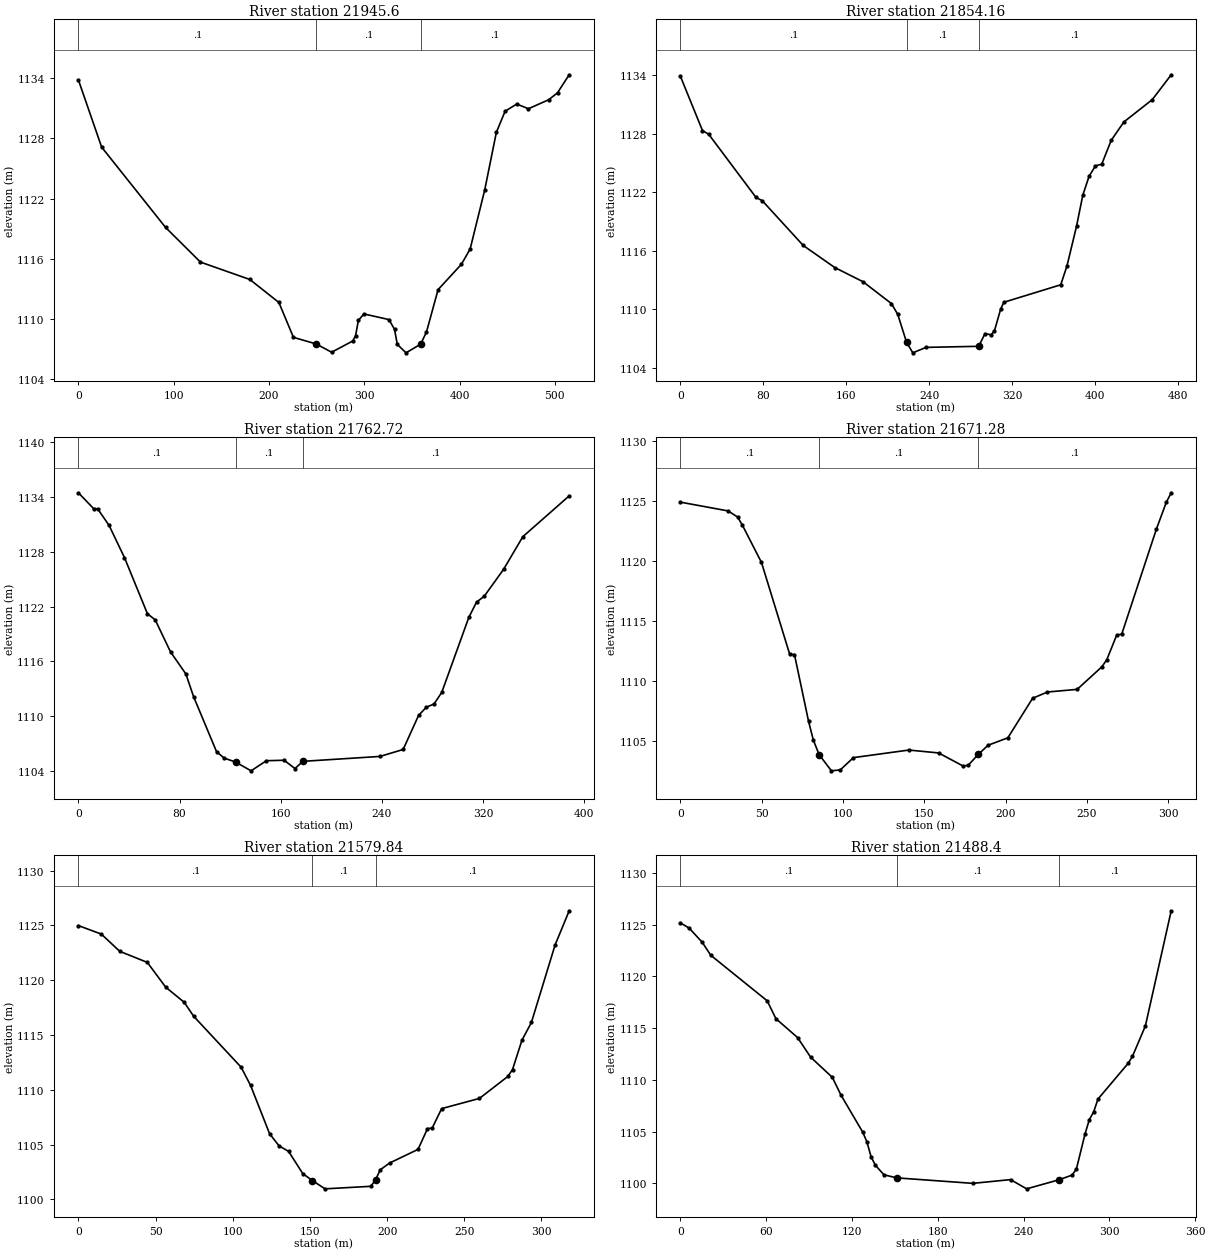
Type RM Length L Ch R = 1 ,21945.6 ,75.47,91.44,97.82
XS GIS Cut Line= 6
     643849.6948     4321060.482      643723.833    4321273.0483
     643721.2035    4321280.6616     643717.4829    4321307.3383
     643664.9895    4321309.8783     643501.7171    4321386.6066
#Sta/Elev= 30
       0 1133.81    24.4 1127.12   91.49 1119.13  128.09 1115.68  179.94 1113.95
  210.44 1111.66  225.69 1108.19  249.72 1107.53  265.76 1106.71  287.99 1107.83
  290.91 1108.35  293.83 1109.88  299.67 1110.52  325.94 1109.96  331.78 1108.99
   334.7 1107.49  343.87 1106.65  359.16 1107.51  365.28 1108.71  377.51 1112.94
  401.97 1115.46  411.14 1116.98  426.43 1122.85  438.66 1128.59  447.84 1130.69
  460.07 1131.41   472.3 1130.94   493.7 1131.84  502.87 1132.53   515.1 1134.32
#Mann= 3 , 0 , 0
       0      .1       0  249.72      .1       0  359.16      .1       0
Bank Sta=249.72,359.16
XS Rating Curve= 0 ,0
Exp/Cntr=0.3,0.1

Type RM Length L Ch R = 1 ,21854.16,92.12,91.44,88.74
XS GIS Cut Line= 6
     643841.7573    4321058.8945     643690.3188    4321216.0747
     643681.3862    4321217.5232     643677.6157    4321223.4641
     643667.8261    4321228.2266     643495.3671    4321378.1399
#Sta/Elev= 30
       0 1133.87   21.28 1128.31   27.36 1127.92   72.96 1121.45   79.04 1121.11
  118.57 1116.52  148.97 1114.26  176.33  1112.8  203.69 1110.56  209.77 1109.46
  218.27  1106.6  224.31 1105.51  237.08 1106.07   287.9 1106.18     294 1107.48
  300.09 1107.36  303.14 1107.78  309.23 1110.03  312.28  1110.7  367.12 1112.49
  373.21 1114.45  382.35 1118.49  388.45 1121.69  394.54 1123.64  400.63 1124.68
  406.73 1124.87  415.87 1127.31  428.05 1129.19  455.47 1131.48  473.76 1134.03
#Mann= 3 , 0 , 0
       0      .1       0  218.27      .1       0   287.9      .1       0
Bank Sta=218.27,287.9
XS Rating Curve= 0 ,0
Exp/Cntr=0.3,0.1

Type RM Length L Ch R = 1 ,21762.72,102.43,91.44,64.03
XS GIS Cut Line= 5
     643705.9759    4321056.4059     643624.3037    4321158.2075
     643608.3049    4321166.7586     643593.9807    4321180.1325
     643477.3754    4321366.4982
#Sta/Elev= 30
       0 1134.48   12.14 1132.73   15.18 1132.73   24.28  1130.9   36.42 1127.38
   54.63 1121.21    60.7 1120.56   72.85 1117.04   84.99 1114.62   91.06 1112.14
  109.27 1106.09  115.34 1105.39  124.24 1104.97  136.56    1104  148.65 1105.11
  162.65 1105.16  171.31 1104.25  177.41 1105.04  238.48 1105.58   256.8 1106.34
  269.01 1110.08  275.12 1110.97  281.22 1111.33  287.33  1112.6   308.7 1120.81
  314.81 1122.49  320.92 1123.14  336.18 1126.08  351.45 1129.67  388.09 1134.14
#Mann= 3 , 0 , 0
       0      .1       0  124.24      .1       0  177.41      .1       0
Bank Sta=124.24,177.41
XS Rating Curve= 0 ,0
Exp/Cntr=0.3,0.1

Type RM Length L Ch R = 1 ,21671.28,84.1,91.44,96.56
XS GIS Cut Line= 6
     643576.5944    4321043.7059     643536.9068    4321073.8685
      643547.743     4321106.905     643554.4143    4321124.8314
     643557.5067    4321143.0273     643488.4879    4321308.8189
#Sta/Elev= 30
       0 1124.88   29.32 1124.15   35.19 1123.64   38.12 1122.96   49.85 1119.86
   67.23 1112.21   70.13  1112.2   78.82 1106.63   81.72 1105.09   85.28 1103.87
   92.87 1102.52   98.32  1102.6  106.41 1103.62   140.5 1104.25  158.76 1104.01
  173.98 1102.91  177.02 1102.99  183.11 1103.88   189.2 1104.65  201.37 1105.27
  216.59 1108.56  225.72 1109.08  243.98  1109.3   259.2 1111.18  262.25 1111.78
  268.33 1113.83  271.38 1113.89  292.69 1122.63  298.77 1124.86  301.82 1125.66
#Mann= 3 , 0 , 0
       0      .1       0   85.28      .1       0  183.11      .1       0
Bank Sta=85.28,183.11
XS Rating Curve= 0 ,0
Exp/Cntr=0.3,0.1

Type RM Length L Ch R = 1 ,21579.84,92.73,91.44,92.37
XS GIS Cut Line= 6
     643581.3569    4321036.5622     643521.1503    4321062.3309
     643467.1127    4321102.9181     643462.8945    4321124.0202
     643461.7466    4321134.3291     643438.0847    4321285.4826
#Sta/Elev= 30
       0 1124.99   14.88 1124.21   26.79 1122.64   44.65 1121.63   56.56 1119.37
   68.56 1117.99   74.71 1116.71  105.42 1112.07  111.57  1110.4  123.86    1106
     130 1104.89  136.15 1104.39  145.37 1102.36  151.52 1101.73  159.78 1100.97
  189.44  1101.2   192.5 1101.79  195.56 1102.71  201.68 1103.33  220.04 1104.57
  226.16 1106.46  229.22 1106.52  235.34 1108.29  259.82 1109.22  278.18 1111.22
  281.24 1111.85  287.36 1114.53  293.48 1116.15  308.78  1123.2  317.96 1126.34
#Mann= 3 , 0 , 0
       0      .1       0  151.52      .1       0   192.5      .1       0
Bank Sta=151.52,192.5
XS Rating Curve= 0 ,0
Exp/Cntr=0.3,0.1

Type RM Length L Ch R = 1 ,21488.4 ,38.96,91.44,100.54
XS GIS Cut Line= 6
     643579.3725    4321031.4821     643458.2161    4321071.1901
     643381.1741    4321071.6534     643375.4144    4321094.2192
     643372.2188    4321115.9821      643338.072    4321202.9325
#Sta/Elev= 30
       0 1125.16    6.07 1124.66   15.18  1123.3   21.25 1122.03   60.71 1117.63
   66.78 1115.91   81.96 1114.08   91.07 1112.19  106.25 1110.24  112.32 1108.52
   127.5 1104.95  130.46    1104  133.42 1102.54  136.39 1101.75  142.31 1100.83
   151.2 1100.53  204.54    1100   230.9 1100.36  242.17 1099.47  264.94 1100.35
  273.98  1100.8  276.99 1101.39  283.02 1104.78  286.03 1106.16  289.04  1106.9
  292.06 1108.14  313.15 1111.59  316.16 1112.26  325.21  1115.2  343.29 1126.33
#Mann= 3 , 0 , 0
       0      .1       0   151.2      .1       0  264.94      .1       0
Bank Sta=151.2,264.94
XS Rating Curve= 0 ,0
Exp/Cntr=0.3,0.1