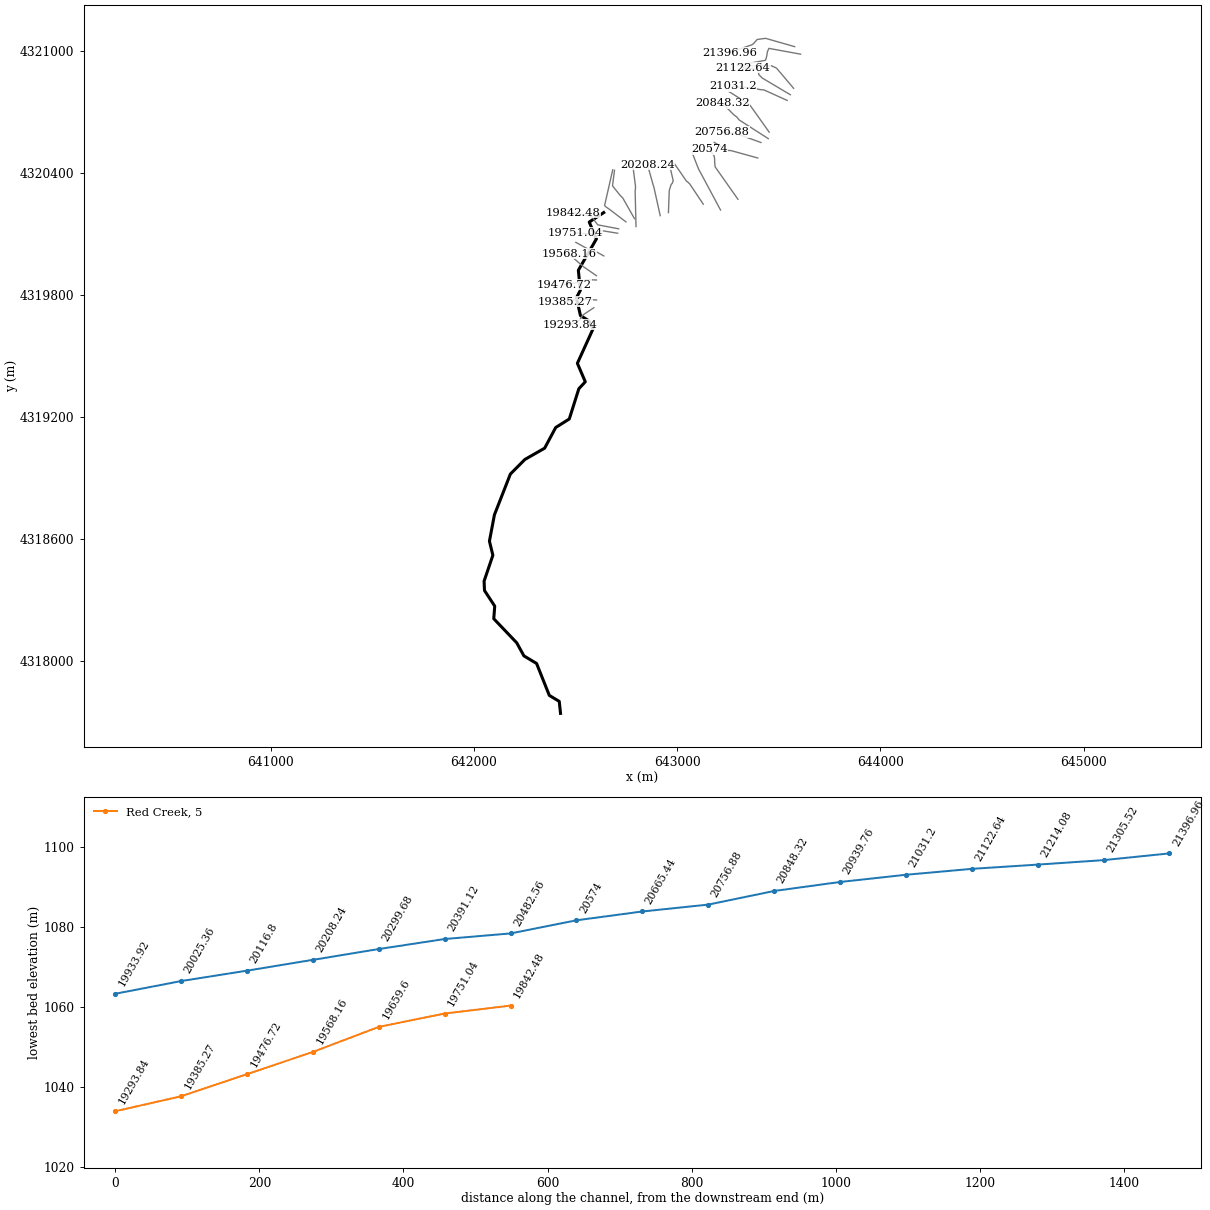
HEC-RAS study RedCreek.prj: RedCreek

--- RedCreek.g01 (geometry) --- (continued)

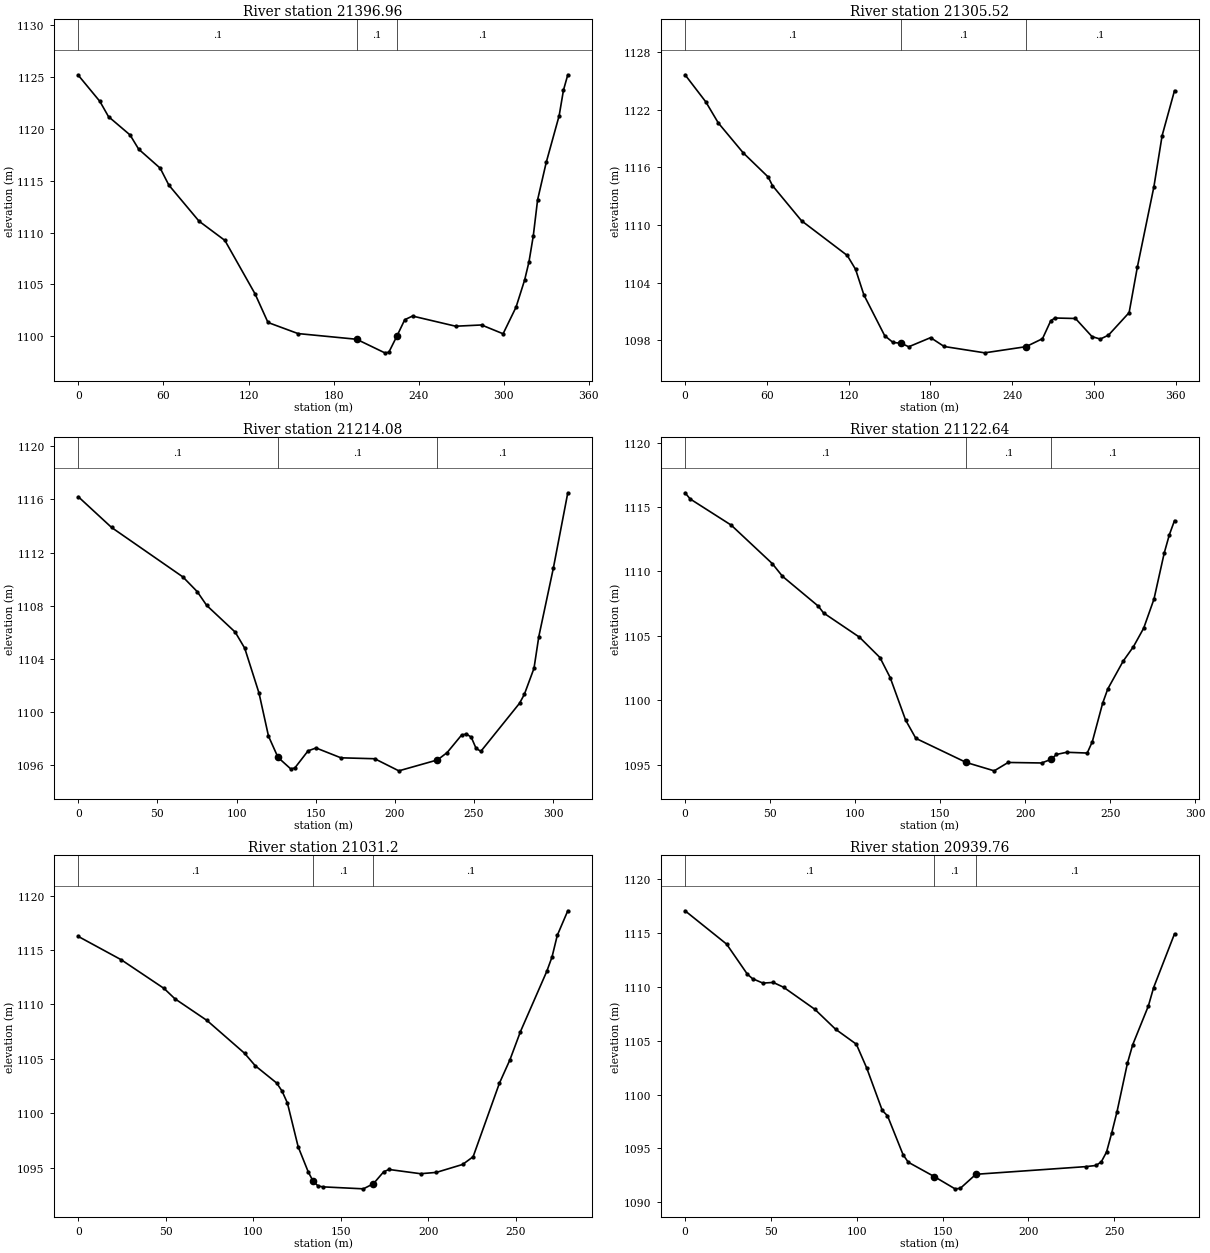
Type RM Length L Ch R = 1 ,21396.96,77.4,91.44,107.94
XS GIS Cut Line= 6
      643578.248    4321023.4344      643435.032    4321064.3302
     643393.7569    4321058.7739     643374.9117    4321037.6183
     643367.6816     4321032.583     643256.7786    4320994.3302
#Sta/Elev= 30
       0 1125.18    15.2 1122.66   21.28 1121.19   36.48 1119.42   42.55 1118.05
   57.75 1116.21   63.83 1114.58   85.11  1111.1  103.35 1109.24  124.62 1104.08
  133.74 1101.32  154.89 1100.25  196.25  1099.7  216.09 1098.39  218.92 1098.44
  224.79 1100.05  230.17 1101.59  235.66 1101.94  266.06 1100.96  284.31 1101.08
  299.51 1100.23  308.64  1102.8  314.72 1105.43  317.76 1107.17   320.8 1109.68
  323.84 1113.16  329.92 1116.77  339.05 1121.29  342.09 1123.75  345.13 1125.23
#Mann= 3 , 0 , 0
       0      .1       0  196.25      .1       0  224.79      .1       0
Bank Sta=196.25,224.79
XS Rating Curve= 0 ,0
Exp/Cntr=0.3,0.1

Type RM Length L Ch R = 1 ,21305.52,114.6,91.44,59.87
XS GIS Cut Line= 6
     643607.3522    4320986.3926      643451.284     4321014.853
     643443.7408    4320997.4138     643440.8454    4320977.0542
     643434.6152      4320956.38     643297.7891      4320930.83
#Sta/Elev= 30
       0 1125.61   15.25 1122.79   24.41  1120.6   42.71 1117.49   61.02 1114.98
   64.07  1114.1   85.42 1110.44  118.98 1106.83  125.08 1105.39  131.18 1102.73
  146.44 1098.49  152.54 1097.79  158.64  1097.7  164.07 1097.34  180.12 1098.29
  190.04 1097.37  219.81 1096.71  250.07 1097.35  262.18 1098.18  268.23 1100.04
  271.25 1100.33  286.38 1100.28  298.49  1098.4  304.54 1098.14  310.59 1098.55
  325.72 1100.89  331.77 1105.63  343.88 1113.96  349.93 1119.29  359.01 1123.96
#Mann= 3 , 0 , 0
       0      .1       0  158.64      .1       0  250.07      .1       0
Bank Sta=158.64,250.07
XS Rating Curve= 0 ,0
Exp/Cntr=0.3,0.1

Type RM Length L Ch R = 1 ,21214.08,90.57,91.44,74.32
XS GIS Cut Line= 6
     643572.9563    4320818.3819     643489.4496    4320916.9806
     643482.9181    4320920.9462     643468.1711    4320926.9191
     643464.8902    4320929.2474     643312.3412    4320928.1842
#Sta/Elev= 30
       0  1116.2   21.03 1113.89   66.11 1110.17   75.12 1109.07   81.13 1108.03
   99.16 1106.02  105.17 1104.81  114.19 1101.44  120.19  1098.2   126.2  1096.6
   134.3 1095.73  136.85 1095.81  145.18 1097.09  150.24 1097.31  165.95 1096.57
  187.31  1096.5  202.56 1095.59  226.97 1096.41  233.07 1096.96  242.22 1098.28
  245.28 1098.36  248.33 1098.12  251.38 1097.28  254.43 1097.06  278.84 1100.67
  281.89 1101.34  287.99  1103.3  291.04 1105.69   300.2 1110.82  309.35  1116.5
#Mann= 3 , 0 , 0
       0      .1       0   126.2      .1       0  226.97      .1       0
Bank Sta=126.2,226.97
XS Rating Curve= 0 ,0
Exp/Cntr=0.3,0.1

Type RM Length L Ch R = 1 ,21122.64,66.71,91.44,105.37
XS GIS Cut Line= 6
     643557.0813    4320786.6318     643419.6199    4320868.2873
     643401.7241    4320885.3249     643399.2264    4320902.3983
       643397.28    4320912.7426     643322.0352    4320918.9737
#Sta/Elev= 30
       0  1116.1    3.02 1115.62   27.15 1113.59   51.28 1110.61   57.32 1109.62
   78.43  1107.3   81.45 1106.78  102.57  1104.9  114.63 1103.32  120.67 1101.76
  129.72 1098.47  135.75 1097.05  165.38 1095.18  181.85 1094.53  190.04 1095.18
  209.76 1095.14  215.41 1095.43  218.43  1095.8  224.47 1095.97  236.55 1095.91
  239.57  1096.8  245.61 1099.77  248.63 1100.88  257.69 1103.04  263.73 1104.16
  269.77  1105.6  275.81 1107.85  281.85 1111.43  284.87 1112.85  287.89 1113.94
#Mann= 3 , 0 , 0
       0      .1       0  165.38      .1       0  215.41      .1       0
Bank Sta=165.38,215.41
XS Rating Curve= 0 ,0
Exp/Cntr=0.3,0.1

Type RM Length L Ch R = 1 ,21031.2 ,107.94,91.44,83.75
XS GIS Cut Line= 6
     643541.2063    4320758.8505     643426.7152    4320810.5551
      643403.792    4320812.5106     643387.2249    4320816.8158
     643381.9564    4320819.1541     643274.0926    4320827.7981
#Sta/Elev= 30
       0 1116.24   24.51  1114.1   49.02 1111.46   55.15 1110.52   73.54 1108.52
   94.98 1105.51  101.11 1104.36  113.37 1102.77  116.43 1102.03   119.5 1100.93
  125.62 1096.92  131.38 1094.61  134.25 1093.73  137.13  1093.3     140 1093.23
   162.9 1093.05  168.63 1093.52  174.52 1094.62  177.52 1094.83  195.56 1094.44
  204.58 1094.56  219.61 1095.29  225.62    1096  240.65 1102.76  246.66 1104.91
  252.67  1107.5   267.7 1113.03   270.7 1114.35  273.71 1116.34  279.72  1118.6
#Mann= 3 , 0 , 0
       0      .1       0  134.25      .1       0  168.63      .1       0
Bank Sta=134.25,168.63
XS Rating Curve= 0 ,0
Exp/Cntr=0.3,0.1

Type RM Length L Ch R = 1 ,20939.76,87.92,91.44,90.58
XS GIS Cut Line= 4
     643452.5707     4320602.746     643363.3318     4320728.482
     643353.4332    4320740.0303     643255.6071     4320801.764
#Sta/Elev= 30
       0 1117.05   24.19 1113.96   36.28 1111.17    39.3 1110.75   45.35 1110.34
    51.4  1110.4   57.44 1109.95   75.58 1107.91   87.67 1106.06   99.77 1104.67
  105.81 1102.46  114.88 1098.52  117.91 1098.03  126.98 1094.42     130 1093.72
  145.12 1092.39  157.23 1091.25  160.27 1091.29   169.4  1092.6  233.32 1093.31
  239.41 1093.42  242.45 1093.76   245.5 1094.67  248.54 1096.46  251.59 1098.41
  257.67 1102.92  260.72 1104.62  269.85 1108.22   272.9 1109.92  285.07 1114.91
#Mann= 3 , 0 , 0
       0      .1       0  145.12      .1       0   169.4      .1       0
Bank Sta=145.12,169.4
XS Rating Curve= 0 ,0
Exp/Cntr=0.3,0.1

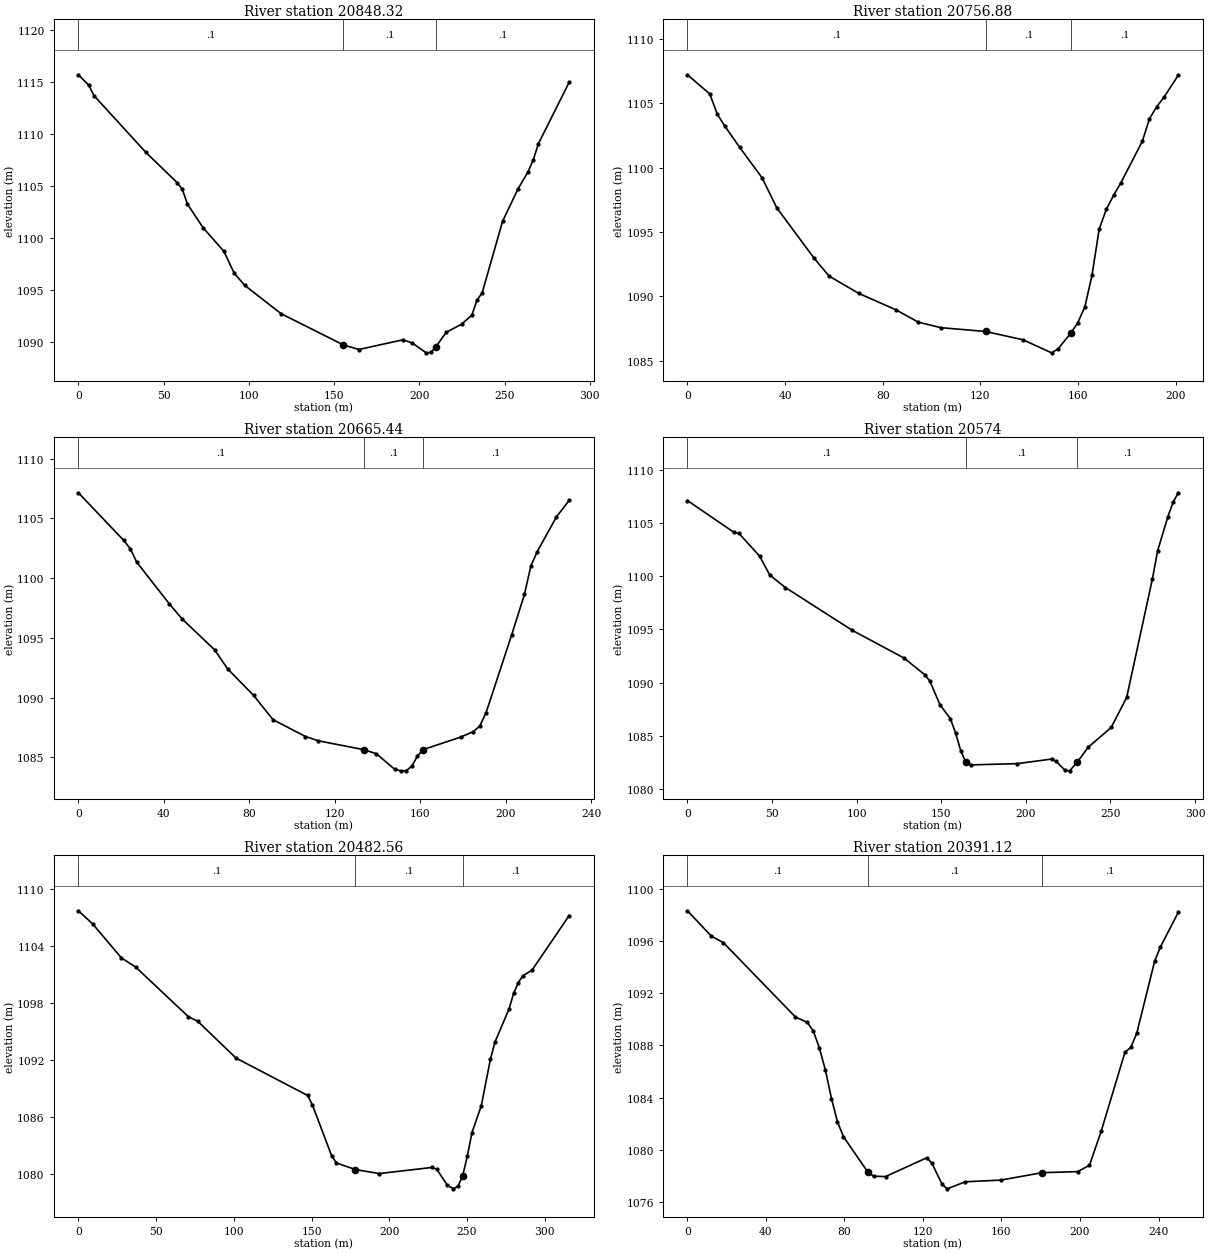
Type RM Length L Ch R = 1 ,20848.32,80.27,91.44,98.24
XS GIS Cut Line= 5
     643448.2491    4320570.6432      643304.645    4320662.8313
     643294.3575    4320676.2759     643278.9842    4320687.7074
     643221.8373    4320745.3053
#Sta/Elev= 30
       0 1115.67    6.09 1114.67    9.14 1113.67   39.61 1108.22    57.9 1105.33
   60.95 1104.69   63.99 1103.26   73.13    1101   85.32 1098.74   91.42 1096.63
   97.51 1095.48  118.84 1092.76  155.41 1089.76  164.55 1089.32  190.31 1090.25
  195.79 1089.95     204    1089  206.73 1089.04  209.74  1089.6  215.75 1090.97
  224.77 1091.75  230.78 1092.61  233.78 1094.06  236.79 1094.74  248.81 1101.62
  257.82 1104.72  263.83 1106.39  266.84 1107.54  269.84 1109.07  287.87 1114.96
#Mann= 3 , 0 , 0
       0      .1       0  155.41      .1       0  209.74      .1       0
Bank Sta=155.41,209.74
XS Rating Curve= 0 ,0
Exp/Cntr=0.3,0.1

Type RM Length L Ch R = 1 ,20756.88,87.65,91.44,90.09
XS GIS Cut Line= 6
     643412.2657    4320551.5932     643282.9728    4320598.2248
     643278.1457    4320599.5824     643274.2179    4320598.4052
     643260.9887    4320596.8177     643220.2521    4320603.1193
#Sta/Elev= 30
       0 1107.23    9.16 1105.74   12.22 1104.17   15.27 1103.25   21.38 1101.59
   30.54 1099.23   36.65 1096.87   51.92 1092.96   58.03 1091.57   70.25 1090.22
   85.52 1088.94   94.68 1087.98  103.85 1087.56  122.17 1087.26  137.45 1086.62
  149.22  1085.6  151.89 1085.91  157.22 1087.17  159.88 1087.92  162.83 1089.16
  165.77 1091.62  168.72 1095.23  171.66 1096.77  174.61 1097.85  177.55 1098.81
  186.38 1102.05  189.33 1103.81  192.27 1104.74  195.22 1105.47  201.11 1107.19
#Mann= 3 , 0 , 0
       0      .1       0  122.17      .1       0  157.22      .1       0
Bank Sta=122.17,157.22
XS Rating Curve= 0 ,0
Exp/Cntr=0.3,0.1

Type RM Length L Ch R = 1 ,20665.44,115.57,91.44,73.32
XS GIS Cut Line= 5
     643396.3907     4320475.393     643264.7359    4320511.8598
     643250.6006    4320512.4152     643238.3844    4320517.0996
     643182.6869    4320552.1555
#Sta/Elev= 30
       0 1107.14   21.25 1103.15   24.29 1102.46   27.32 1101.33    42.5 1097.86
   48.57 1096.58   63.75    1094   69.82 1092.41   81.97 1090.19   91.07 1088.16
  106.25 1086.75  112.33 1086.39  133.58 1085.65  139.44 1085.31  147.93 1084.02
  150.76 1083.88  153.37 1083.89  155.99 1084.27  158.61  1085.1  161.22 1085.65
   178.8  1086.7  184.78 1087.16  187.77 1087.62  190.76 1088.75  202.73 1095.25
  208.71 1098.64   211.7 1101.01   214.7 1102.22  223.67 1105.12  229.65 1106.51
#Mann= 3 , 0 , 0
       0      .1       0  133.58      .1       0  161.22      .1       0
Bank Sta=133.58,161.22
XS Rating Curve= 0 ,0
Exp/Cntr=0.3,0.1

Type RM Length L Ch R = 1 ,20574   ,81.31,91.44,98.42
XS GIS Cut Line= 6
     643299.0238    4320272.1926     643186.7365    4320431.6446
     643184.4789    4320451.7578     643184.2633    4320470.5579
     643181.4449     4320486.678     643158.9183    4320519.2366
#Sta/Elev= 30
       0 1107.15   27.42 1104.16   30.47 1104.05   42.66 1101.91   48.76 1100.11
    57.9 1098.95   97.51 1094.91  127.98 1092.31  140.17 1090.75  143.22 1090.15
  149.31 1087.88  155.41  1086.6  158.46 1085.24   161.5 1083.59  164.55 1082.47
   167.6 1082.24  195.02 1082.36  215.26 1082.79   217.9 1082.58  223.19 1081.72
  225.84 1081.68  230.37  1082.5  236.81  1083.9  250.44 1085.77  259.58  1088.6
  274.81 1099.79  277.85 1102.41  283.95 1105.64  286.99 1106.98  290.04 1107.88
#Mann= 3 , 0 , 0
       0      .1       0  164.55      .1       0  230.37      .1       0
Bank Sta=164.55,230.37
XS Rating Curve= 0 ,0
Exp/Cntr=0.3,0.1

Type RM Length L Ch R = 1 ,20482.56,84.34,91.44,94.9
XS GIS Cut Line= 5
     643213.2987    4320219.2758     643104.5799     4320422.437
      643102.349    4320429.0157     643100.5292    4320432.4369
     643073.5984    4320501.8514
#Sta/Elev= 30
       0 1107.68    9.22 1106.29   27.65 1102.72   36.87 1101.75   70.66 1096.54
   76.81 1096.04  101.39 1092.17  147.47 1088.23  150.54 1087.23  162.83 1081.91
   165.9 1081.13  178.19 1080.43  193.55 1080.01  227.35 1080.65  230.42 1080.47
  237.37 1078.78  241.24  1078.4  244.22 1078.68   247.2 1079.79  250.18 1081.85
  253.16 1084.33  259.11 1087.12  265.07 1092.09  268.05  1093.9  276.98 1097.33
  279.96 1098.98  282.94 1100.12  285.92 1100.83  291.87 1101.45   315.7 1107.18
#Mann= 3 , 0 , 0
       0      .1       0  178.19      .1       0   247.2      .1       0
Bank Sta=178.19,247.2
XS Rating Curve= 0 ,0
Exp/Cntr=0.3,0.1

Type RM Length L Ch R = 1 ,20391.12,106.6,91.44,68.8
XS GIS Cut Line= 5
     643128.3231    4320247.9611     643062.0696     4320347.136
     643050.7554    4320358.0233     643045.3537    4320361.7519
     642983.8604    4320451.1615
#Sta/Elev= 30
       0 1098.33   12.23 1096.38   18.35 1095.88   55.05 1090.18   61.16 1089.76
   64.22 1089.08   67.28 1087.78   70.34 1086.08    73.4 1083.92   76.45 1082.13
   79.51    1081   91.75 1078.32    94.8 1077.97  100.92 1077.94  121.89 1079.38
   124.5 1078.98  129.74 1077.35  132.35    1077  141.53 1077.54  159.62 1077.67
  180.72 1078.24  198.81 1078.32  204.84 1078.81  210.86 1081.45  222.92 1087.48
  225.94 1087.86  228.95 1088.95  237.99 1094.44  241.01 1095.57  250.05  1098.2
#Mann= 3 , 0 , 0
       0      .1       0   91.75      .1       0  180.72      .1       0
Bank Sta=91.75,180.72
XS Rating Curve= 0 ,0
Exp/Cntr=0.3,0.1

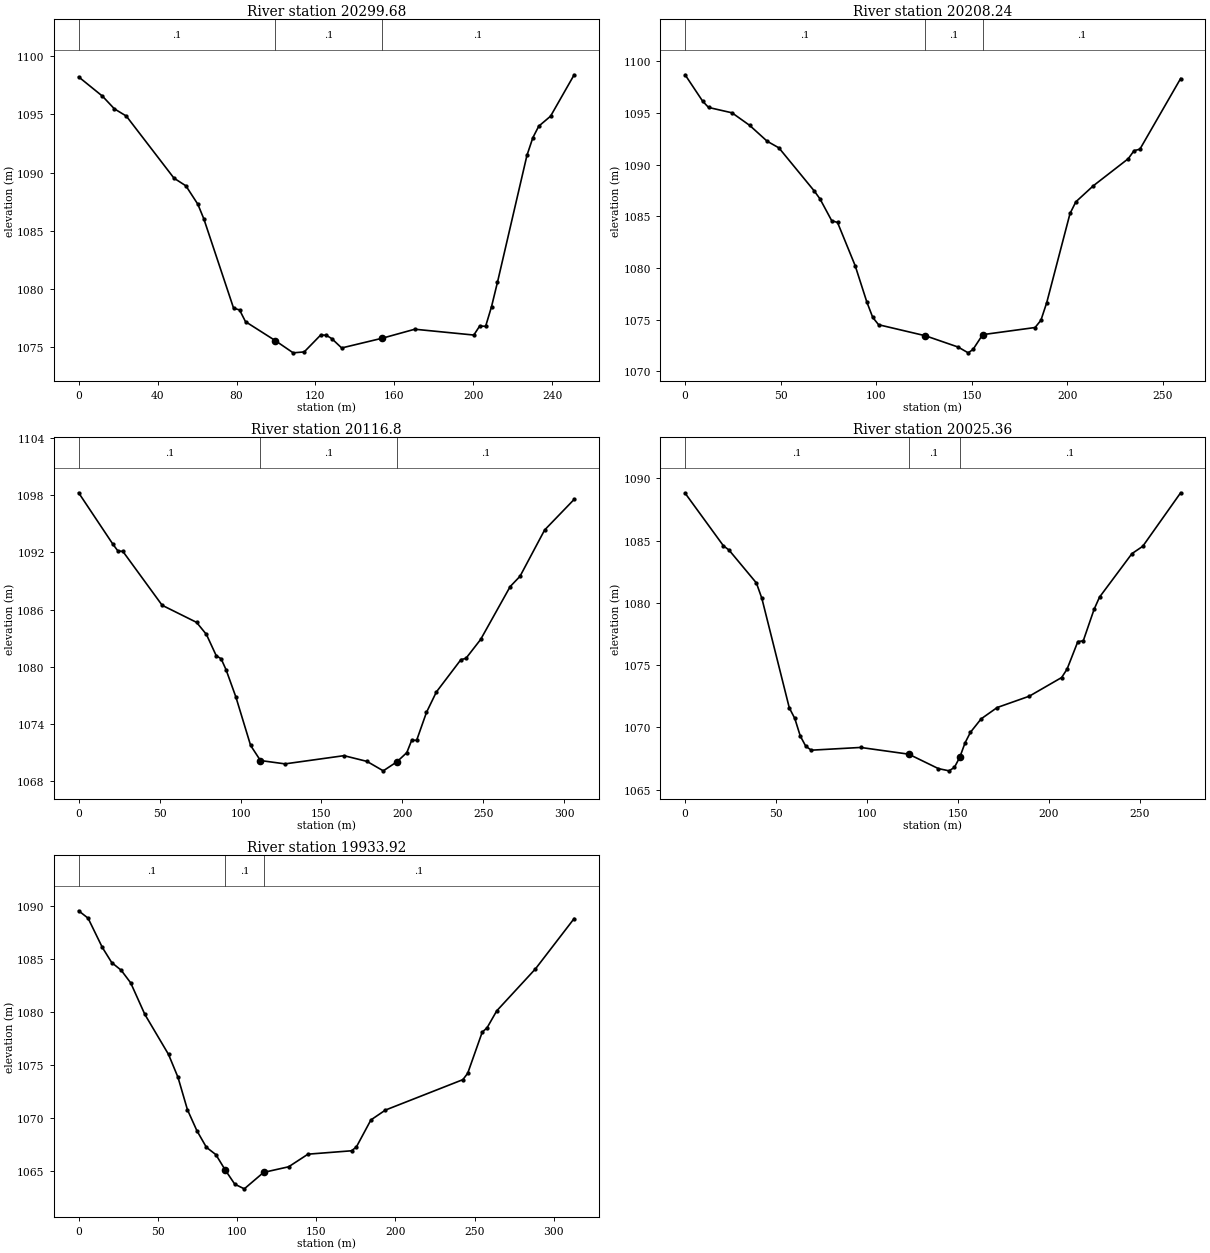
Type RM Length L Ch R = 1 ,20299.68,81.41,91.44,98.07
XS GIS Cut Line= 6
     642956.8728     4320206.686     642960.8804     4320315.327
     642969.6508    4320343.5737     642976.0504    4320352.0717
     642980.3273    4320363.7459     642960.0478    4320451.1615
#Sta/Elev= 30
       0 1098.23   12.08 1096.57   18.12 1095.48   24.16 1094.86   48.32 1089.52
   54.36 1088.86    60.4 1087.28   63.42 1086.03   78.52 1078.34   81.54 1078.19
   84.56 1077.18   99.66 1075.55  108.71  1074.5  114.31 1074.58   122.7 1076.04
   125.5 1076.01  128.29 1075.72  133.29 1074.92  153.91 1075.76  170.34 1076.53
  200.25 1076.03  203.24 1076.81  206.23 1076.78  209.22 1078.47  212.22 1080.56
  227.17 1091.48  230.16    1093  233.15 1093.99  239.14 1094.85   251.1 1098.41
#Mann= 3 , 0 , 0
       0      .1       0   99.66      .1       0  153.91      .1       0
Bank Sta=99.66,153.91
XS Rating Curve= 0 ,0
Exp/Cntr=0.3,0.1

Type RM Length L Ch R = 1 ,20208.24,94.43,91.44,87.69
XS GIS Cut Line= 5
     642916.3915    4320191.6048     642885.8118    4320329.4557
     642884.6763    4320333.7811     642881.4492    4320343.3776
     642853.5276      4320443.18
#Sta/Elev= 30
       0  1098.7    9.21 1096.14   12.28 1095.54   24.56 1095.02   33.77 1093.81
   42.97 1092.27   49.11 1091.63   67.53 1087.48    70.6  1086.7   76.74 1084.59
   79.81 1084.41   89.02 1080.24   95.16 1076.71   98.23 1075.23   101.3 1074.52
  125.85 1073.45  142.93 1072.36  148.21  1071.8  150.74 1072.13   155.8 1073.56
  183.23 1074.25  186.28 1074.95  189.33 1076.66  201.52 1085.28  204.57 1086.41
  213.71 1087.96     232 1090.58  235.05 1091.36   238.1  1091.5  259.43 1098.34
#Mann= 3 , 0 , 0
       0      .1       0  125.85      .1       0   155.8      .1       0
Bank Sta=125.85,155.8
XS Rating Curve= 0 ,0
Exp/Cntr=0.3,0.1

Type RM Length L Ch R = 1 ,20116.8 ,81.84,91.44,94.9
XS GIS Cut Line= 6
     642797.3287    4320137.6297     642792.9887    4320313.6271
     642793.8772     4320317.652     642794.4137     4320328.313
     642795.0515     4320334.071     642781.0568    4320442.6287
#Sta/Elev= 30
       0 1098.24   21.25 1092.83   24.28 1092.14   27.32  1092.1    51.6 1086.45
   72.85 1084.66   78.92  1083.4   84.99 1081.17   88.03 1080.84   91.06  1079.7
   97.13 1076.84  106.24 1071.76  112.31 1070.18  127.49 1069.83  163.91 1070.69
  178.11 1070.09  188.18  1069.1  196.64 1070.05  202.72 1071.01  205.76 1072.31
   208.8  1072.3  214.88 1075.23  220.96 1077.36  236.17 1080.76  239.21 1080.88
  248.33 1082.87  266.57 1088.41  272.65 1089.49  287.85 1094.34   306.1 1097.55
#Mann= 3 , 0 , 0
       0      .1       0  112.31      .1       0  196.64      .1       0
Bank Sta=112.31,196.64
XS Rating Curve= 0 ,0
Exp/Cntr=0.3,0.1

Type RM Length L Ch R = 1 ,20025.36,88.33,91.44,94.28
XS GIS Cut Line= 5
     642789.7881    4320176.7219     642731.8134    4320279.1002
     642718.5039    4320292.2647     642681.6167    4320338.0944
     642691.3629    4320414.8474
#Sta/Elev= 30
       0 1088.82   21.12 1084.58   24.13 1084.25   39.22  1081.6   42.23 1080.36
   57.32 1071.56   60.34 1070.71   63.35  1069.3   66.37 1068.48   69.39 1068.16
   96.54 1068.38     123 1067.84  139.32 1066.68   145.2  1066.5  148.14 1066.78
  151.08 1067.59  154.02 1068.76  156.96  1069.6  162.85 1070.68  171.67 1071.59
  189.32  1072.5  207.11    1074  210.08 1074.67  216.03 1076.89  219.01 1076.95
  224.96 1079.48  227.94 1080.46  245.79 1083.96  251.74 1084.55  272.57 1088.85
#Mann= 3 , 0 , 0
       0      .1       0     123      .1       0  151.08      .1       0
Bank Sta=123,151.08
XS Rating Curve= 0 ,0
Exp/Cntr=0.3,0.1

Type RM Length L Ch R = 1 ,19933.92,94.97,91.44,53.35
XS GIS Cut Line= 5
     642747.7193    4320160.8469     642667.0426    4320222.5277
     642649.5029    4320234.5863     642642.6222    4320241.4631
     642682.6316    4320417.2287
#Sta/Elev= 30
       0 1089.56    5.97 1088.86   14.93 1086.11   20.91 1084.67   26.88 1083.95
   32.86 1082.76   41.82 1079.78   56.75 1076.01   62.72 1073.85    68.7 1070.79
   74.67 1068.81   80.65 1067.25   86.62 1066.56   92.59  1065.1   98.57 1063.77
  104.59 1063.33  116.76 1064.88  132.57 1065.41  144.79  1066.6  172.29 1066.92
  175.34 1067.28  184.51 1069.83  193.67 1070.76  242.56 1073.63  245.61 1074.23
  254.78 1078.11  257.83 1078.52  263.94 1080.12  288.39 1084.08  312.83 1088.83
#Mann= 3 , 0 , 0
       0      .1       0   92.59      .1       0  116.76      .1       0
Bank Sta=92.59,116.76
XS Rating Curve= 0 ,0
Exp/Cntr=0.3,0.1

River Reach=Red Creek       ,5
Reach XY= 30
     642638.3306    4320206.7709     642567.0606    4320160.0422
     642602.4282    4320077.1595     642513.4823    4319922.7105
     642523.3799    4319824.1413     642503.9573    4319787.3758
     642523.8011    4319700.0631     642564.6793    4319674.2662
     642585.3168     4319633.388     642508.7116    4319464.8905
      642547.589    4319373.9379     642515.8636    4319339.6999
     642468.9034    4319190.9868     642401.9602    4319148.8027
     642347.5882    4319047.2025     642250.3537    4318991.6398
      642178.916    4318919.8053     642100.3346    4318718.9862
     642075.8258    4318589.5663      642092.794    4318520.1514
     642049.5345    4318392.7543     642051.5189    4318346.7167
     642101.9221    4318269.7228     642097.1596    4318207.8101
     642210.2692    4318089.1443     642245.5912    4318024.8504
     642307.9007    4317987.5441      642370.607    4317830.3813
     642419.4228    4317801.0125     642425.7667    4317741.9269

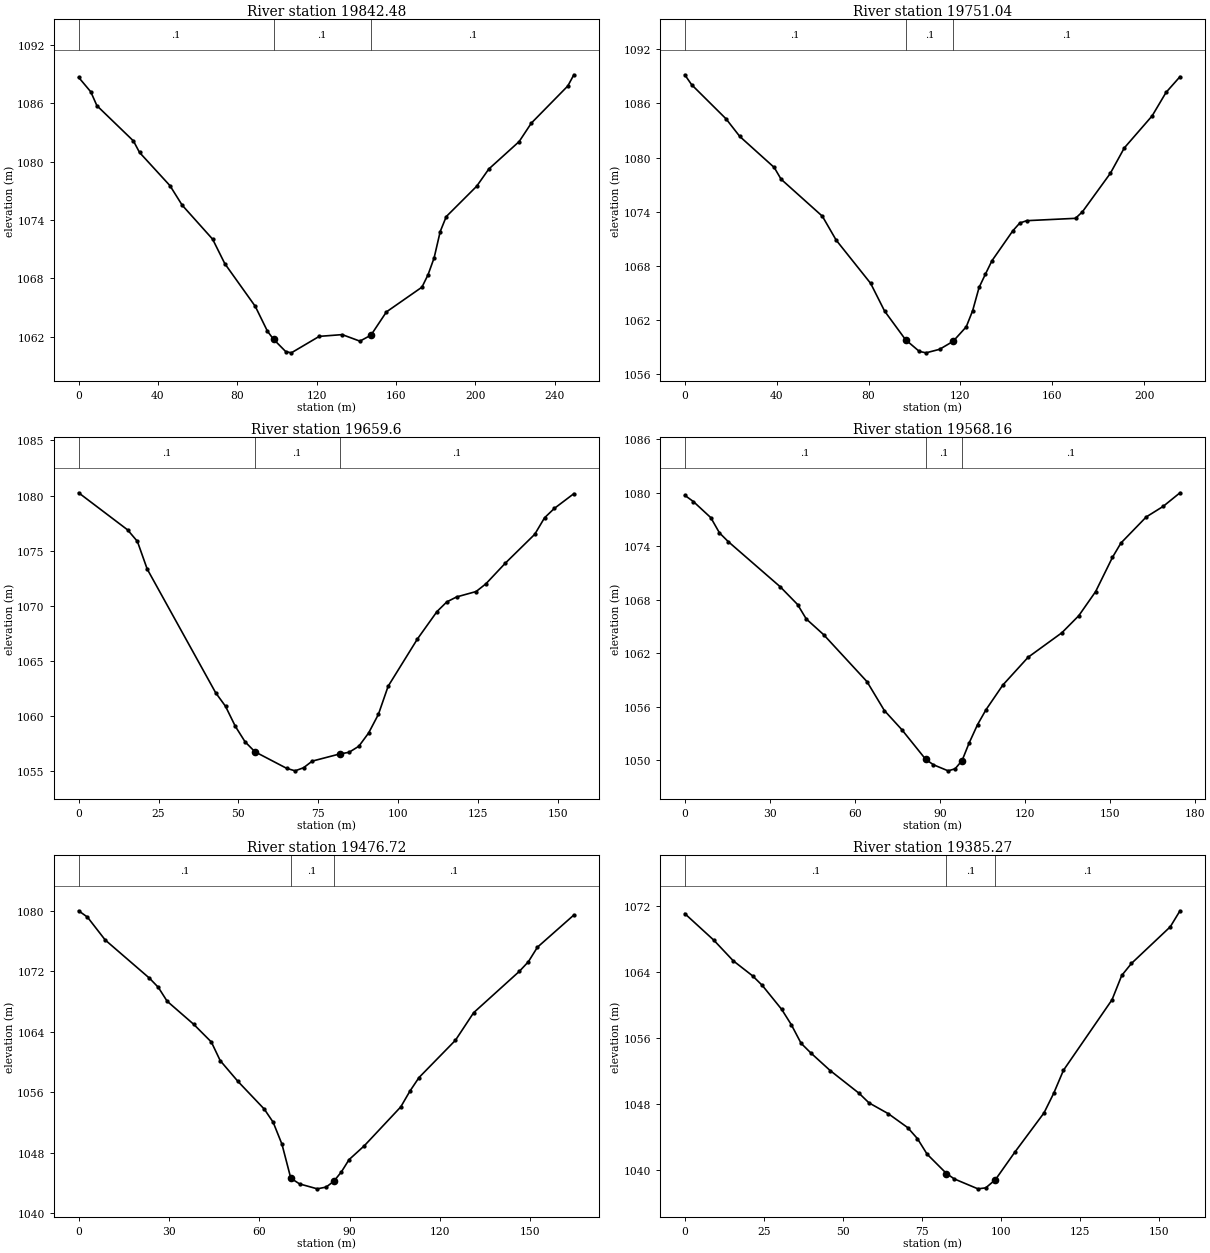
Type RM Length L Ch R = 1 ,19842.48,55.17,91.44,92.78
XS GIS Cut Line= 6
     642711.7513     4320126.828     642609.1426    4320146.3571
     642595.3339     4320164.162     642585.7802     4320179.225
     642576.9957    4320188.8229      642486.855    4320206.8646
#Sta/Elev= 30
       0 1088.64    6.14 1087.15    9.22 1085.73   27.65 1082.11   30.72 1080.93
   46.08 1077.52   52.23 1075.52   67.59 1072.03   73.73 1069.52   89.09 1065.14
   95.23 1062.59   98.31 1061.76  104.45  1060.5  107.27 1060.37  121.35 1062.06
  132.93 1062.24  141.85 1061.57  147.42 1062.18  155.23 1064.57  173.15 1067.11
  176.22 1068.38  179.28 1070.11  182.35 1072.81  185.41 1074.35  200.73 1077.46
  206.86 1079.23  222.18 1082.05  228.31 1083.94   246.7 1087.75  249.76  1088.9
#Mann= 3 , 0 , 0
       0      .1       0   98.31      .1       0  147.42      .1       0
Bank Sta=98.31,147.42
XS Rating Curve= 0 ,0
Exp/Cntr=0.3,0.1

Type RM Length L Ch R = 1 ,19751.04,99.01,91.44,82.48
XS GIS Cut Line= 6
     642707.1211    4320104.9999     642630.2527    4320117.6022
     642609.3841    4320113.4347     642590.3905    4320105.5206
     642577.1242    4320101.1212      642495.454    4320106.9842
#Sta/Elev= 30
       0 1089.17       3 1088.07   17.98 1084.29   23.97 1082.34   38.95 1078.91
   41.94 1077.61   59.92 1073.51   65.91 1070.87   80.93 1066.08   87.01 1063.01
   96.14 1059.84  102.11 1058.55  105.05 1058.39  110.93 1058.78  116.81 1059.66
  122.55 1061.27  125.34 1063.06  128.14 1065.63  130.93 1067.12  133.73 1068.58
  142.83  1071.9  145.86 1072.76  148.89 1073.02  170.12 1073.28  173.15 1074.01
  185.28 1078.26  191.35 1081.07  203.48 1084.62  209.54 1087.22  215.61 1088.96
#Mann= 3 , 0 , 0
       0      .1       0   96.14      .1       0  116.81      .1       0
Bank Sta=96.14,116.81
XS Rating Curve= 0 ,0
Exp/Cntr=0.3,0.1

Type RM Length L Ch R = 1 ,19659.6 ,96.79,91.44,86.6
XS GIS Cut Line= 6
     642638.8584    4319993.3455     642587.8171    4320021.3324
     642576.8056    4320026.3046     642571.5452    4320024.9308
      642562.814    4320026.1214     642501.2748    4320060.1529
#Sta/Elev= 30
       0 1080.25   15.32 1076.89   18.38 1075.85   21.45 1073.34   42.89 1062.12
   45.96  1060.9   49.02 1059.09   52.08 1057.68   55.15 1056.78   65.07 1055.28
   67.72 1055.05   70.37 1055.33   73.08 1055.93   81.68 1056.58   84.61 1056.73
   87.67 1057.28   90.73 1058.48   93.79 1060.17   96.84 1062.72  106.02 1067.01
  112.13 1069.49  115.19 1070.36  118.25 1070.81  124.36  1071.3  127.42    1072
  133.53 1073.88  142.71 1076.49  145.76 1077.98  148.82 1078.83  154.94 1080.17
#Mann= 3 , 0 , 0
       0      .1       0   55.15      .1       0   81.68      .1       0
Bank Sta=55.15,81.68
XS Rating Curve= 0 ,0
Exp/Cntr=0.3,0.1

Type RM Length L Ch R = 1 ,19568.16,75.16,91.44,101.05
XS GIS Cut Line= 5
     642602.4781    4319896.1109     642536.9729    4319941.3046
     642529.5457    4319949.2308     642521.4651    4319954.8424
      642465.556    4320003.9288
#Sta/Elev= 30
       0 1079.73    3.06 1079.02    9.18 1077.22   12.24 1075.51    15.3 1074.54
   33.67 1069.46   39.79 1067.47   42.85 1065.85   48.97 1064.09   64.28 1058.81
    70.4 1055.57   76.52 1053.44   85.01 1050.08   87.73 1049.48    92.9  1048.8
   95.36 1049.03   97.82 1049.96  100.28 1051.91  103.26 1053.98  106.23 1055.65
  112.19 1058.43  121.11 1061.55  133.02  1064.3  138.97 1066.21  144.92 1068.92
  150.87 1072.77  153.85 1074.37  162.78  1077.3  168.73 1078.48  174.68 1080.01
#Mann= 3 , 0 , 0
       0      .1       0   85.01      .1       0   97.82      .1       0
Bank Sta=85.01,97.82
XS Rating Curve= 0 ,0
Exp/Cntr=0.3,0.1

Type RM Length L Ch R = 1 ,19476.72,90.65,91.45,89.03
XS GIS Cut Line= 5
     642602.4781    4319874.9442      642552.546    4319876.4972
     642522.2491    4319865.5313     642509.9596    4319862.3042
      642441.082    4319852.4546
#Sta/Elev= 30
       0 1080.02    2.94 1079.18    8.82 1076.16   23.51 1071.11   26.45  1069.9
   29.39 1068.06    38.2 1065.01   44.08 1062.66   47.02  1060.2   52.89 1057.46
   61.67 1053.78    64.6 1052.05   67.53 1049.14   70.46 1044.64   73.39 1043.89
   79.25 1043.24   82.18 1043.47   84.72 1044.23   87.26 1045.48    89.8  1047.1
   94.88 1048.94  106.98 1054.08  110.01 1056.16  113.03 1057.96  125.13 1062.89
  131.18 1066.54  146.31 1071.99  149.34 1073.27  152.36  1075.2  164.46 1079.46
#Mann= 3 , 0 , 0
       0      .1       0   70.46      .1       0   84.72      .1       0
Bank Sta=70.46,84.72
XS Rating Curve= 0 ,0
Exp/Cntr=0.3,0.1

Type RM Length L Ch R = 1 ,19385.27,74.74,91.43,108.14
XS GIS Cut Line= 4
     642603.2278    4319776.6072     642520.4719    4319779.9705
     642508.1153    4319781.2831     642448.1817    4319767.6113
#Sta/Elev= 30
       0 1071.13     9.2  1067.9   15.34  1065.4   21.47 1063.57   24.54 1062.41
   30.68  1059.5   33.74 1057.63   36.81 1055.39   39.88 1054.22   46.01 1052.08
   55.22  1049.3   58.28 1048.16   64.42 1046.84   70.55 1045.15   73.62 1043.82
   76.69 1041.93   82.82 1039.58   85.31 1038.92   92.77 1037.72   95.25 1037.84
   98.32 1038.84  104.47 1042.18  113.69 1046.94  116.77 1049.33  119.84 1052.11
  135.21 1060.67  138.28 1063.62  141.36 1065.08  153.65 1069.53  156.72 1071.47
#Mann= 3 , 0 , 0
       0      .1       0   82.82      .1       0   98.32      .1       0
Bank Sta=82.82,98.32
XS Rating Curve= 0 ,0
Exp/Cntr=0.3,0.1

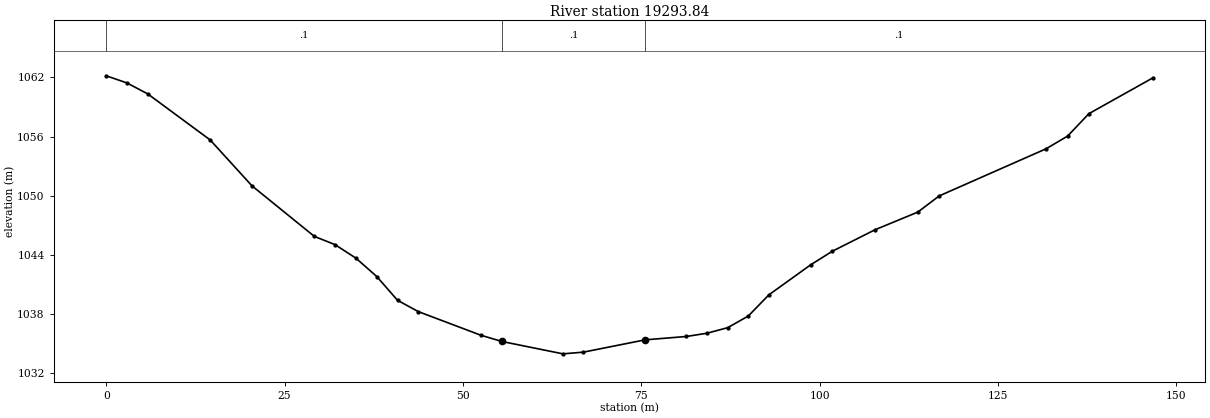
Type RM Length L Ch R = 1 ,19293.84,100.01,91.44,67.61
XS GIS Cut Line= 5
     642589.6615    4319738.3968     642543.4387    4319707.8308
     642534.5162     4319700.649     642519.0899    4319676.2042
     642473.0525    4319654.3694
#Sta/Elev= 30
       0 1062.17    2.92 1061.44    5.83 1060.33   14.58 1055.66   20.42 1051.02
   29.17 1045.89   32.08 1045.05      35 1043.68   37.92 1041.82   40.83 1039.41
   43.75 1038.26    52.5 1035.87   55.42 1035.24   64.01 1033.98   66.87 1034.15
   75.54  1035.4   81.32 1035.74   84.21 1036.07    87.1 1036.63   89.99 1037.81
   92.88 1039.96   98.77 1043.02  101.77 1044.38  107.76 1046.56  113.76 1048.35
  116.75 1049.99  131.74 1054.77  134.74 1056.05  137.74 1058.33  146.73 1061.97
#Mann= 3 , 0 , 0
       0      .1       0   55.42      .1       0   75.54      .1       0
Bank Sta=55.42,75.54
XS Rating Curve= 0 ,0
Exp/Cntr=0.3,0.1