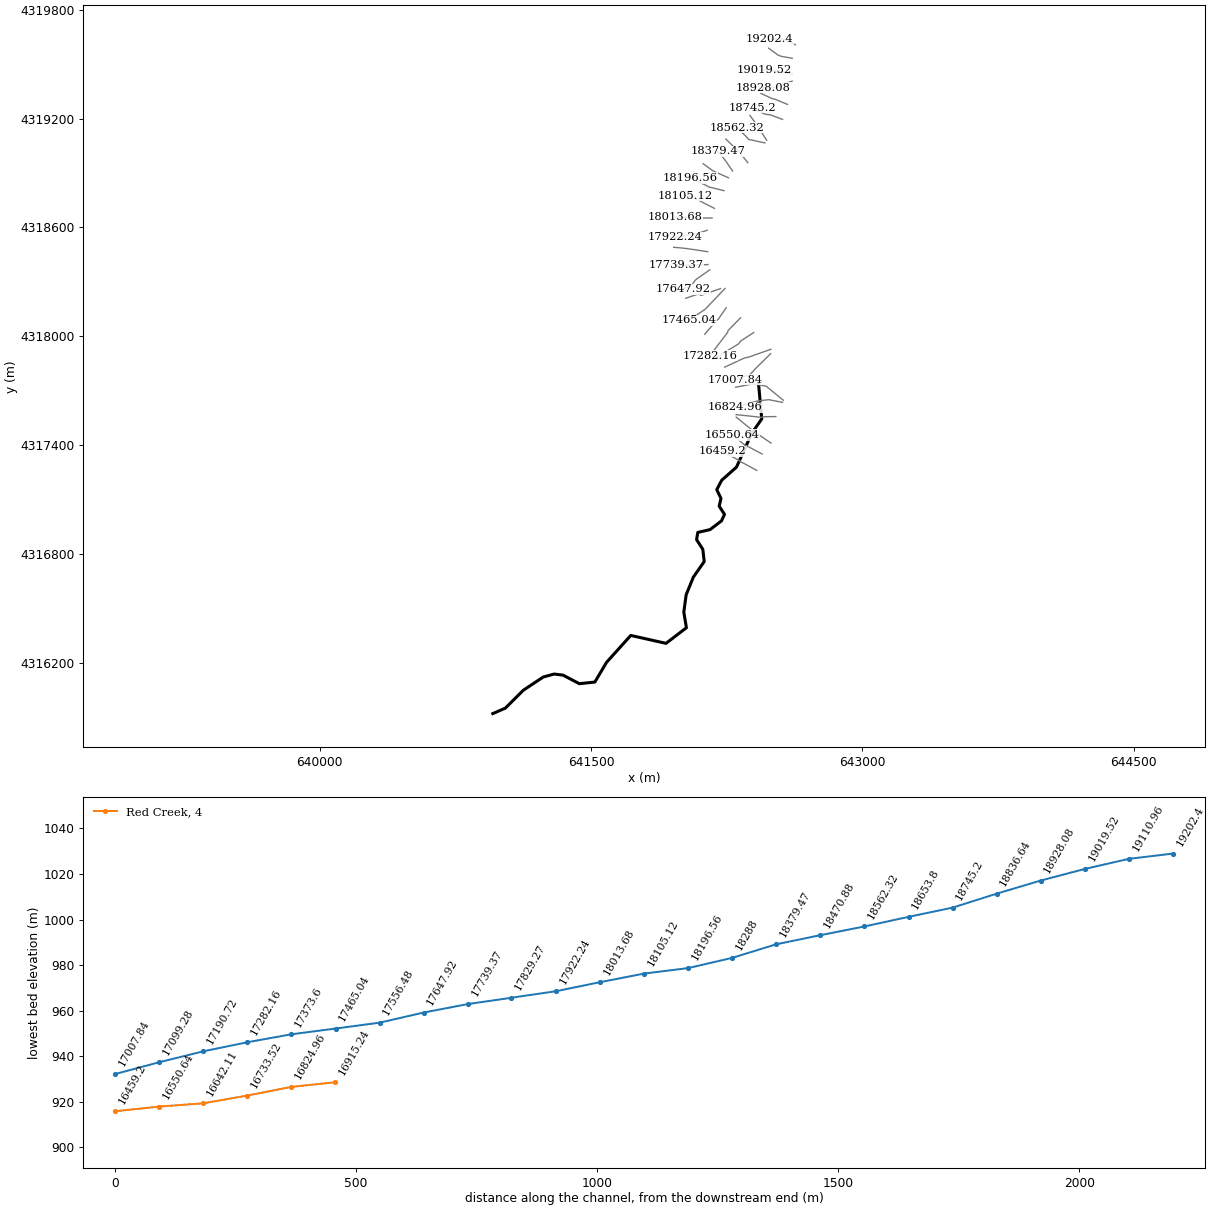
HEC-RAS study RedCreek.prj: RedCreek

--- RedCreek.g01 (geometry) --- (continued)

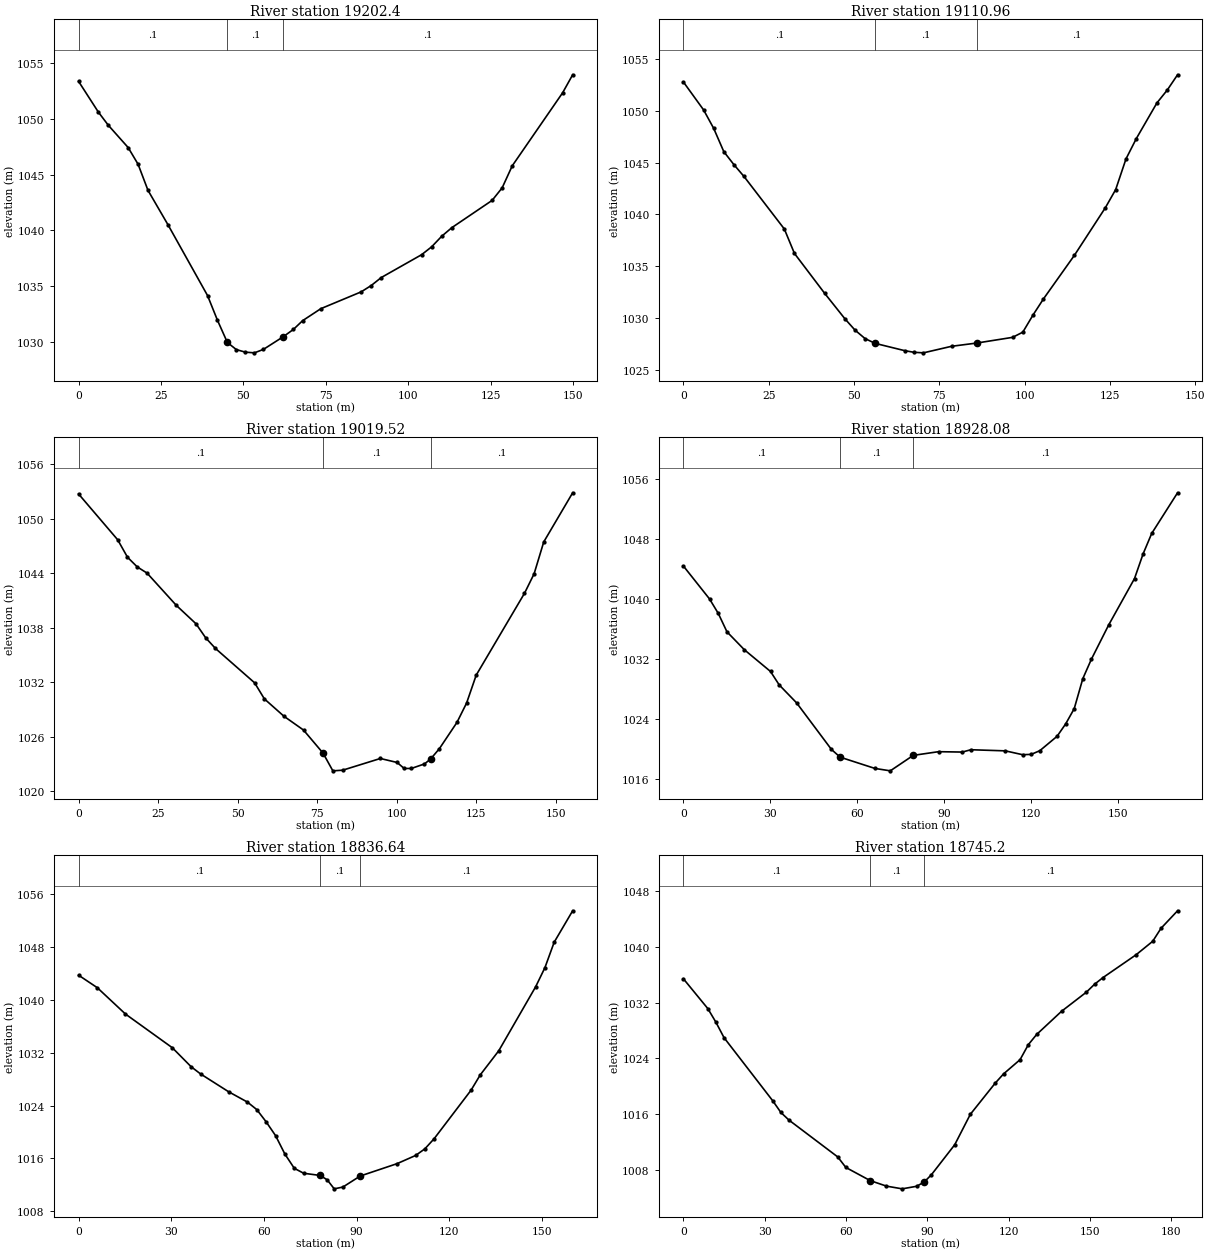
Type RM Length L Ch R = 1 ,19202.4 ,88.39,91.44,93.22
XS GIS Cut Line= 6
      642629.157    4319606.7443      642587.832    4319624.8882
     642578.4064    4319630.4167     642570.8517    4319635.5021
     642563.1258    4319638.5713     642486.8109    4319635.8486
#Sta/Elev= 30
       0 1053.39    6.02 1050.62    9.03 1049.44   15.04 1047.44   18.05 1045.94
   21.06 1043.59   27.08 1040.52   39.11 1034.14   42.12 1031.92   45.13 1029.92
   47.86 1029.28    50.6 1029.05   53.33 1028.99   56.06  1029.3   62.13 1030.45
   65.17  1031.1   67.94 1031.88   73.48 1032.96    85.7 1034.47   88.75 1035.04
   91.81 1035.76  104.03 1037.81  107.08 1038.52  110.13 1039.47  113.19 1040.24
  125.41 1042.69  128.46 1043.82  131.52  1045.8  146.79 1052.36  149.84 1053.98
#Mann= 3 , 0 , 0
       0      .1       0   45.13      .1       0   62.13      .1       0
Bank Sta=45.13,62.13
XS Rating Curve= 0 ,0
Exp/Cntr=0.3,0.1

Type RM Length L Ch R = 1 ,19110.96,87.38,91.44,100.03
XS GIS Cut Line= 4
     642612.0473    4319532.0435      642550.859    4319542.7989
     642533.0132    4319549.9371      642481.872    4319587.6061
#Sta/Elev= 30
       0 1052.75    5.92 1050.06    8.88 1048.28   11.83 1046.05   14.79  1044.8
   17.75 1043.66   29.58  1038.6   32.54 1036.25   41.42  1032.4   47.33 1029.96
   50.29 1028.87   53.25 1028.05   56.21 1027.59   64.87 1026.89   67.62 1026.73
   70.36 1026.68    78.6 1027.31   85.94 1027.62   96.47 1028.17   99.49 1028.67
  102.52 1030.34  105.54 1031.87  114.62 1036.07  123.69 1040.65  126.72  1042.4
  129.74 1045.35  132.77 1047.31  138.81 1050.74  141.84 1051.98  144.86 1053.45
#Mann= 3 , 0 , 0
       0      .1       0   56.21      .1       0   85.94      .1       0
Bank Sta=56.21,85.94
XS Rating Curve= 0 ,0
Exp/Cntr=0.3,0.1

Type RM Length L Ch R = 1 ,19019.52,85.92,91.44,104
XS GIS Cut Line= 6
     642608.3431    4319444.7308      642518.549    4319465.7054
       642511.09    4319463.0867     642504.4235    4319463.2795
     642492.8314    4319466.8167      642456.472     4319467.485
#Sta/Elev= 30
       0 1052.72   12.29 1047.68   15.37 1045.76   18.44 1044.69   21.52 1044.01
   30.74 1040.45   36.88 1038.44   39.96 1036.88   43.03 1035.71   55.33 1031.93
    58.4 1030.16   64.55 1028.25    70.7 1026.73   76.84 1024.19   79.92 1022.24
   82.99 1022.31   94.85  1023.6  100.12 1023.16  102.34  1022.5  104.56  1022.5
  108.71    1023  110.64 1023.54   113.4 1024.68  118.92 1027.57  121.95  1029.7
  124.98 1032.78  140.14 1041.78  143.17 1043.93   146.2 1047.44  155.29 1052.85
#Mann= 3 , 0 , 0
       0      .1       0   76.84      .1       0  110.64      .1       0
Bank Sta=76.84,110.64
XS Rating Curve= 0 ,0
Exp/Cntr=0.3,0.1

Type RM Length L Ch R = 1 ,18928.08,97.5,91.44,78.8
XS GIS Cut Line= 6
     642611.7827     4319405.837     642548.7061    4319386.0613
     642535.9656    4319382.5019     642531.6706    4319378.3267
     642523.3534    4319371.2424     642449.0636    4319369.3244
#Sta/Elev= 30
       0 1044.41    9.01 1040.03   12.02 1038.11   15.02 1035.66   21.03 1033.27
   30.05 1030.38   33.05 1028.59   39.06  1026.2   51.08    1020   54.09 1018.97
    66.1 1017.47    71.4 1017.15   79.33 1019.21   88.05  1019.7   96.25 1019.65
   99.22 1019.96  111.11 1019.81  117.06  1019.3  120.03 1019.34     123 1019.83
  128.95 1021.74  131.92 1023.39  134.89 1025.43  137.86 1029.43  140.84 1032.03
  146.78 1036.57   155.7 1042.75  158.67 1046.04  161.64 1048.76  170.56 1054.17
#Mann= 3 , 0 , 0
       0      .1       0   54.09      .1       0   79.33      .1       0
Bank Sta=54.09,79.33
XS Rating Curve= 0 ,0
Exp/Cntr=0.3,0.1

Type RM Length L Ch R = 1 ,18836.64,90.64,91.44,94.81
XS GIS Cut Line= 5
     642586.0519    4319277.7784     642515.8392    4319306.5649
     642509.0538    4319307.5002      642500.989    4319309.8314
     642438.5464    4319338.6327
#Sta/Elev= 30
       0 1043.77    6.07 1041.87   15.18 1037.88   30.35 1032.77   36.42  1029.9
   39.46 1028.81   48.57  1026.1   54.64 1024.54   57.67  1023.4   60.71 1021.54
   63.74 1019.46   66.78 1016.65   69.81  1014.5   72.85 1013.75   78.17 1013.42
   80.45 1012.76   82.73 1011.39   85.53 1011.66   91.13 1013.33  103.09 1015.21
  109.07 1016.45  112.06 1017.45  115.05 1018.98  127.01 1026.34     130 1028.67
  135.98 1032.32  147.93 1042.03  150.92 1044.92  153.91 1048.77  159.89 1053.53
#Mann= 3 , 0 , 0
       0      .1       0   78.17      .1       0   91.13      .1       0
Bank Sta=78.17,91.13
XS Rating Curve= 0 ,0
Exp/Cntr=0.3,0.1

Type RM Length L Ch R = 1 ,18745.2 ,99.56,91.4,81.86
XS GIS Cut Line= 6
     642558.9321     4319195.096     642485.9765    4319222.3258
     642483.4443    4319221.1034     642472.8018    4319222.3491
       642458.67    4319225.1749     642390.2598    4319259.2575
#Sta/Elev= 30
       0  1035.4    8.99 1031.13   11.98 1029.17   14.98 1026.95   32.95 1017.89
   35.94 1016.22   38.94 1015.12   56.91 1009.84    59.9 1008.33   68.89 1006.44
   74.88 1005.65   80.68 1005.26   86.03 1005.63   88.82 1006.25   91.41 1007.26
  100.06 1011.59  105.82 1015.96  114.99 1020.43  118.05 1021.75  124.16  1023.8
  127.22 1025.96  130.28 1027.42  139.45 1030.74  148.62 1033.49  151.68 1034.64
  154.74 1035.58  166.97 1038.86  173.08 1040.79  176.14 1042.65  182.25 1045.17
#Mann= 3 , 0 , 0
       0      .1       0   68.89      .1       0   88.82      .1       0
Bank Sta=68.89,88.82
XS Rating Curve= 0 ,0
Exp/Cntr=0.3,0.1

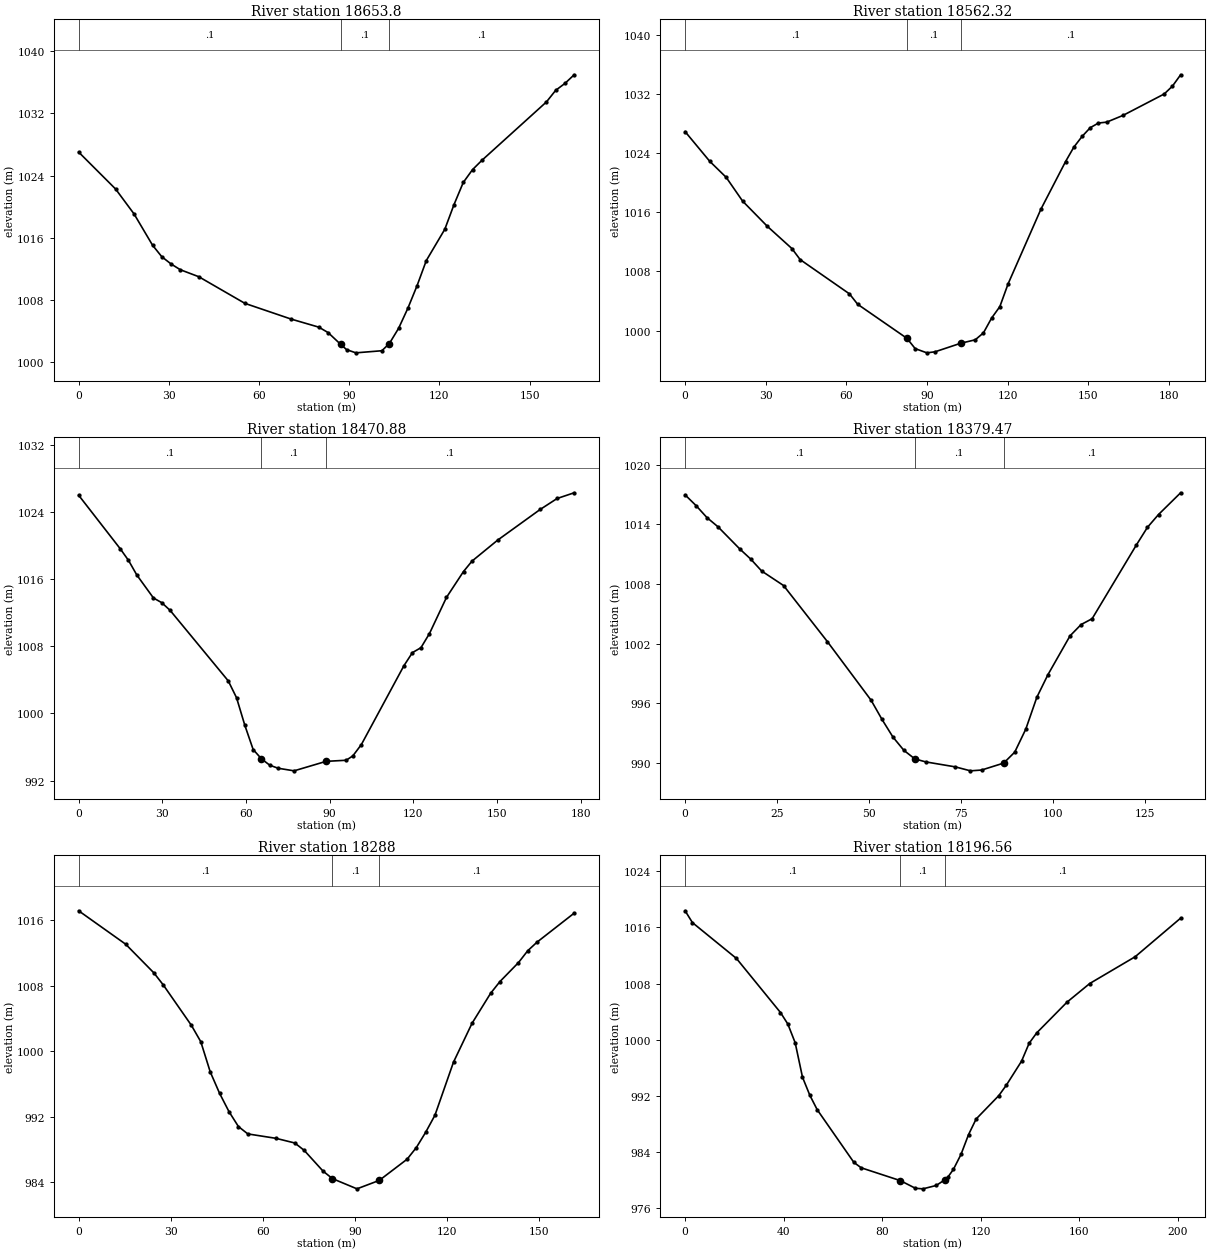
Type RM Length L Ch R = 1 ,18653.8 ,86.22,91.48,90.25
XS GIS Cut Line= 4
     642470.9579    4319080.6634     642417.6228    4319163.2995
     642414.6283    4319167.2933     642378.3536    4319216.9241
#Sta/Elev= 30
       0 1027.03   12.29 1022.28   18.44 1019.07   24.59 1015.05   27.66 1013.57
   30.74 1012.64   33.81  1011.9   39.96    1011   55.32 1007.57   70.69 1005.55
   79.91 1004.51   82.99 1003.81    87.1 1002.32   89.13 1001.62   92.21 1001.21
  100.85 1001.48  103.34  1002.4  106.42 1004.36  109.49 1006.93  112.57 1009.85
  115.64 1013.08  121.79  1017.1  124.86 1020.28  127.93 1023.12  131.01 1024.77
  134.08 1025.95   155.6 1033.48  158.67 1034.97  161.75 1035.86  164.82 1036.97
#Mann= 3 , 0 , 0
       0      .1       0    87.1      .1       0  103.34      .1       0
Bank Sta=87.1,103.34
XS Rating Curve= 0 ,0
Exp/Cntr=0.3,0.1

Type RM Length L Ch R = 1 ,18562.32,109.33,91.44,93.83
XS GIS Cut Line= 6
     642460.9809    4319065.6152     642377.3014     4319083.746
     642372.9708    4319083.9235     642366.1263    4319089.9461
     642361.4335    4319097.4819     642305.5379    4319149.6206
#Sta/Elev= 30
       0 1026.93    9.17 1022.91   15.29 1020.74   21.41 1017.52   30.58 1014.12
   39.75  1011.1   42.81 1009.61   61.16 1004.97   64.22 1003.56   82.56  998.95
   85.62  997.56   89.96  996.99   92.99  997.13  102.57  998.29  107.95  998.75
  111.01  999.69  114.06  1001.7  117.12 1003.25  120.18 1006.32  132.41 1016.44
  141.58 1022.88  144.64 1024.82   147.7 1026.27  150.76 1027.46  153.81 1028.09
  156.87 1028.21  162.99 1029.13  178.27 1032.02  181.33 1033.08  184.39 1034.62
#Mann= 3 , 0 , 0
       0      .1       0   82.56      .1       0  102.57      .1       0
Bank Sta=82.56,102.57
XS Rating Curve= 0 ,0
Exp/Cntr=0.3,0.1

Type RM Length L Ch R = 1 ,18470.88,94.83,91.41,86.91
XS GIS Cut Line= 5
     642366.3922    4318957.1358       642321.52    4319012.8476
     642309.5605    4319025.2125     642302.2638     4319031.462
     642245.3451    4319086.7819
#Sta/Elev= 30
       0 1025.99    14.9 1019.62   17.88 1018.23   20.86 1016.49   26.83 1013.75
   29.81 1013.19   32.79 1012.28   53.65 1003.88   56.63 1001.87   59.61  998.58
   62.59   995.7   65.57  994.59   68.55  993.83   71.54  993.47   77.27  993.16
   88.74  994.29   95.94  994.42   98.34  994.94   101.4  996.29  116.66 1005.68
  119.71 1007.24  122.77 1007.83  125.82 1009.51  131.93 1013.82  138.03  1016.9
  141.08 1018.14  150.24 1020.63  165.51 1024.29  171.61  1025.6  177.72 1026.28
#Mann= 3 , 0 , 0
       0      .1       0   65.57      .1       0   88.74      .1       0
Bank Sta=65.57,88.74
XS Rating Curve= 0 ,0
Exp/Cntr=0.3,0.1

Type RM Length L Ch R = 1 ,18379.47,88.14,91.47,94.68
XS GIS Cut Line= 4
     642282.3868    4318910.8337     642241.8636    4318969.6496
     642237.9026    4318974.4232     642201.6887    4319018.6516
#Sta/Elev= 30
       0 1016.97    2.98 1015.89    5.95 1014.68    8.93 1013.76   14.88 1011.52
   17.86  1010.5   20.83  1009.3   26.78 1007.84   38.69  1002.2   50.59  996.29
   53.57  994.35   56.54  992.58   59.52  991.24    62.5  990.38   65.47  990.08
   73.49  989.58   77.63  989.18   80.64  989.26   86.65  989.96   89.66  991.06
   92.67  993.38   95.68  996.59   98.69  998.86   104.7 1002.77  107.71 1003.91
  110.72  1004.5  122.76 1011.93  125.76  1013.7  128.77 1014.99  134.79 1017.18
#Mann= 3 , 0 , 0
       0      .1       0    62.5      .1       0   86.65      .1       0
Bank Sta=62.5,86.65
XS Rating Curve= 0 ,0
Exp/Cntr=0.3,0.1

Type RM Length L Ch R = 1 ,18288   ,89.34,91.44,91.49
XS GIS Cut Line= 5
     642259.8972     4318873.448     642184.2265    4318906.8377
     642179.2216    4318909.9385     642173.2498    4318912.1169
     642119.4031    4318951.2356
#Sta/Elev= 30
       0 1017.18   15.32  1013.1   24.51  1009.6   27.57 1008.13   36.76 1003.18
   39.82 1001.18   42.89   997.5   45.95  994.87   49.01  992.64   52.08  990.82
   55.14  989.92   64.33  989.38   70.46  988.81   73.52  987.91   79.65  985.38
   82.71  984.46   90.72  983.21   97.98  984.24  107.06  986.83  110.08  988.26
  113.11  990.12  116.13   992.2  122.18  998.69  128.23 1003.44  134.28  1007.1
  137.31 1008.53  143.36 1010.85  146.38  1012.3  149.41 1013.35  161.51 1016.89
#Mann= 3 , 0 , 0
       0      .1       0   82.71      .1       0   97.98      .1       0
Bank Sta=82.71,97.98
XS Rating Curve= 0 ,0
Exp/Cntr=0.3,0.1

Type RM Length L Ch R = 1 ,18196.56,94.77,91.44,94.24
XS GIS Cut Line= 6
     642235.2909    4318802.8041     642157.1258    4318821.6302
     642153.2678    4318822.2259     642139.7399    4318829.3044
     642131.6284    4318833.8584     642047.9655    4318872.6542
#Sta/Elev= 30
       0 1018.37    2.98 1016.68   20.84 1011.57   38.71 1003.86   41.69 1002.22
   44.67  999.55   47.64  994.64   50.62  992.06    53.6  990.01   68.49  982.49
   71.47  981.72   87.36  979.89   93.46   978.8   96.52  978.72   101.9   979.2
  105.31  979.99  106.55  980.35  108.87  981.49  111.95  983.62  115.02  986.45
   118.1  988.68  127.32  992.02  130.39  993.52  136.54  996.93  139.61  999.48
  142.69 1000.96  154.98 1005.34  164.21    1008  182.65 1011.82  201.09 1017.32
#Mann= 3 , 0 , 0
       0      .1       0   87.36      .1       0  105.31      .1       0
Bank Sta=87.36,105.31
XS Rating Curve= 0 ,0
Exp/Cntr=0.3,0.1

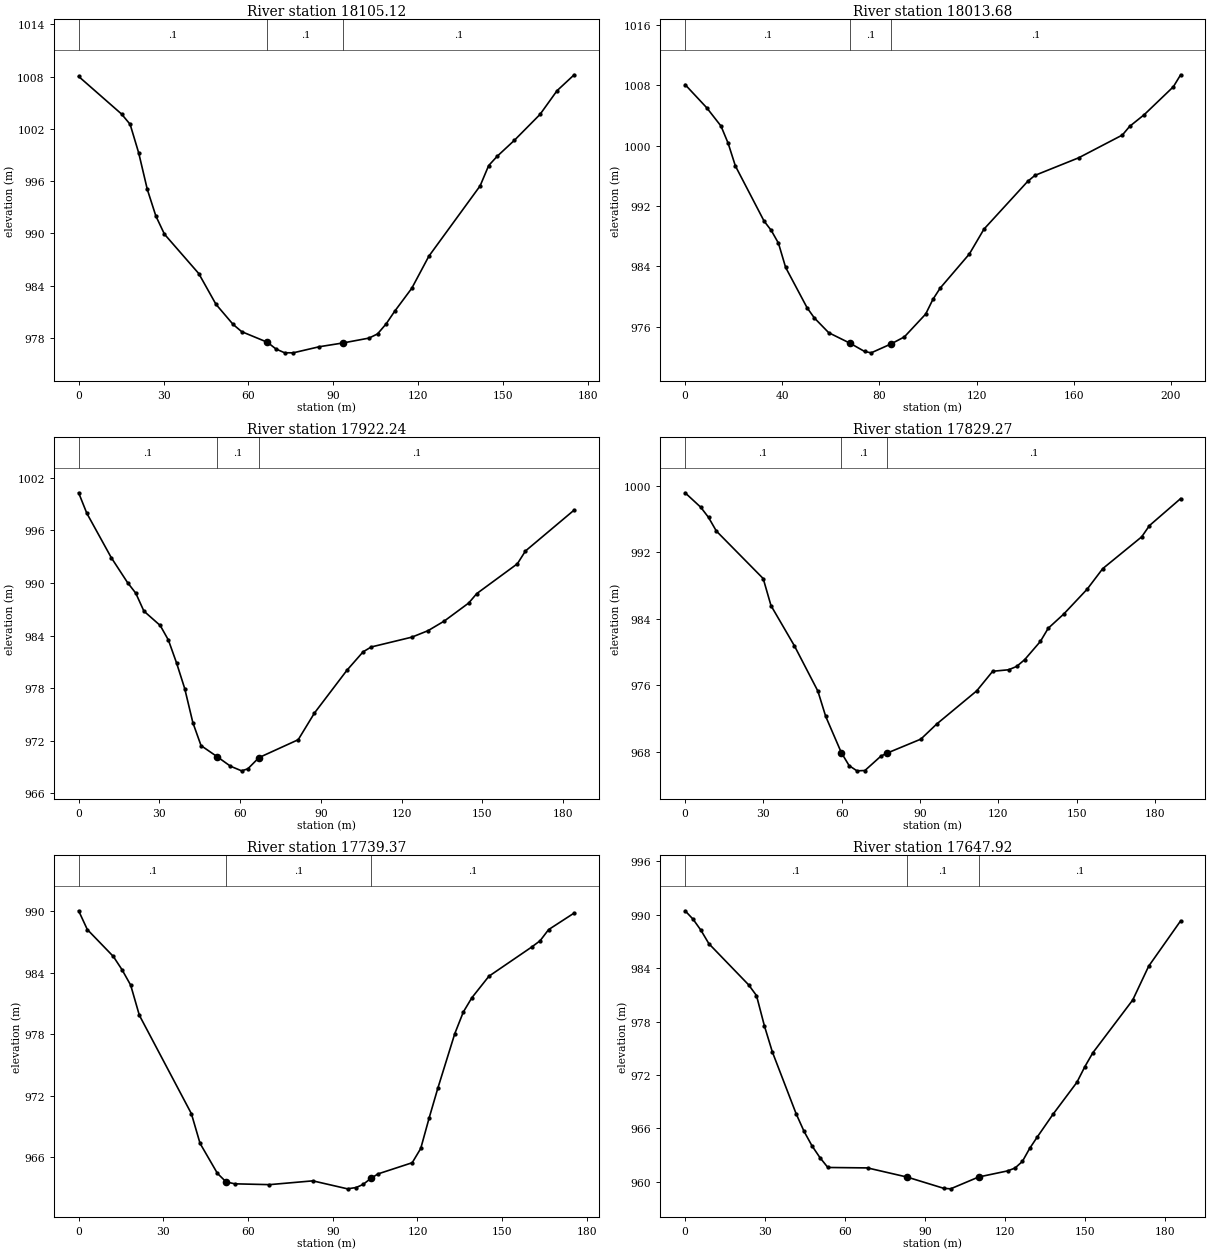
Type RM Length L Ch R = 1 ,18105.12,86.86,91.44,100.32
XS GIS Cut Line= 6
     642182.1095    4318705.1726     642119.6782    4318736.2592
     642114.9427     4318740.008     642106.5456    4318743.8916
     642099.4316    4318748.5339     642022.5654    4318775.8165
#Sta/Elev= 30
       0 1008.01   15.16  1003.7   18.19 1002.52   21.23  999.23   24.26  995.06
   27.29     992   30.32  989.92   42.45   985.4   48.52  981.88   54.58  979.57
   57.61  978.74   66.71  977.52   69.74  976.75   72.76  976.32   75.78  976.31
   85.03  977.01   93.53  977.45  102.59     978  105.61  978.48  108.63  979.62
  111.65  981.07   117.7  983.71  123.74  987.39  141.86  995.46  144.88  997.79
  147.91  998.86  153.95 1000.68  163.01 1003.65  169.05 1006.38  175.09  1008.2
#Mann= 3 , 0 , 0
       0      .1       0   66.71      .1       0   93.53      .1       0
Bank Sta=66.71,93.53
XS Rating Curve= 0 ,0
Exp/Cntr=0.3,0.1

Type RM Length L Ch R = 1 ,18013.68,90.17,91.44,94.13
XS GIS Cut Line= 5
     642168.9465     4318651.859     642095.0532    4318652.4522
     642084.4806    4318654.6948      642076.157    4318654.8403
     641965.2169    4318657.1507
#Sta/Elev= 30
       0  1008.1    8.87 1005.04   14.78  1002.6   17.73 1000.31   20.69  997.32
   32.51     990   35.47  988.76   38.43  987.07   41.38  983.86   50.25  978.49
    53.2  977.16   59.12   975.2   67.98  973.79    73.9  972.71    76.6  972.53
    84.7   973.7   90.25  974.64   99.03  977.67  102.03  979.63  105.02  981.12
  117.02  985.64  123.02  988.93  141.01  995.26  144.01  996.06  162.01  998.39
     180 1001.41     183 1002.56     189 1004.11  200.99 1007.81  203.99  1009.4
#Mann= 3 , 0 , 0
       0      .1       0   67.98      .1       0    84.7      .1       0
Bank Sta=67.98,84.7
XS Rating Curve= 0 ,0
Exp/Cntr=0.3,0.1

Type RM Length L Ch R = 1 ,17922.24,94.53,92.97,90.05
XS GIS Cut Line= 6
     642141.8266    4318584.3901     642089.9446    4318567.4349
     642086.6229    4318565.8565     642080.0467    4318563.6761
     642075.7072    4318563.8367     641962.5711     4318545.364
#Sta/Elev= 30
       0 1000.29    3.03  997.96   12.13  992.89   18.19  990.04   21.23  988.84
   24.26  986.79   30.32  985.15   33.36  983.49   36.39  980.88   39.42  977.96
   42.45  974.07   45.49  971.45   51.55  970.17   56.42   969.1   60.57  968.57
   62.88   968.8   67.02  970.08    81.6  972.12   87.63  975.16    99.7  980.04
  105.73  982.15  108.75   982.7  123.83  983.82  129.86  984.56   135.9  985.66
  144.95  987.71  147.96  988.79  163.05  992.19  166.06  993.65  184.16  998.32
#Mann= 3 , 0 , 0
       0      .1       0   51.55      .1       0   67.02      .1       0
Bank Sta=51.55,67.02
XS Rating Curve= 0 ,0
Exp/Cntr=0.3,0.1

Type RM Length L Ch R = 1 ,17829.27,88.1,89.9,91.78
XS GIS Cut Line= 4
     642144.9134    4318466.2644     642079.8414    4318476.3413
     642013.1747     4318485.673     641956.6769    4318490.7736
#Sta/Elev= 30
       0  999.19    5.99  997.45    8.98  996.22   11.97  994.58   29.93  988.85
   32.92  985.59    41.9  980.74   50.88  975.29   53.88  972.24   59.86  967.88
   62.85  966.31   65.85  965.68   68.91  965.72   75.03  967.45    77.2  967.79
   90.33   969.5   96.45  971.33  111.75  975.32  117.87  977.68  123.98  977.86
  127.04  978.26   130.1  979.07  136.15  981.28  139.14  982.86  145.11  984.58
  154.06  987.57  160.04  990.05  174.96  993.88  177.95  995.24  189.89  998.49
#Mann= 3 , 0 , 0
       0      .1       0   59.86      .1       0    77.2      .1       0
Bank Sta=59.86,77.2
XS Rating Curve= 0 ,0
Exp/Cntr=0.3,0.1

Type RM Length L Ch R = 1 ,17739.37,78.67,91.45,104.12
XS GIS Cut Line= 4
     642146.2364    4318395.4882     642048.0507    4318390.9192
     642040.3743    4318392.0601     641970.9495     4318390.858
#Sta/Elev= 30
       0  990.07    3.07  988.24   12.29  985.61   15.36  984.32   18.43  982.81
    21.5  979.87   39.93  970.26      43  967.36   49.15  964.43   52.22   963.6
   55.29  963.41   67.58  963.33   82.93   963.7   95.22  962.92   98.29  963.05
  100.74  963.35  103.47  963.94  106.05  964.38  118.13  965.47  121.15  966.86
  124.17  969.88  127.19  972.73  133.22  978.08  136.24  980.19  139.26  981.58
   145.3  983.68  160.39  986.52  163.41  987.14  166.43  988.23  175.49  989.85
#Mann= 3 , 0 , 0
       0      .1       0   52.22      .1       0  103.47      .1       0
Bank Sta=52.22,103.47
XS Rating Curve= 0 ,0
Exp/Cntr=0.3,0.1

Type RM Length L Ch R = 1 ,17647.92,104.21,91.44,79.34
XS GIS Cut Line= 6
     642156.1582     4318366.384      642083.045    4318315.3605
     642075.1591    4318308.7013     642069.6168    4318299.7549
     642056.1633    4318282.5521     642007.3298     4318259.889
#Sta/Elev= 30
       0  990.44    2.97   989.5    5.94  988.25    8.92  986.74   23.78  982.13
   26.75  980.92   29.72  977.51   32.69  974.59   41.61  967.64   44.58  965.66
   47.55  964.04   50.52  962.72   53.49  961.61   68.35  961.56   83.21  960.53
    96.9  959.27   99.48  959.21     110  960.54  120.92  961.23  123.65  961.55
  126.38  962.29  129.11  963.75  131.84  964.98  137.82  967.57   146.8  971.17
  149.79  972.93  152.78  974.49  167.73  980.42  173.71  984.22  185.68  989.31
#Mann= 3 , 0 , 0
       0      .1       0   83.21      .1       0     110      .1       0
Bank Sta=83.21,110
XS Rating Curve= 0 ,0
Exp/Cntr=0.3,0.1

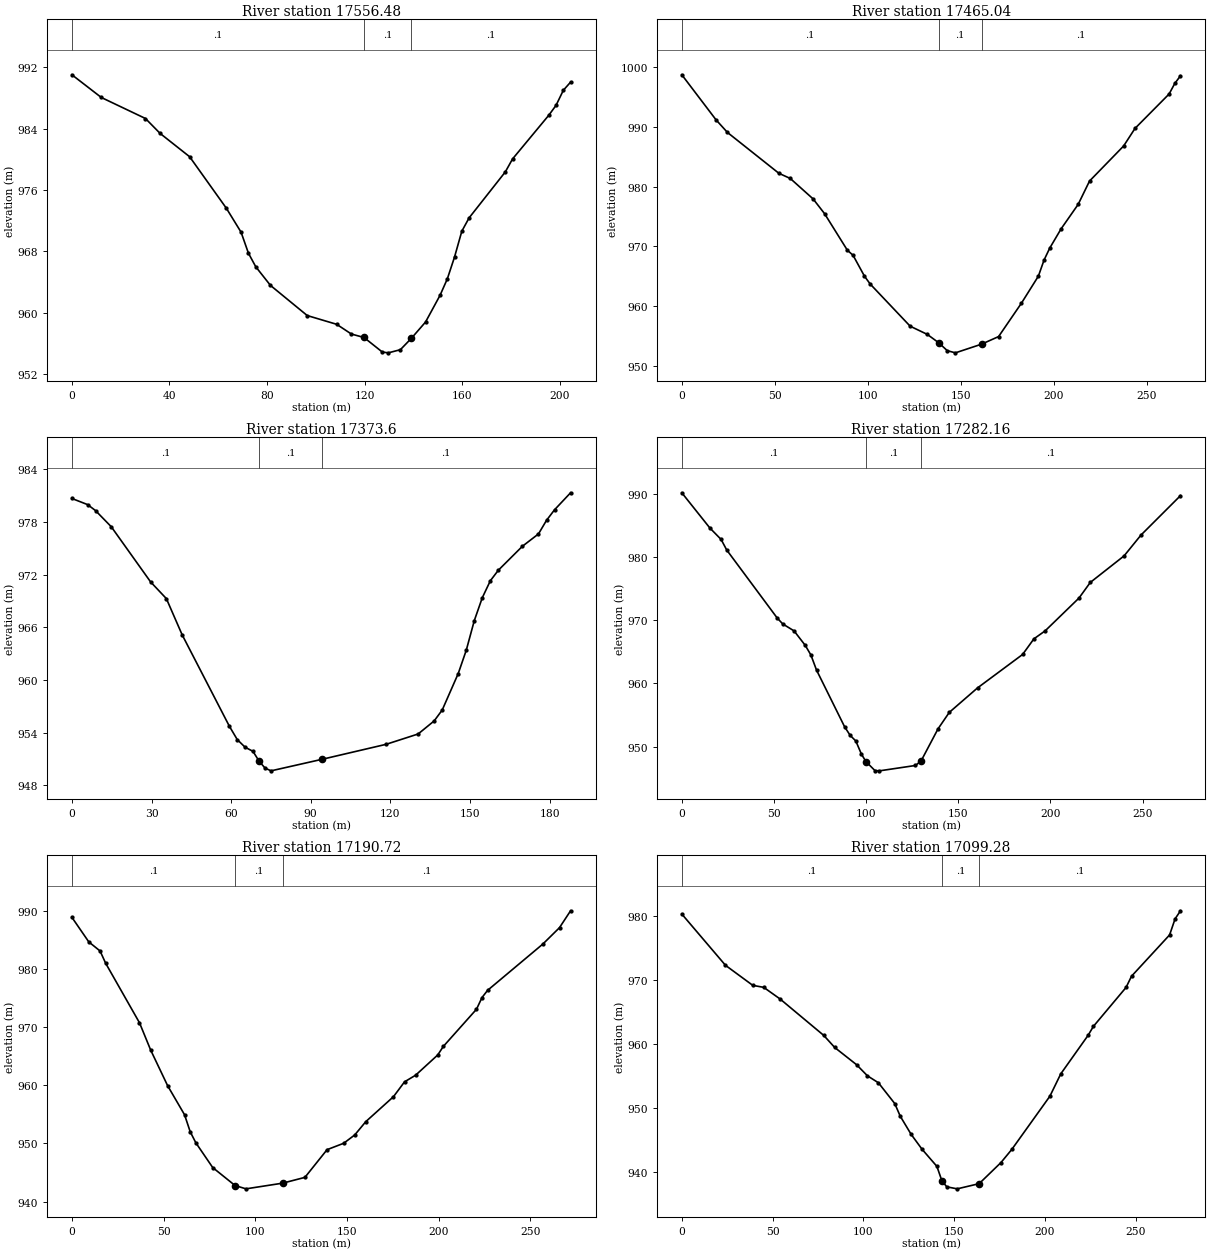
Type RM Length L Ch R = 1 ,17556.48,77.14,91.44,96.21
XS GIS Cut Line= 6
     642215.2927     4318263.064     642107.0163    4318225.4902
     642101.3278    4318230.7819     642089.1482     4318232.655
      642082.432    4318229.6818     642023.2049    4318209.8827
#Sta/Elev= 30
       0  991.01   12.06  988.05   30.16  985.31   36.19  983.36   48.26  980.33
   63.34  973.61   69.37  970.49   72.39  967.75    75.4  965.98   81.43  963.55
   96.51  959.62  108.58  958.48  114.61  957.21  119.79  956.76  127.31  954.86
  129.77  954.76   134.7  955.17   139.2  956.65  145.03  958.78  150.97  962.26
  153.95   964.4  156.92  967.26  159.89  970.61  162.87  972.35  177.74  978.35
  180.71  980.04  195.58  985.74  198.55  987.03  201.53  988.99   204.5  990.05
#Mann= 3 , 0 , 0
       0      .1       0  119.79      .1       0   139.2      .1       0
Bank Sta=119.79,139.2
XS Rating Curve= 0 ,0
Exp/Cntr=0.3,0.1

Type RM Length L Ch R = 1 ,17465.04,90.04,91.44,92.26
XS GIS Cut Line= 5
     642240.6928    4318263.8578     642142.7572    4318162.1302
     642140.7885    4318159.7111     642128.8822    4318147.8048
     642039.8736    4318088.4387
#Sta/Elev= 30
       0  998.73   18.42  991.18   24.56  989.07   52.19  982.24   58.33  981.37
    70.6  977.95   76.74  975.49   89.02  969.36   92.09  968.51   98.23  965.01
   101.3   963.7  122.79  956.64     132  955.27  138.14  953.87  142.77  952.54
  147.13  952.18  161.17  953.63  170.34   954.9  182.56  960.46  191.73  965.01
  194.79  967.71  197.85  969.71  203.96  972.94  213.13  977.03  219.25  980.94
  237.59  986.81   243.7  989.75  262.04  995.51   265.1  997.28  268.16  998.56
#Mann= 3 , 0 , 0
       0      .1       0  138.14      .1       0  161.17      .1       0
Bank Sta=138.14,161.17
XS Rating Curve= 0 ,0
Exp/Cntr=0.3,0.1

Type RM Length L Ch R = 1 ,17373.6 ,85.47,91.44,92.8
XS GIS Cut Line= 6
     642247.0428    4318157.4951     642208.0344    4318101.5051
     642205.8905    4318097.4864     642201.1004    4318092.6963
     642194.2761    4318087.4821     642128.7738    4318012.2385
#Sta/Elev= 30
       0  980.69    5.93  979.99     8.9  979.31   14.83  977.47   29.67  971.18
    35.6  969.28   41.54  965.16   59.34  954.74   62.31  953.22   65.27  952.35
   68.24  951.88   70.52  950.77   72.79  949.97   75.05  949.66    94.2  950.97
  118.39  952.68  130.48  953.86  136.52  955.35  139.55  956.59  145.59  960.75
  148.62  963.41  151.64  966.78  154.66  969.39  157.69  971.32  160.71  972.52
  169.78  975.25  175.82  976.65  178.85   978.2  181.87   979.4  187.92  981.34
#Mann= 3 , 0 , 0
       0      .1       0   70.52      .1       0    94.2      .1       0
Bank Sta=70.52,94.2
XS Rating Curve= 0 ,0
Exp/Cntr=0.3,0.1

Type RM Length L Ch R = 1 ,17282.16,93.67,91.44,86.09
XS GIS Cut Line= 5
     642326.1005    4318101.8531     642257.6632    4318032.4851
     642255.0914    4318023.0476     642251.3331    4318016.7704
     642156.2376    4317893.0964
#Sta/Elev= 30
       0   990.2   15.23  984.62   21.32  982.81   24.36  981.14   51.77  970.36
   54.81  969.42    60.9  968.33   66.99  966.03   70.04  964.51   73.08  962.13
   88.31  953.15   91.35  951.78    94.4   950.9   97.45  948.81   99.89  947.64
  104.78  946.21  107.23  946.17  126.78  947.02  129.84  947.75  139.01  952.82
  145.13  955.43  160.43   959.3   184.9   964.6  191.02  967.07  197.14  968.34
  215.49  973.53  221.61     976  239.96  980.21  249.14  983.51  270.55  989.75
#Mann= 3 , 0 , 0
       0      .1       0   99.89      .1       0  129.84      .1       0
Bank Sta=99.89,129.84
XS Rating Curve= 0 ,0
Exp/Cntr=0.3,0.1

Type RM Length L Ch R = 1 ,17190.72,101.8,91.44,86.89
XS GIS Cut Line= 5
     642399.1256    4318020.8904     642326.9216    4317974.2066
     642318.5753    4317961.8687     642312.4744    4317956.5875
     642172.9064    4317872.4589
#Sta/Elev= 30
       0  988.85    9.21  984.63   15.35  983.07   18.42  980.95   36.85  970.73
   42.99  966.01    52.2  959.91   61.42  954.92   64.49  952.01   67.56  950.11
   76.77  945.85   88.96  942.76   94.92  942.19  114.98  943.17  127.05  944.16
  139.12  948.92  148.18  950.02  154.21  951.45  160.25  953.74  175.34  958.03
  181.37  960.58  187.41  961.72  199.48   965.2   202.5  966.66  220.61  973.06
  223.62  975.07  226.64   976.3  256.82  984.27  265.87  987.08  271.91  989.98
#Mann= 3 , 0 , 0
       0      .1       0   88.96      .1       0  114.98      .1       0
Bank Sta=88.96,114.98
XS Rating Curve= 0 ,0
Exp/Cntr=0.3,0.1

Type RM Length L Ch R = 1 ,17099.28,72.44,91.44,93.31
XS GIS Cut Line= 5
     642494.3758    4317928.8152     642369.5363    4317885.0616
     642353.4053    4317882.5344     642344.8061    4317879.5052
     642238.7878      4317830.39
#Sta/Elev= 30
       0  980.31   24.05   972.3   39.08  969.17    45.1  968.86   54.12  967.04
   78.17  961.35   84.18  959.47   96.21  956.78  102.22  955.04  108.23  953.96
  117.25  950.71  120.26  948.74  126.27   945.9  132.28  943.57  140.45   940.9
  143.17  938.67  145.89   937.7  151.65  937.39  163.72   938.2  175.71  941.49
   181.7  943.55  202.67  951.86  208.66  955.35  223.64  961.34  226.64  962.77
  244.61  968.85  247.61   970.6  268.58  977.05  271.58  979.55  274.57  980.82
#Mann= 3 , 0 , 0
       0      .1       0  143.17      .1       0  163.72      .1       0
Bank Sta=143.17,163.72
XS Rating Curve= 0 ,0
Exp/Cntr=0.3,0.1

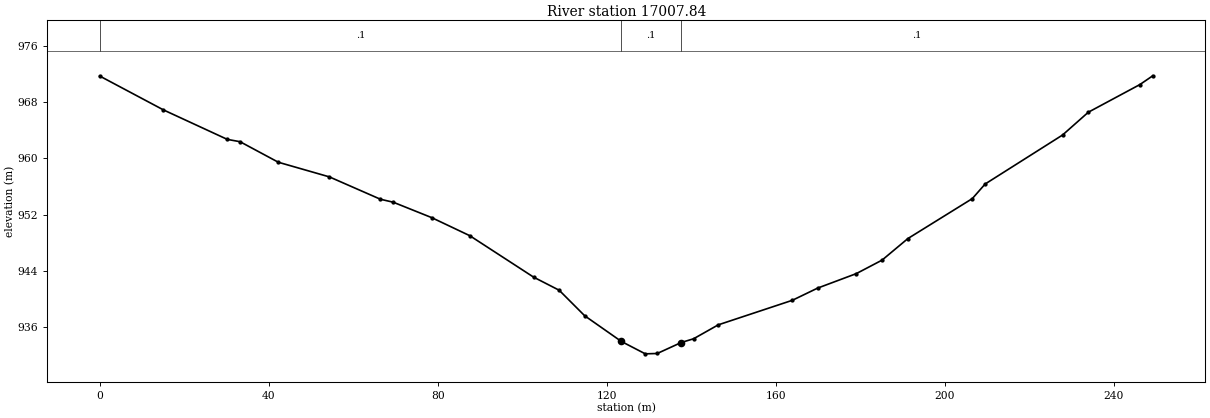
Type RM Length L Ch R = 1 ,17007.84,97.15,92.6,80.74
XS GIS Cut Line= 5
     642492.7883    4317904.2089     642408.4723    4317821.9325
      642395.804    4317806.6909     642374.2081    4317786.9982
     642295.9379    4317761.3336
#Sta/Elev= 30
       0  971.71    15.1  966.89   30.21   962.7   33.23  962.37   42.29  959.45
   54.37  957.37   66.46  954.19   69.48  953.77   78.54  951.59    87.6  949.01
   102.7  943.12  108.75  941.26  114.79  937.63  123.47  933.98  129.13  932.22
  131.96  932.27  137.63  933.83  140.55  934.36  146.39  936.34  163.93  939.83
   169.9  941.56  179.06  943.62  185.16  945.54  191.26   948.6  206.51  954.28
  209.56  956.36  227.87  963.32  233.97  966.56  246.17  970.49  249.22  971.74
#Mann= 3 , 0 , 0
       0      .1       0  123.47      .1       0  137.63      .1       0
Bank Sta=123.47,137.63
XS Rating Curve= 0 ,0
Exp/Cntr=0.3,0.1

River Reach=Red Creek       ,4
Reach XY= 30
     642425.7667    4317741.9269     642443.6322    4317545.0276
     642388.4664    4317466.0493     642303.9319    4317279.5177
     642222.1755    4317207.2863     642194.7911    4317155.2955
     642218.2067    4317107.2736     642208.2848     4317064.411
     642237.6536     4317019.564     642220.9849    4316983.4483
     642157.8816    4316935.4264     642090.0158    4316919.9482
      642083.269    4316880.2606     642117.7972    4316826.6824
     642125.5388    4316759.5018     642065.4095    4316673.4883
      642025.722    4316576.6506     642012.6251    4316481.0036
     642027.0179    4316394.7564     641914.1999    4316308.7595
     641719.3339    4316352.4158     641585.5867    4316204.3811
      641520.896    4316095.6372     641434.9447     4316086.522
     641344.6831    4316133.7372     641295.4705    4316139.6904
     641235.5423    4316123.4185     641125.2108    4316050.3933
     641025.9918    4315951.9681     640956.5386    4315921.8056

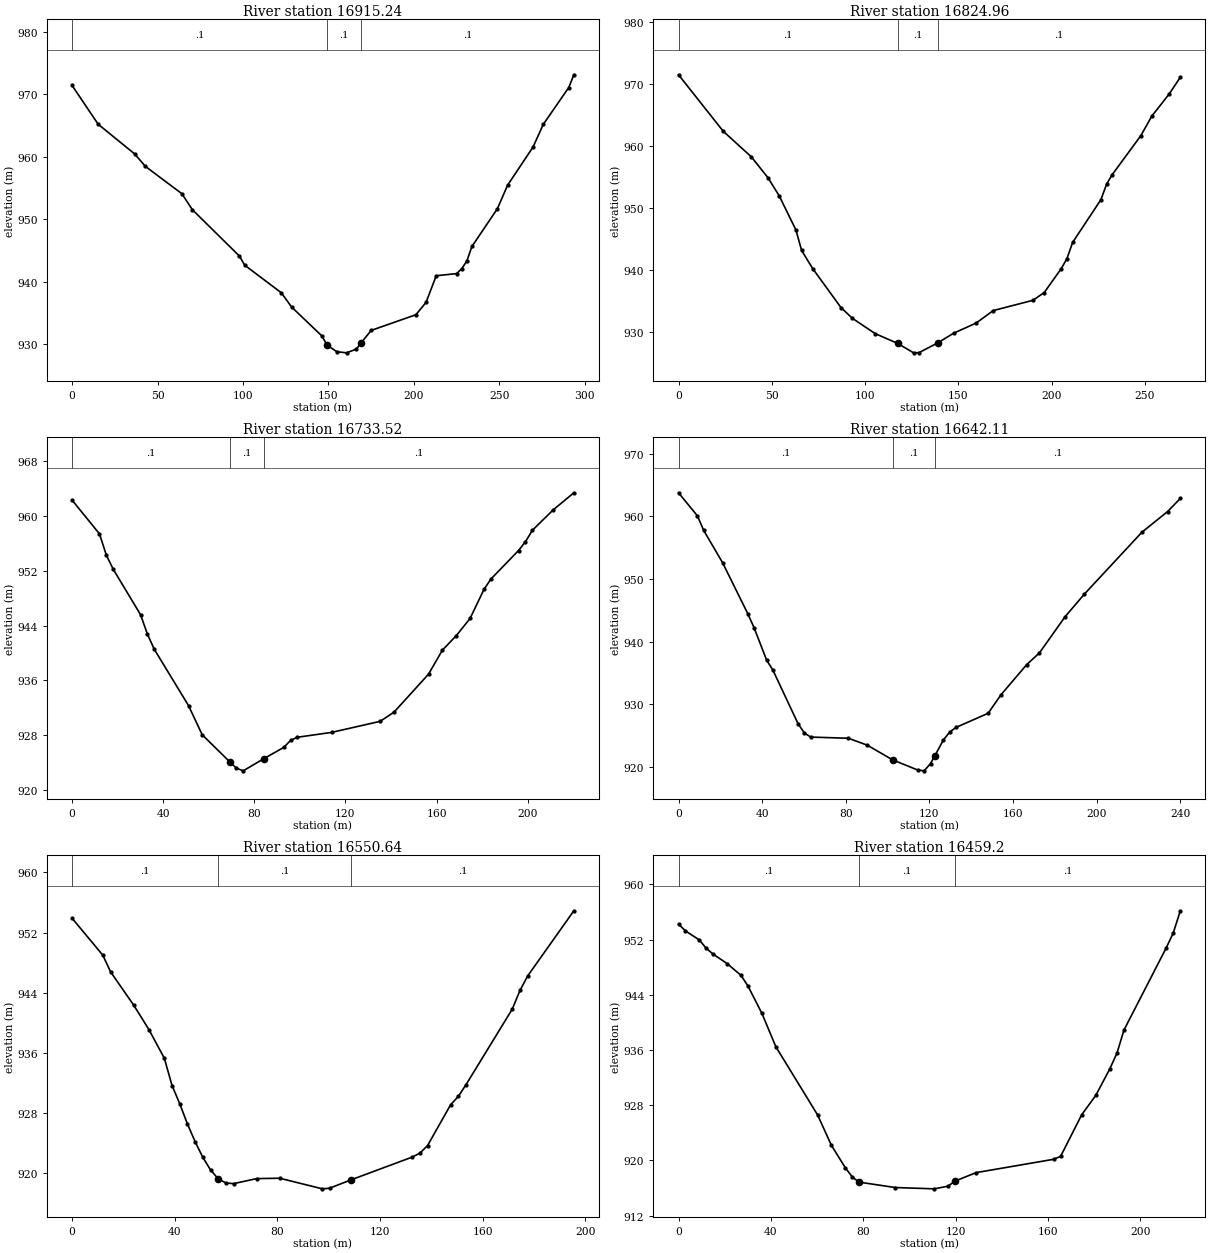
Type RM Length L Ch R = 1 ,16915.24,85.1,90.28,95.21
XS GIS Cut Line= 6
     642562.8766    4317648.0609     642468.0788    4317725.5287
     642450.2988    4317728.7037     642419.3847    4317735.2176
     642390.4024    4317737.4157     642299.6138    4317719.9232
#Sta/Elev= 30
       0  971.41    15.3  965.19   36.73  960.42   42.85  958.46   64.27  954.07
   70.39  951.51   97.94  944.08     101  942.63  122.42  938.21  128.45  935.93
  146.23  931.28   149.1  929.86  154.84  928.78  160.59  928.59  166.34  929.19
  168.94  930.12  174.99  932.18  201.15  934.69  207.11  936.67  213.08  940.94
  225.01  941.28  227.99  942.06  230.97  943.29  233.95  945.62  248.87  951.68
  254.83  955.44  269.74  961.56  275.71  965.18  290.62  971.08   293.6  973.12
#Mann= 3 , 0 , 0
       0      .1       0   149.1      .1       0  168.94      .1       0
Bank Sta=149.1,168.94
XS Rating Curve= 0 ,0
Exp/Cntr=0.3,0.1

Type RM Length L Ch R = 1 ,16824.96,91.14,91.44,88.26
XS GIS Cut Line= 6
     642558.6432    4317636.4192     642482.0935    4317651.1781
     642445.7244    4317647.0993     642428.8585    4317643.7249
     642419.2626    4317643.7731      642296.176    4317609.9608
#Sta/Elev= 30
       0  971.42   23.99   962.3   38.98   958.2   47.98   954.8   53.97  951.89
   62.97  946.36   65.97  943.09   71.96  940.14   87.11  933.86   93.21  932.14
  105.41  929.67  117.42   928.1  126.02  926.57  128.89   926.6  138.95  928.17
  147.43  929.73  159.59  931.38  168.71  933.39  189.98  935.04  196.06   936.3
  205.18  940.16  208.22  941.77  211.25  944.37  226.45  951.29  229.49  953.79
  232.53  955.33  247.72  961.55   253.8  964.79  262.92  968.28     269  971.02
#Mann= 3 , 0 , 0
       0      .1       0  117.42      .1       0  138.95      .1       0
Bank Sta=117.42,138.95
XS Rating Curve= 0 ,0
Exp/Cntr=0.3,0.1

Type RM Length L Ch R = 1 ,16733.52,107.58,91.41,80.24
XS GIS Cut Line= 5
     642521.5033    4317558.0726     642458.3569    4317557.4107
     642434.7722     4317553.383     642423.3174    4317555.9832
      642302.526    4317568.6857
#Sta/Elev= 30
       0  962.32   12.03  957.39   15.04  954.28   18.04  952.24   30.07  945.58
   33.08  942.74   36.09  940.53   51.12  932.31   57.14  928.04   69.13  924.13
   72.12  923.18   75.11  922.78   84.09  924.54   92.95  926.21   95.89  927.22
   98.82  927.68     114   928.4  135.26  930.01  141.33  931.35  156.51  936.91
  162.59  940.42  168.66  942.52  174.73  945.04  180.81  949.27  183.84  950.78
  195.99  954.96  199.02  956.23  202.06  957.91  211.17  960.88  220.28  963.39
#Mann= 3 , 0 , 0
       0      .1       0   69.13      .1       0   84.09      .1       0
Bank Sta=69.13,84.09
XS Rating Curve= 0 ,0
Exp/Cntr=0.3,0.1

Type RM Length L Ch R = 1 ,16642.11,86.29,91.47,91.98
XS GIS Cut Line= 3
     642495.1431    4317412.0521     642400.2582    4317475.9883
      642302.526    4317554.9274
#Sta/Elev= 30
       0  963.75    9.03  960.07   12.04  957.74   21.08  952.58   33.12  944.45
   36.13  942.22   42.15  937.03   45.16  935.43   57.21  926.86   60.22   925.4
   63.23  924.75    81.3  924.56   90.33  923.45  102.37  921.12  114.42  919.49
  117.48  919.36  120.54  920.51  122.62  921.75  126.67  924.28  129.74  925.55
   132.8   926.3  148.12  928.55  154.25   931.5  166.51   936.3  172.63  938.18
  184.89  943.95  194.08  947.55  221.66  957.45  233.92  960.74  240.05  962.85
#Mann= 3 , 0 , 0
       0      .1       0  102.37      .1       0  122.62      .1       0
Bank Sta=102.37,122.62
XS Rating Curve= 0 ,0
Exp/Cntr=0.3,0.1

Type RM Length L Ch R = 1 ,16550.64,95.38,91.44,92.12
XS GIS Cut Line= 6
     642445.4013     4317351.727     642374.0669     4317389.963
     642361.9608    4317396.7391     642351.7004    4317400.8534
     642344.5642    4317405.7914     642281.3593    4317456.5022
#Sta/Elev= 30
       0  953.91   11.99  948.99   14.99  946.79   23.98  942.37   29.98  939.09
   35.97  935.28   38.97  931.65   41.97  929.24   44.96  926.55   47.96  924.19
   50.96  922.11   53.96  920.44   56.95  919.25   59.95   918.7   62.95  918.61
   71.94  919.28   80.94  919.33   97.57  917.92  100.34     918  108.76  919.12
  132.55  922.14  135.55  922.66  138.55  923.67  147.56  929.11  150.56  930.22
  153.56  931.78  171.57  941.82  174.57   944.3  177.57  946.23  195.58   954.9
#Mann= 3 , 0 , 0
       0      .1       0   56.95      .1       0  108.76      .1       0
Bank Sta=56.95,108.76
XS Rating Curve= 0 ,0
Exp/Cntr=0.3,0.1

Type RM Length L Ch R = 1 ,16459.2 ,98.11,91.44,82.16
XS GIS Cut Line= 6
     642415.7856    4317261.7332      642339.036    4317303.3912
      642332.686    4317304.9787     642325.8068    4317309.4766
     642322.8899    4317314.4457     642226.0789    4317365.7146
#Sta/Elev= 30
       0  954.24    3.01  953.25    9.03  951.94   12.05  950.71   15.06  949.87
   21.08  948.51    27.1   946.8   30.11  945.25   36.14  941.29   42.16  936.47
   60.23  926.59   66.25  922.17   72.27  918.92   75.28  917.58   78.29  916.84
   93.87  916.06  110.76  915.87  116.72  916.25  119.78  916.99  128.93  918.22
  162.49  920.15  165.54  920.58   174.7  926.62   180.8  929.42   186.9  933.29
  189.95  935.53     193  938.89  211.31   950.8  214.36  952.97  217.41  956.17
#Mann= 3 , 0 , 0
       0      .1       0   78.29      .1       0  119.78      .1       0
Bank Sta=78.29,119.78
XS Rating Curve= 0 ,0
Exp/Cntr=0.3,0.1