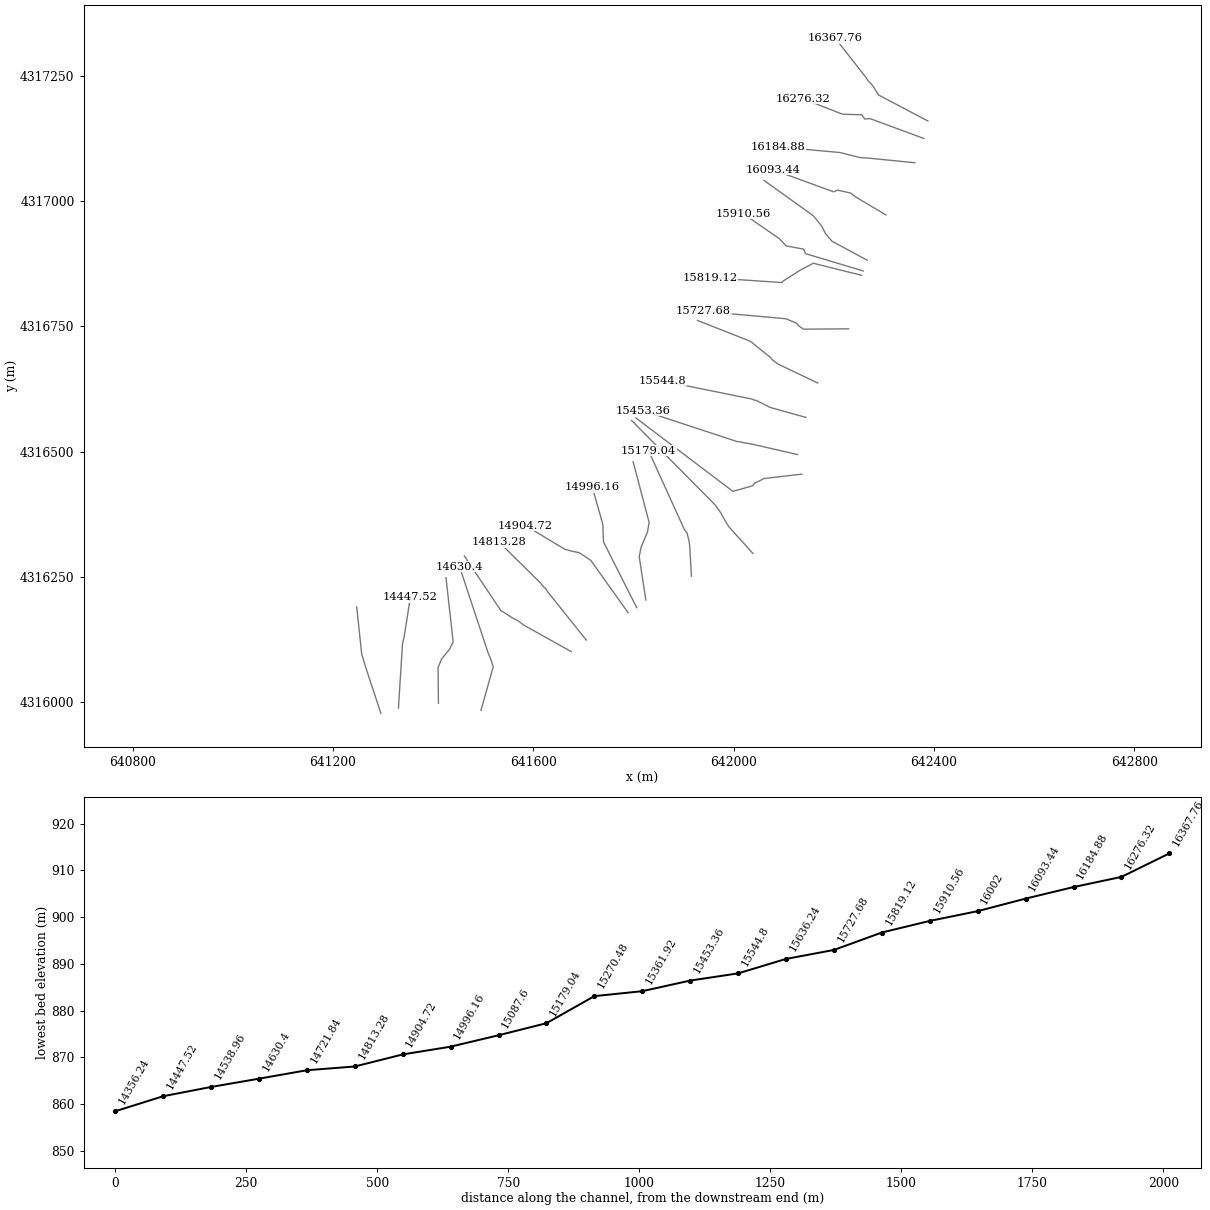
HEC-RAS study RedCreek.prj: RedCreek

--- RedCreek.g01 (geometry) --- (continued)

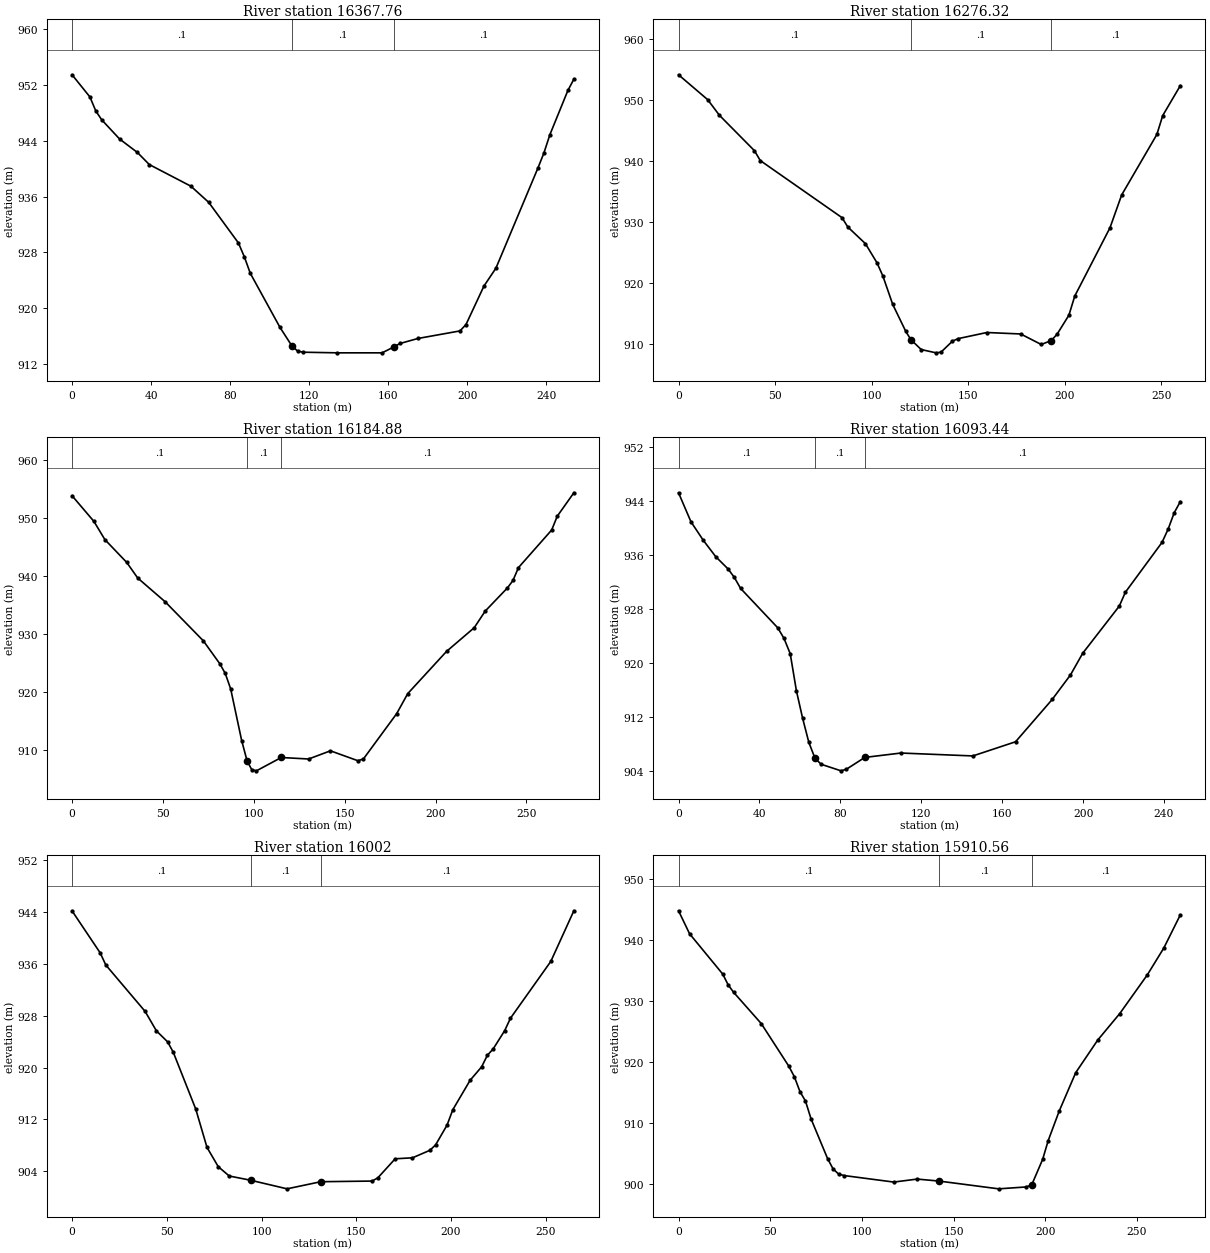
Type RM Length L Ch R = 1 ,16367.76,64.75,91.44,96.24
XS GIS Cut Line= 6
     642388.0043     4317160.133     642289.6221    4317212.0305
     642277.1939    4317231.4244     642269.1895     4317239.754
     642264.8468    4317246.4859     642203.0601    4317325.2333
#Sta/Elev= 30
       0  953.45    9.02  950.28   12.02  948.26   15.03  946.99   24.05  944.25
   33.07  942.32   39.08  940.59   60.13  937.49   69.14  935.18   84.18  929.36
   87.18  927.37   90.19  925.01  105.22  917.26  111.23  914.62  114.11  913.87
  116.99  913.71  134.27  913.62  156.89  913.62  162.93  914.48  165.96  914.96
  175.06  915.68  196.29  916.76  199.33  917.67  208.43  923.19  214.49  925.75
  235.72  940.08  238.76  942.24  241.79  944.87  250.89   951.2  253.92  952.82
#Mann= 3 , 0 , 0
       0      .1       0  111.23      .1       0  162.93      .1       0
Bank Sta=111.23,162.93
XS Rating Curve= 0 ,0
Exp/Cntr=0.3,0.1

Type RM Length L Ch R = 1 ,16276.32,80.78,91.44,96.96
XS GIS Cut Line= 6
     642380.0667    4317125.2079     642272.4349    4317164.9128
     642261.8516    4317164.1191     642256.0307    4317172.5858
     642217.4383    4317173.7385     642137.9725     4317204.583
#Sta/Elev= 30
       0  954.13   15.12  950.05   21.17   947.5   39.32   941.7   42.35  940.08
    84.7  930.73   87.72  929.19    96.8  926.48  102.85  923.32  105.87  921.17
  110.97  916.52  117.75  912.09  120.41  910.74  125.71  909.13  133.42  908.59
  135.99   908.7  141.93  910.51   144.9  910.92  159.75  911.92  177.26  911.68
   187.9  909.96  193.12   910.6  196.16  911.66  202.24  914.75  205.28  917.89
  223.51  929.06  229.58  934.45  247.81  944.35  250.85  947.45  259.97  952.35
#Mann= 3 , 0 , 0
       0      .1       0  120.41      .1       0  193.12      .1       0
Bank Sta=120.41,193.12
XS Rating Curve= 0 ,0
Exp/Cntr=0.3,0.1

Type RM Length L Ch R = 1 ,16184.88,84.37,91.44,81.68
XS GIS Cut Line= 5
     642361.8105     4317076.789     642265.9549    4317086.3528
      642253.205    4317086.9747     642212.3574    4317097.1866
     642087.9662    4317108.5391
#Sta/Elev= 30
       0  953.83   12.04   949.4   18.06  946.27    30.1  942.33   36.12  939.65
   51.18  935.57   72.25  928.82   81.28  924.88   84.29  923.21    87.3  920.51
   93.32  911.64   96.33   908.1   98.88  906.62  101.44  906.42  115.11  908.72
  130.15  908.46  142.18  909.87  157.29  908.16  160.34  908.48  178.62  916.28
  184.71  919.73  206.04     927  221.27  931.08  227.36  933.96  239.55  937.94
   242.6  939.23  245.64  941.45  263.92  947.93  266.97   950.3  276.11  954.34
#Mann= 3 , 0 , 0
       0      .1       0   96.33      .1       0  115.11      .1       0
Bank Sta=96.33,115.11
XS Rating Curve= 0 ,0
Exp/Cntr=0.3,0.1

Type RM Length L Ch R = 1 ,16093.44,97.19,91.44,72.69
XS GIS Cut Line= 6
     642304.1312    4316972.5959      642243.463    4317008.6132
     642233.7744    4317016.2669     642207.4796     4317022.107
     642199.8066    4317018.6674      642077.912    4317063.0836
#Sta/Elev= 30
       0  945.18    6.14  940.88   12.27  938.12   18.41   935.7   24.54  933.87
   27.61  932.62   30.68     931   49.08  925.15   52.15  923.58   55.22  921.32
   58.28  915.81   61.35  911.74   64.42  908.17   67.49  905.79   70.55  904.92
   80.34  903.95      83  904.19   92.09  905.94  109.94  906.59   145.5  906.16
  166.62  908.26  184.72  914.53  193.77  918.17  199.81  921.38  217.91  928.38
  220.93  930.44  239.03  937.82  242.05  939.79  245.06  942.22  248.08  943.87
#Mann= 3 , 0 , 0
       0      .1       0   67.49      .1       0   92.09      .1       0
Bank Sta=67.49,92.09
XS Rating Curve= 0 ,0
Exp/Cntr=0.3,0.1

Type RM Length L Ch R = 1 ,16002   ,55.13,91.44,89.24
XS GIS Cut Line= 6
     642266.8249    4316882.1082     642196.3155    4316920.1423
     642183.5017    4316935.4007     642176.1121    4316949.8756
     642159.3584    4316970.7888     642060.4494    4317041.6523
#Sta/Elev= 30
       0  944.18   14.84   937.7    17.8  935.83   38.57  928.66   44.51  925.66
   50.44  923.96   53.41  922.36   65.28  913.58   71.21  907.67   77.15  904.69
   82.96  903.25   94.35  902.59  113.47  901.27  131.25  902.37  158.37  902.47
  161.41  902.98  170.53  905.91  179.66  906.06  188.78  907.21  191.83  908.04
  197.91  911.11  200.95  913.49  210.08  918.03  216.16  920.11   219.2   921.9
  222.24  922.87  228.33   925.7  231.37  927.61  252.66  936.38  264.83   944.2
#Mann= 3 , 0 , 0
       0      .1       0   94.35      .1       0  131.25      .1       0
Bank Sta=94.35,131.25
XS Rating Curve= 0 ,0
Exp/Cntr=0.3,0.1

Type RM Length L Ch R = 1 ,15910.56,43.18,91.44,104.57
XS GIS Cut Line= 6
     642258.8873    4316860.6769      642143.563    4316895.2986
     642139.8588    4316904.2944     642105.0448    4316910.6577
      642091.014    4316925.3162     642019.1744    4316974.9772
#Sta/Elev= 30
       0  944.78    6.02  941.01   24.08  934.41   27.09  932.62    30.1  931.39
   45.15  926.27    60.2  919.27   63.21  917.54   66.23  915.12   69.24  913.58
   72.25  910.67   81.28  904.15   84.29  902.45    87.3   901.6   90.31  901.36
   117.4  900.29  130.14  900.78  141.93  900.46  174.59  899.18   189.6  899.49
   192.6  899.81  198.61  904.02  201.61  907.08  207.62  911.93  216.63  918.23
  228.64  923.58  240.65  927.92  255.67  934.26  264.68  938.67  273.69  944.11
#Mann= 3 , 0 , 0
       0      .1       0  141.93      .1       0   192.6      .1       0
Bank Sta=141.93,192.6
XS Rating Curve= 0 ,0
Exp/Cntr=0.3,0.1

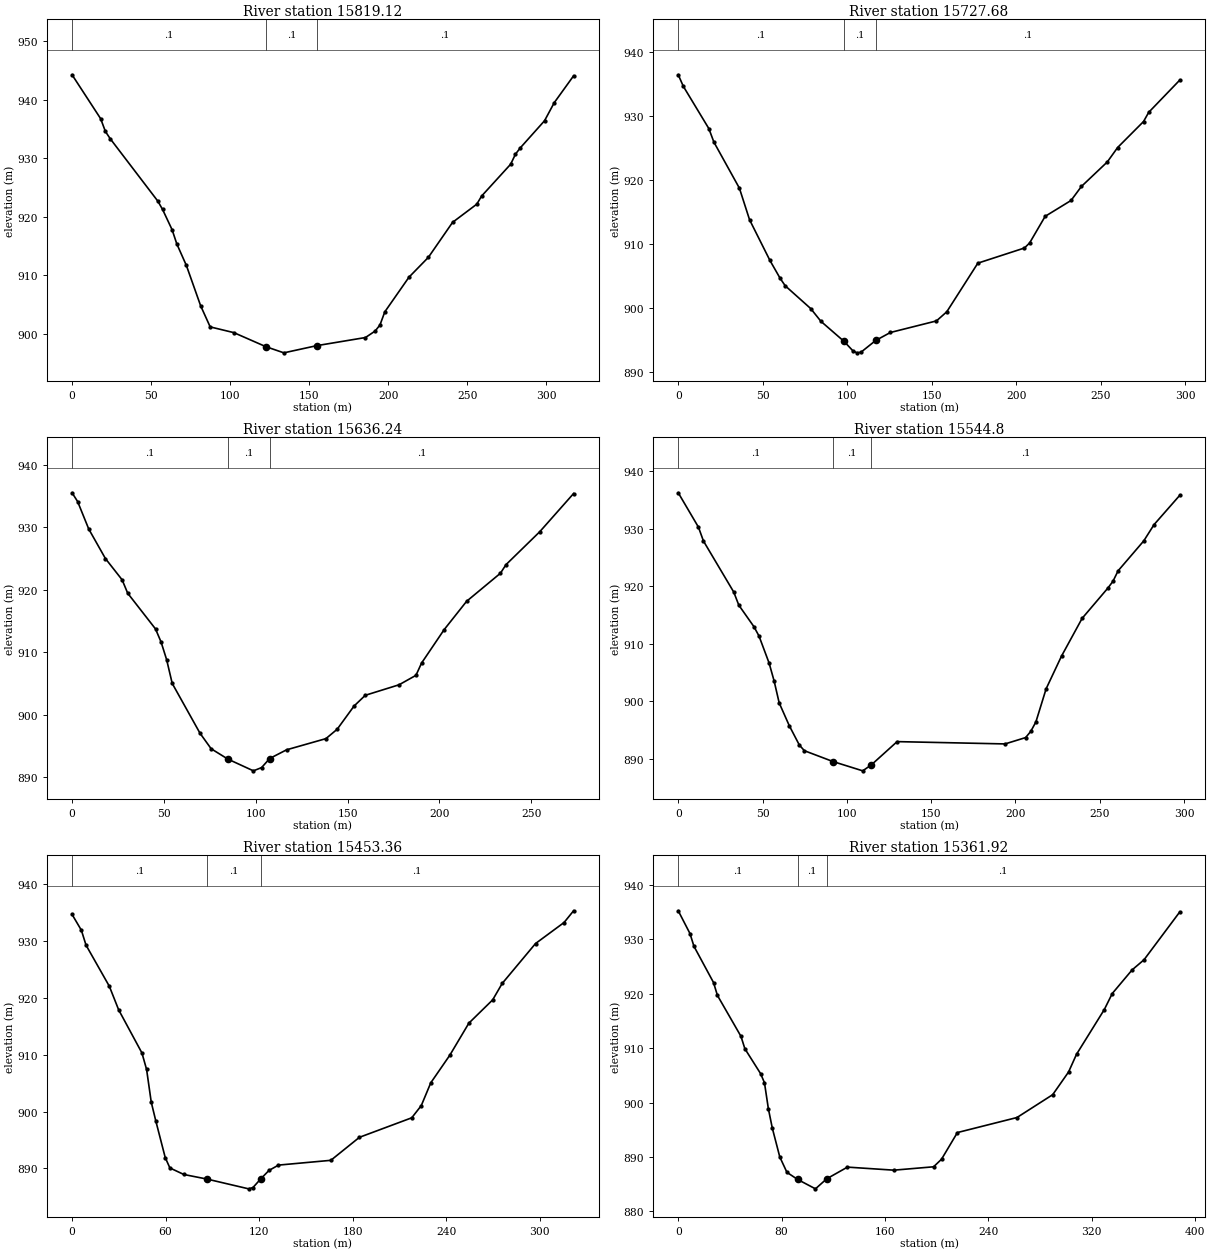
Type RM Length L Ch R = 1 ,15819.12,137.21,91.44,75.39
XS GIS Cut Line= 6
     642255.7123    4316851.9457     642159.2131    4316876.0545
     642133.4955    4316862.5607     642098.4117    4316840.1769
     642096.9286     4316837.486      641953.293    4316847.1832
#Sta/Elev= 30
       0   944.3   18.08  936.79    21.1   934.6   24.11  933.37   54.25  922.68
   57.27  921.25    63.3  917.78   66.31  915.33   72.34  911.66   81.38  904.75
   87.41  901.14  102.37  900.16   122.7  897.75  134.03   896.7  154.84  897.93
  185.66  899.32  191.79  900.43  194.85  901.47  197.91  903.72  213.23  909.66
  225.48  913.05   240.8  919.04  256.11  922.15  259.17  923.54  277.55  928.99
  280.61  930.72  283.68   931.8  298.99  936.43  305.12  939.52  317.37  944.12
#Mann= 3 , 0 , 0
       0      .1       0   122.7      .1       0  154.84      .1       0
Bank Sta=122.7,154.84
XS Rating Curve= 0 ,0
Exp/Cntr=0.3,0.1

Type RM Length L Ch R = 1 ,15727.68,89.99,91.44,80.91
XS GIS Cut Line= 6
     642229.6244    4316745.1199     642139.1576    4316744.4108
     642128.8389    4316752.0837     642126.0514    4316755.9891
     642104.7128    4316765.1996      641939.905     4316780.045
#Sta/Elev= 30
       0  936.44    3.02  934.63   18.09  928.04   21.11  925.91   36.19  918.72
   42.22  913.77   54.28  907.41   60.31  904.62   63.33  903.45   78.41  899.89
   84.44   897.9   98.18  894.75  103.33   893.3  105.73  892.97  108.13  893.06
  116.84   894.9  125.56  896.15  152.82  897.96  158.95  899.39  177.33  906.99
  204.91  909.36  207.98  910.15  217.17  914.31  232.49  916.79  238.62  918.98
  253.94  922.81  260.07  925.07  275.39  929.13  278.46  930.57  296.84  935.61
#Mann= 3 , 0 , 0
       0      .1       0   98.18      .1       0  116.84      .1       0
Bank Sta=98.18,116.84
XS Rating Curve= 0 ,0
Exp/Cntr=0.3,0.1

Type RM Length L Ch R = 1 ,15636.24,86.47,91.44,101.4
XS GIS Cut Line= 6
     642167.9763    4316636.9051     642088.6971     4316674.715
     642077.7569    4316682.8175     642074.0127    4316687.5473
     642033.4927    4316720.2303     641927.9988    4316761.7887
#Sta/Elev= 30
       0  935.51    3.03  934.11    9.09  929.71   18.17  924.99   27.26  921.59
   30.29  919.45   45.43  913.74   48.46  911.65   51.49  908.82   54.52  905.03
   69.66  897.06   75.72  894.58   84.81  892.93   98.72  891.05  103.18  891.57
  107.58  893.02  116.76  894.41   138.2   896.2  144.32   897.7  153.51  901.41
  159.63  903.13  178.02  904.81  187.21  906.32  190.28  908.29  202.54  913.62
  214.79  918.16  233.18  922.64  236.24  924.02  254.63  929.29  273.02  935.39
#Mann= 3 , 0 , 0
       0      .1       0   84.81      .1       0  107.58      .1       0
Bank Sta=84.81,107.58
XS Rating Curve= 0 ,0
Exp/Cntr=0.3,0.1

Type RM Length L Ch R = 1 ,15544.8 ,83.07,91.44,93.8
XS GIS Cut Line= 6
     642144.6929    4316568.1133     642072.6016    4316588.2314
     642044.9262    4316602.4425      642043.709    4316601.8839
     642037.1153    4316604.7077      641857.884    4316641.1385
#Sta/Elev= 30
       0  936.21   11.98  930.25   14.97  927.83   32.93  918.98   35.93  916.71
   44.91  912.97    47.9  911.36   53.89  906.67   56.88  903.55   59.88  899.75
   65.86   895.8   71.85  892.43   74.85  891.45   91.82  889.57  109.43  887.96
   114.6  889.01  129.84  893.03  193.86  892.63  206.05  893.73   209.1   894.8
  212.15  896.44  218.24  902.21  227.39  907.89  239.58  914.42  254.82  919.66
  257.87  920.85  260.92  922.67  276.16  927.87  282.26  930.69   297.5  935.77
#Mann= 3 , 0 , 0
       0      .1       0   91.82      .1       0   114.6      .1       0
Bank Sta=91.82,114.6
XS Rating Curve= 0 ,0
Exp/Cntr=0.3,0.1

Type RM Length L Ch R = 1 ,15453.36,74.21,91.44,98.64
XS GIS Cut Line= 6
     642127.7596    4316494.0299     642034.5081    4316515.3936
     642019.7759     4316517.629     642011.8154    4316519.6654
     642007.3091    4316519.8444     641818.7256    4316581.8717
#Sta/Elev= 30
       0  934.63    5.98  931.85    8.97  929.23   23.92  922.01    29.9  917.87
   44.84  910.29   47.83  907.39   50.82  901.64   53.81  898.27   59.79  891.91
   62.78  890.09   71.75  888.94    86.7  888.13  113.31  886.42  116.05  886.64
  121.04  888.16  126.35  889.65  132.46  890.59  166.05  891.43  184.38  895.47
  217.97   898.9  224.08  901.04  230.19  905.05  242.41   909.9  254.63  915.53
   269.9  919.62     276   922.5  297.38  929.51  315.71  933.21  321.82  935.27
#Mann= 3 , 0 , 0
       0      .1       0    86.7      .1       0  121.04      .1       0
Bank Sta=86.7,121.04
XS Rating Curve= 0 ,0
Exp/Cntr=0.3,0.1

Type RM Length L Ch R = 1 ,15361.92,133.35,91.44,55.25
XS GIS Cut Line= 6
     642136.2263    4316454.8714     642060.9083    4316446.1309
     642041.0645    4316436.3413     642038.3393    4316431.7388
     641998.5194    4316420.5721     641804.9673     4316567.055
#Sta/Elev= 30
       0  935.23     9.1  931.04   12.13  928.72    27.3  922.05   30.33  919.68
   48.53  912.17   51.56  909.89   63.69  905.33   66.72  903.65   69.76  898.85
   72.79  895.31   78.59     890   84.12  887.18   92.42  885.87  106.19  884.15
  114.88  885.99  130.93  888.14  166.87  887.58   197.6   888.2  203.74  889.59
  216.03  894.49  262.12  897.25  289.77  901.45  302.06  905.62  308.21  908.87
  329.72  917.09  335.86  920.03  351.22  924.37  360.44  926.23   388.1  935.02
#Mann= 3 , 0 , 0
       0      .1       0   92.42      .1       0  114.88      .1       0
Bank Sta=92.42,114.88
XS Rating Curve= 0 ,0
Exp/Cntr=0.3,0.1

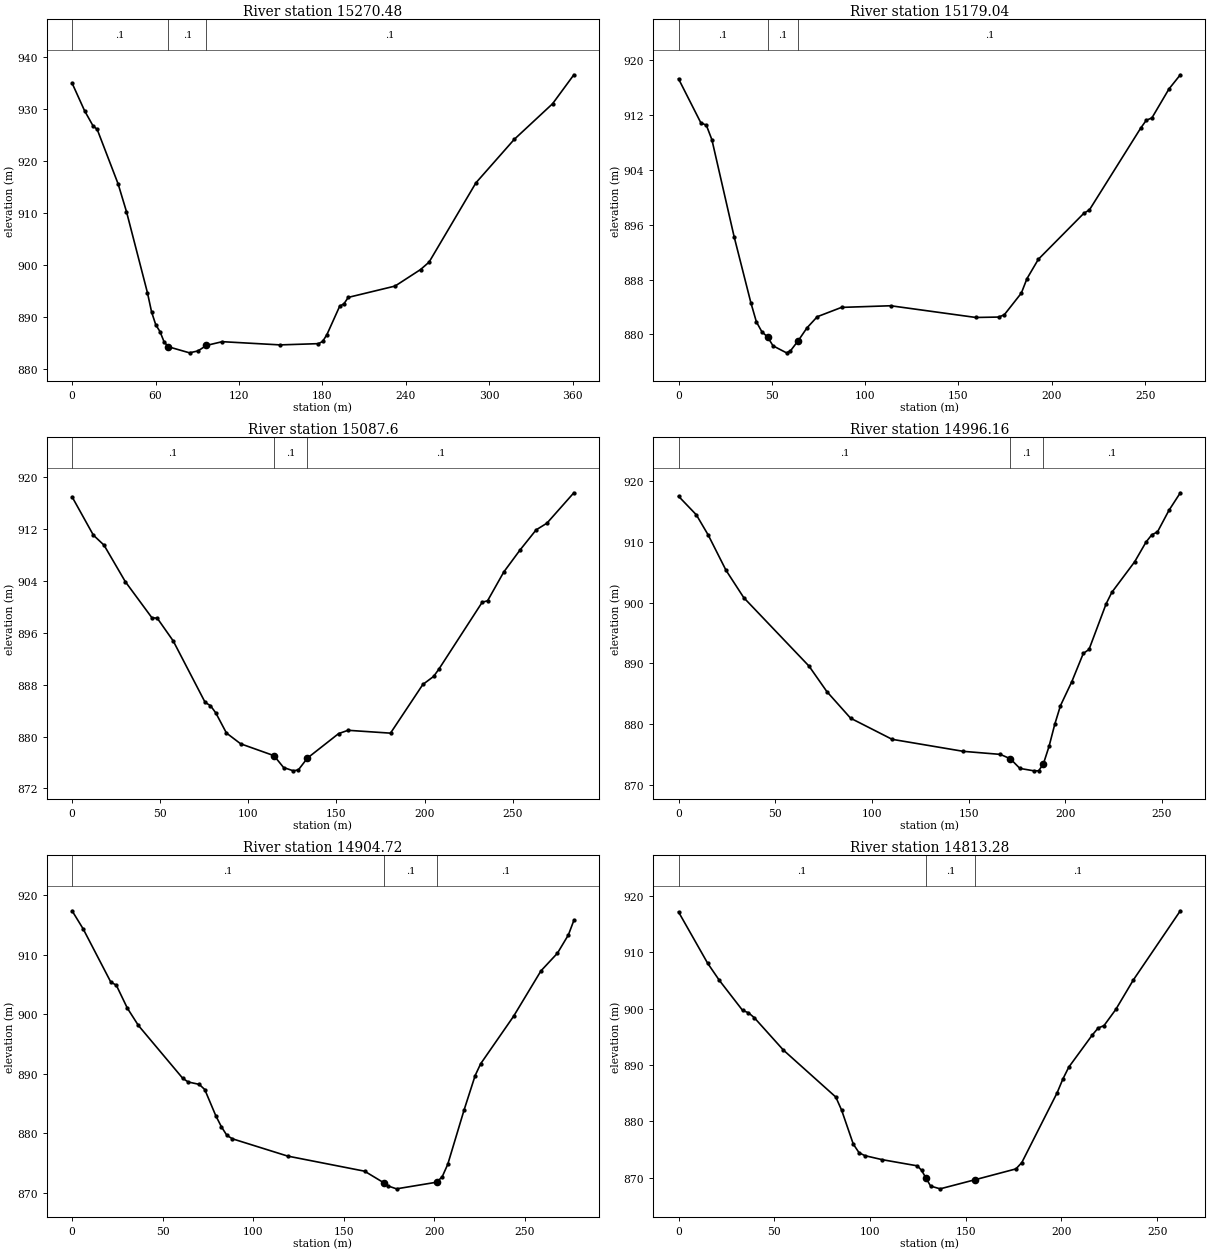
Type RM Length L Ch R = 1 ,15270.48,99.01,91.44,78.98
XS GIS Cut Line= 6
     642038.4978    4316296.5886     641990.1601    4316350.2482
     641977.5846    4316371.1508      641975.139    4316376.3513
     641964.0265    4316392.5438      641796.139    4316562.2308
#Sta/Elev= 30
       0  935.05    9.03   929.7   15.05  926.82   18.06  926.13    33.1  915.63
   39.12  910.28   54.17  894.68   57.17  890.95   60.18  888.48   63.19  887.19
    66.2  885.17   69.21  884.26   84.42  883.09   90.52  883.46   96.61  884.52
  107.97  885.24  149.54  884.62  177.09  884.86  180.15  885.29  183.21  886.61
  192.39  892.08  195.45  892.54  198.51  893.77  232.17  895.95  250.53  899.14
  256.65  900.57  290.32  915.84  317.86  924.21   345.4  931.07  360.71  936.65
#Mann= 3 , 0 , 0
       0      .1       0   69.21      .1       0   96.61      .1       0
Bank Sta=69.21,96.61
XS Rating Curve= 0 ,0
Exp/Cntr=0.3,0.1

Type RM Length L Ch R = 1 ,15179.04,100.24,91.44,77.54
XS GIS Cut Line= 6
     641915.7309    4316251.0801     641912.3799    4316310.9416
     641910.7834    4316322.5834     641906.8146    4316337.6647
     641901.7875    4316344.0147     641830.0057    4316501.9056
#Sta/Elev= 30
       0  917.28   11.92  910.88    14.9  910.51   17.87   908.4   29.79  894.24
   38.73  884.64   41.71  881.82   44.69  880.36   47.67  879.63   50.64  878.32
   57.85   877.3   59.97  877.59    64.2   879.1   68.78  880.93   74.32  882.57
   87.32  883.93  113.67  884.17  159.31  882.46  171.49  882.52  174.53  882.85
  183.66  886.01   186.7  888.13  192.79  890.95  217.13  897.65  220.17  898.16
  247.56  910.06   250.6  911.23  253.64  911.58  262.77   915.8  268.86  917.87
#Mann= 3 , 0 , 0
       0      .1       0   47.67      .1       0    64.2      .1       0
Bank Sta=47.67,64.2
XS Rating Curve= 0 ,0
Exp/Cntr=0.3,0.1

Type RM Length L Ch R = 1 ,15087.6 ,73.9,91.44,100.27
XS GIS Cut Line= 6
      641824.714     4316203.455     641811.4939    4316290.0352
     641815.0922    4316308.4502      641828.103    4316339.9336
      641831.298    4316358.3904      641799.314    4316479.6806
#Sta/Elev= 30
       0  916.97   12.08  911.06   18.12  909.52    30.2  903.89    45.3  898.32
   48.32  898.26   57.38  894.75    75.5  885.27   78.52  884.77   81.54  883.65
   87.58  880.55   95.63  878.89  114.54  877.06  120.01  875.23  125.57  874.72
  128.39  874.87  133.54  876.69  151.22  880.46  156.57  880.97  180.66  880.53
  199.02  888.04  205.14  889.28   208.2  890.44  232.67  900.71  235.73  900.94
  244.91  905.37  254.09  908.75  263.27  911.87  269.39   912.9  284.68  917.59
#Mann= 3 , 0 , 0
       0      .1       0  114.54      .1       0  133.54      .1       0
Bank Sta=114.54,133.54
XS Rating Curve= 0 ,0
Exp/Cntr=0.3,0.1

Type RM Length L Ch R = 1 ,14996.16,46.55,91.44,106.01
XS GIS Cut Line= 6
     641806.6165    4316188.1092     641740.1665     4316319.565
     641739.1743    4316341.3931      641739.219    4316351.2515
     641737.1179    4316360.7065     641717.8222    4316428.8805
#Sta/Elev= 30
       0   917.5    9.21  914.44   15.34  911.12   24.55  905.31   33.76  900.79
   67.51  889.52   76.72  885.33   88.99  880.95  110.47  877.47   147.3  875.49
  166.42  874.99  171.61  874.27  176.54  872.68  183.85  872.28  186.27  872.29
  188.69  873.41  191.64  876.31   194.6  879.95  197.55  883.02  203.45  886.99
  209.36  891.62  212.31  892.27  221.17  899.79  224.12  901.68  235.93  906.71
  241.83  909.97  244.78  911.15  247.73  911.63  253.64  915.17  259.54  918.07
#Mann= 3 , 0 , 0
       0      .1       0  171.61      .1       0  188.69      .1       0
Bank Sta=171.61,188.69
XS Rating Curve= 0 ,0
Exp/Cntr=0.3,0.1

Type RM Length L Ch R = 1 ,14904.72,106.79,91.44,83.5
XS GIS Cut Line= 6
      641789.154    4316178.3196     641714.7499    4316282.7878
     641691.4665    4316298.1337     641675.5246    4316301.3466
     641662.2059    4316305.2767     641584.3661    4316352.1512
#Sta/Elev= 30
       0  917.41    6.11  914.37   21.38  905.42   24.43  904.89   30.54  901.02
   36.64  898.11   61.07  889.24   64.13   888.6   70.24   888.2   73.29  887.33
    79.4  882.91   82.45  881.08    85.5  879.62   88.56  879.04  119.09  876.13
  161.56  873.59   172.4   871.6  174.67  871.09   179.2  870.62  201.43  871.74
  204.46  872.67  207.49  874.74  216.58  883.95  222.64  889.69  225.66  891.66
  243.84  899.65  258.98   907.3  268.07  910.27  274.13  913.35  277.15  915.79
#Mann= 3 , 0 , 0
       0      .1       0   172.4      .1       0  201.43      .1       0
Bank Sta=172.4,201.43
XS Rating Curve= 0 ,0
Exp/Cntr=0.3,0.1

Type RM Length L Ch R = 1 ,14813.28,79.53,91.44,92.75
XS GIS Cut Line= 6
     641705.8101    4316123.5507     641627.8517    4316220.9546
     641625.9836    4316224.9898     641618.6016    4316231.6336
     641614.9224    4316236.9531     641531.9785    4316318.8136
#Sta/Elev= 30
       0  917.18   15.21  908.08    21.3  905.05   33.47  899.71   36.52  899.29
   39.56  898.42   54.77  892.67   82.16  884.33    85.2     882   91.29  875.98
   94.33  874.44   97.37  873.93   106.5  873.21  124.76  872.12  126.98  871.32
  129.21  869.98  131.69  868.53  136.66  868.04  154.81  869.65  176.27  871.58
  179.34  872.71  197.74  885.06  200.81  887.55  203.87  889.64  216.14  895.34
  219.21  896.58  222.27  897.01  228.41  899.87  237.61  905.12  262.14  917.39
#Mann= 3 , 0 , 0
       0      .1       0  129.21      .1       0  154.81      .1       0
Bank Sta=129.21,154.81
XS Rating Curve= 0 ,0
Exp/Cntr=0.3,0.1

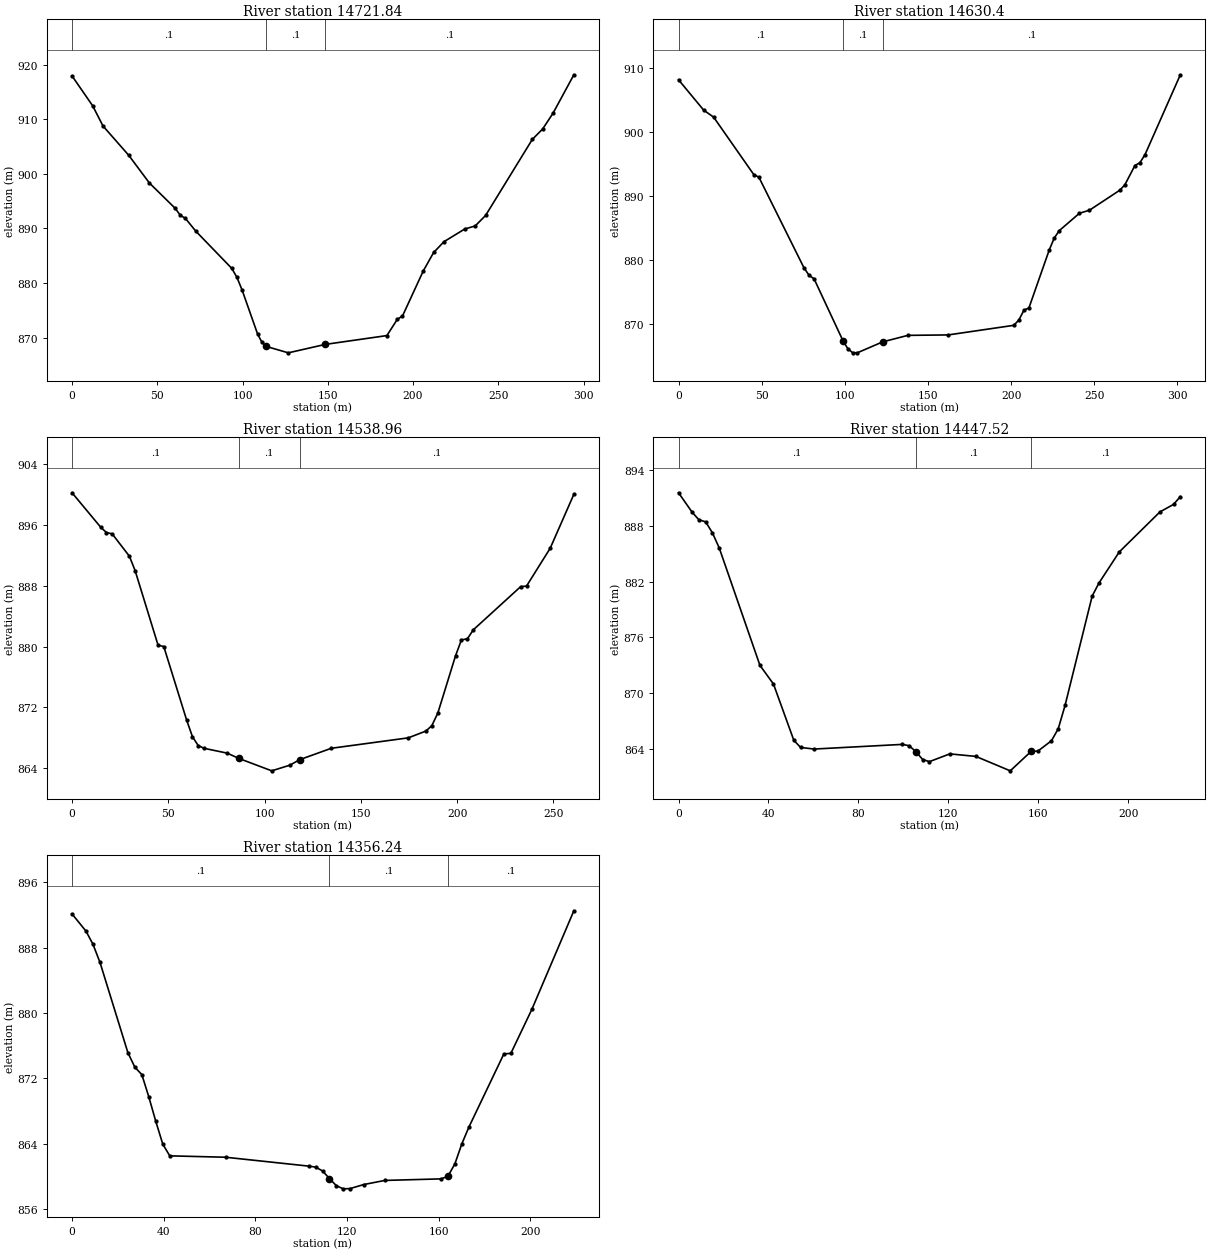
Type RM Length L Ch R = 1 ,14721.84,124.36,91.44,73.4
XS GIS Cut Line= 6
     641675.6475    4316100.5319     641580.6315     4316153.565
     641570.7928    4316161.3456     641560.9188    4316166.0757
     641534.8116    4316182.8677     641462.1283     4316291.826
#Sta/Elev= 30
       0  917.91   12.09  912.45   18.14  908.76   33.25  903.39   45.34  898.33
   60.45   893.7   63.48  892.42    66.5  891.84   72.54  889.52    93.7  882.69
   96.72  881.04   99.75  878.72  108.81  870.69  111.32  869.19  113.83  868.42
  126.83  867.24  148.61  868.79  184.67   870.4  190.76  873.37  193.81  873.98
  205.99  882.22  212.09  885.61  218.18  887.59  230.36  889.91  236.45  890.46
  242.55  892.38  269.96   906.3  276.05  908.22  282.14  911.11  294.33  918.13
#Mann= 3 , 0 , 0
       0      .1       0  113.83      .1       0  148.61      .1       0
Bank Sta=113.83,148.61
XS Rating Curve= 0 ,0
Exp/Cntr=0.3,0.1

Type RM Length L Ch R = 1 ,14630.4 ,107.07,91.44,68.16
XS GIS Cut Line= 5
     641495.4659    4315983.0567     641519.9138     4316070.274
     641514.6283    4316086.3044     641509.8628    4316097.5683
     641452.6033    4316270.3948
#Sta/Elev= 30
       0   908.1    15.1  903.36   21.14  902.25   45.29  893.27   48.31  892.88
   75.48  878.69    78.5  877.55   81.52  876.99   99.02  867.24  101.83  866.07
  104.65  865.46  107.46  865.43  122.72  867.14   137.9  868.16  162.17  868.23
  201.62  869.73  204.65  870.56  207.69  872.08  210.72  872.46  222.86  881.46
  225.89  883.35  228.93  884.52  241.07  887.24  247.13  887.72  265.34  890.84
  268.38  891.68  274.44   894.7  277.48  895.15  280.51   896.4  301.75  908.88
#Mann= 3 , 0 , 0
       0      .1       0   99.02      .1       0  122.72      .1       0
Bank Sta=99.02,122.72
XS Rating Curve= 0 ,0
Exp/Cntr=0.3,0.1

Type RM Length L Ch R = 1 ,14538.96,78.59,91.44,97.83
XS GIS Cut Line= 6
     641410.5345    4315997.3442     641409.7755    4316068.7919
     641416.8143    4316085.6067     641432.9009    4316105.5034
     641439.9026    4316119.9362     641425.6157    4316248.1697
#Sta/Elev= 30
       0  900.26   14.89  895.72   17.86  895.03   20.84  894.85   29.77  891.91
   32.75  890.01   44.66   880.2   47.63  880.02   59.54  870.31   62.52  868.15
    65.5  866.99   68.47  866.63   80.57  865.99   86.64  865.29  103.69  863.66
  113.15  864.41   118.2  865.13  134.64  866.63  174.57     868  183.79   868.9
  186.86  869.62  189.94  871.26  199.15  878.81  202.22   880.9   205.3  881.04
  208.37  882.22  232.94   887.9  236.02  887.98   248.3  892.96  260.59  900.06
#Mann= 3 , 0 , 0
       0      .1       0   86.64      .1       0   118.2      .1       0
Bank Sta=86.64,118.2
XS Rating Curve= 0 ,0
Exp/Cntr=0.3,0.1

Type RM Length L Ch R = 1 ,14447.52,85.24,91.28,94.23
XS GIS Cut Line= 6
     641330.6853      4315987.72     641338.7894    4316117.2042
     641342.0475    4316129.4871     641342.9703    4316137.1155
     641343.7283    4316140.7541     641354.4978     4316209.309
#Sta/Elev= 30
       0  891.54    6.03  889.46    9.05  888.64   12.07  888.42   15.09  887.23
    18.1  885.62   36.21  873.01   42.24     871   51.29  864.96   54.31  864.19
   60.34  864.02   99.57  864.52  102.58  864.38   105.6  863.74  108.62  862.89
  111.63  862.67  120.69   863.5  132.28  863.23  147.57  861.68  156.86  863.77
  159.88   863.8  165.91  864.91  168.93   866.2  171.95   868.7  184.02  880.45
  187.04  881.85  196.09  885.19  214.19  889.49  220.22  890.29  223.24  891.13
#Mann= 3 , 0 , 0
       0      .1       0   105.6      .1       0  156.86      .1       0
Bank Sta=105.6,156.86
XS Rating Curve= 0 ,0
Exp/Cntr=0.3,0.1

Type RM Length L Ch R = 1 ,14356.24,59.81,91.6,98.08
XS GIS Cut Line= 4
     641295.6279    4315977.1366     641266.0212    4316066.7456
     641257.2928     4316095.321     641247.3413    4316189.4652
#Sta/Elev= 30
       0  892.13    6.09  890.02    9.13  888.41   12.18   886.2   24.35  875.15
    27.4  873.36   30.44  872.46   33.49  869.72   36.53  866.73   39.58  863.94
   42.62  862.51   66.97  862.34  103.34  861.25  106.32  861.13  109.31  860.65
   112.3  859.73  115.29  858.86  118.28  858.47  121.26   858.5  127.31     859
  136.47   859.5   160.9  859.69  163.95  859.99  167.01  861.53  170.06  863.99
  173.11  866.02  188.38  874.99  191.44  875.06   200.6  880.45  218.92  892.52
#Mann= 3 , 0 , 0
       0      .1       0   112.3      .1       0  163.95      .1       0
Bank Sta=112.3,163.95
XS Rating Curve= 0 ,0
Exp/Cntr=0.3,0.1