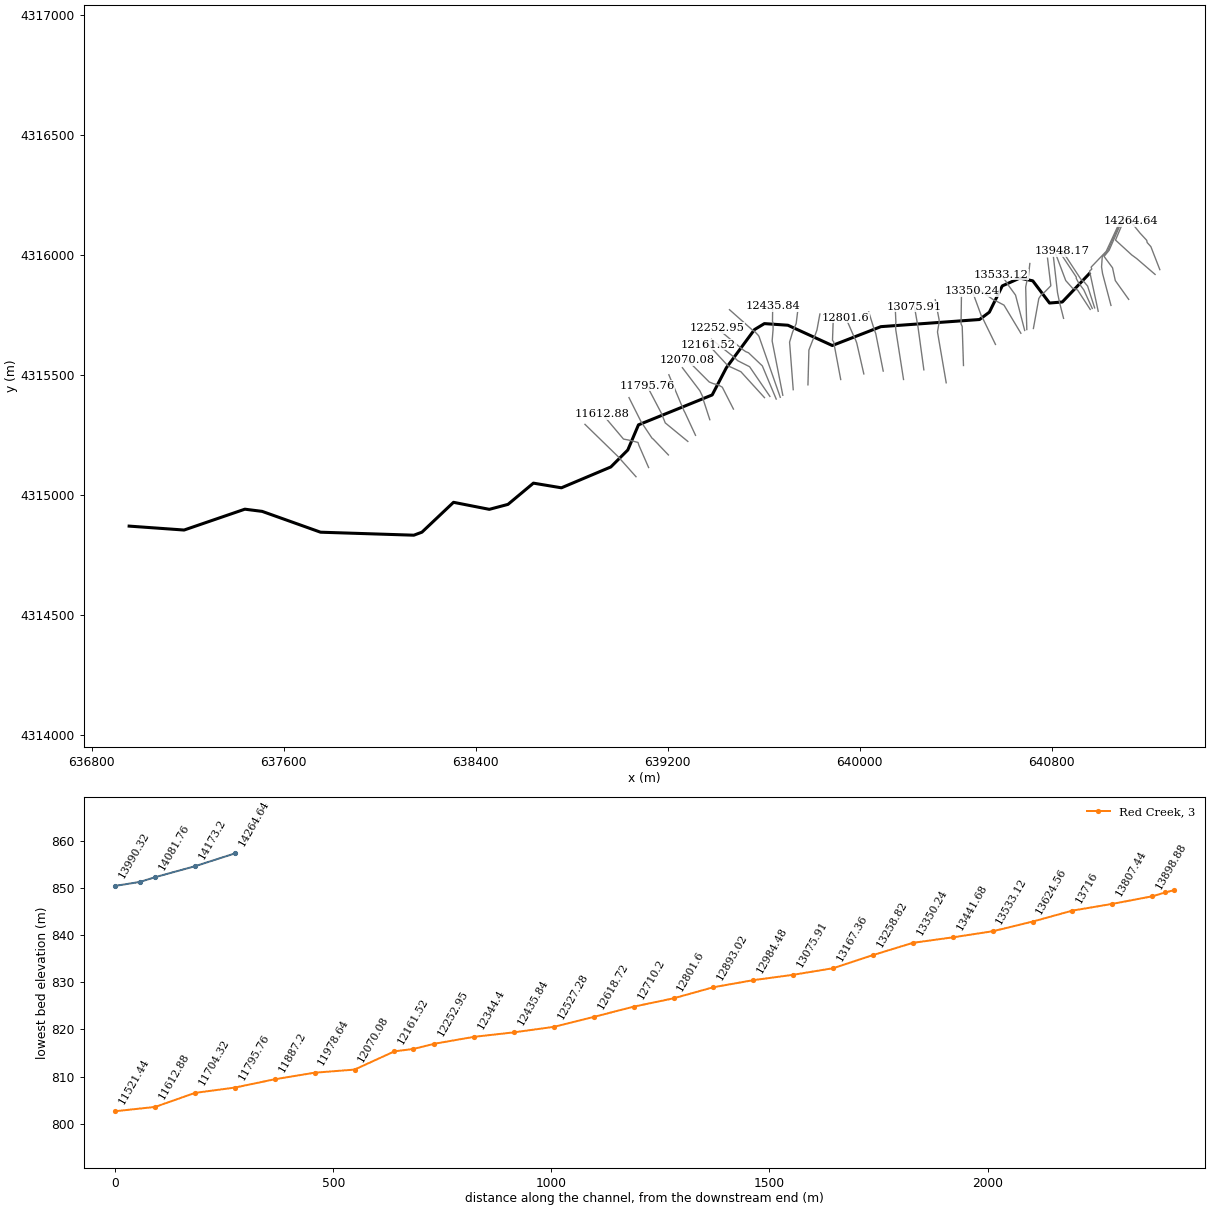
HEC-RAS study RedCreek.prj: RedCreek

--- RedCreek.g01 (geometry) --- (continued)

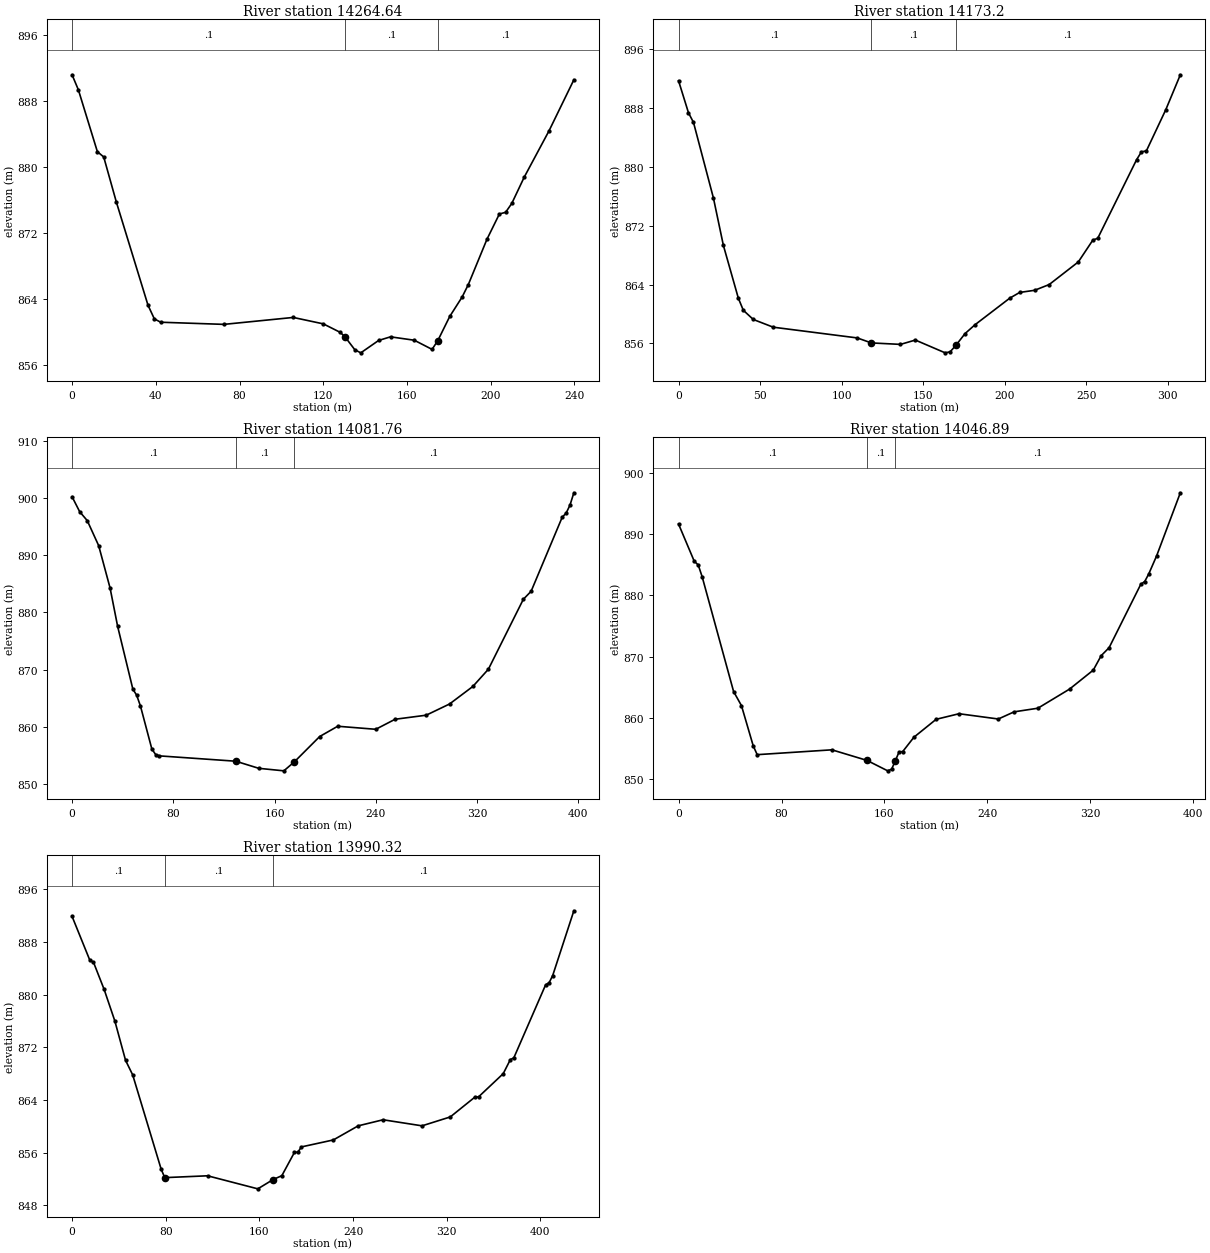
Type RM Length L Ch R = 1 ,14264.64,77.54,91.44,91.94
XS GIS Cut Line= 6
     641250.9794    4315939.1358     641213.6827    4316034.9265
      641198.237     4316051.984     641196.4611    4316061.1043
      641167.771    4316092.2297     641128.7416    4316140.7487
#Sta/Elev= 30
       0  891.12    3.02  889.29   12.09   881.8   15.12  881.16   21.16  875.69
   36.28  863.19    39.3  861.54   42.33  861.13   72.56  860.87  105.67  861.71
  120.05  860.93  128.13   859.9  130.45  859.34   135.1  857.79  137.94  857.42
  146.45  858.92  152.13  859.36  163.48  858.95  171.99  857.84  174.73   858.9
  180.43  861.83  186.36  864.19  189.32   865.7  198.22  871.19  204.15  874.25
  207.12  874.45  210.08  875.53  216.01  878.71  227.87  884.33  239.73  890.51
#Mann= 3 , 0 , 0
       0      .1       0  130.45      .1       0  174.73      .1       0
Bank Sta=130.45,174.73
XS Rating Curve= 0 ,0
Exp/Cntr=0.3,0.1

Type RM Length L Ch R = 1 ,14173.2 ,123.57,91.44,90.72
XS GIS Cut Line= 5
     641231.2679    4315919.1861     641154.8453    4315985.0443
     641133.8175    4316000.4932     641066.4062    4316062.2247
     641101.0926    4316144.6116
#Sta/Elev= 30
       0  891.73    6.11  887.36    9.17  886.06    21.4  875.77   27.51  869.32
   36.69  862.13   39.74  860.49   45.86  859.24   58.09  858.19  109.58  856.73
  118.28  856.05  136.12  855.85  145.26  856.44  163.54   854.7  166.59  854.84
  170.08  855.71  175.73  857.32  181.82  858.52  203.15  862.14  209.24  862.92
  218.38  863.21  227.32  863.99   245.2  867.07  254.14  870.05  257.12  870.29
  280.96  880.99  283.94  882.06  286.92  882.17  298.84  887.78  307.77  892.54
#Mann= 3 , 0 , 0
       0      .1       0  118.28      .1       0  170.08      .1       0
Bank Sta=118.28,170.08
XS Rating Curve= 0 ,0
Exp/Cntr=0.3,0.1

Type RM Length L Ch R = 1 ,14081.76,44.53,34.87,30.38
XS GIS Cut Line= 6
     641121.2627    4315815.2098     641065.4711    4315893.4322
     641053.9476    4315946.6982     641018.6397    4315994.2386
     641039.7092     4316019.728     641101.0926    4316160.4866
#Sta/Elev= 30
       0   900.2    6.01  897.59   12.01  896.03   21.02  891.67   30.03  884.28
   36.03  877.56   48.04  866.63   51.04  865.57   54.05  863.68   63.05  856.18
   66.06  855.21   69.06  854.98  129.38  854.05  147.55  852.81  167.38  852.37
  175.78  853.96  195.71  858.36  209.94  860.15  240.01  859.62   255.3  861.37
  279.87  862.08  298.29  864.03  316.72  867.09  329.01   870.1  356.65  882.31
  362.79   883.7  387.36  896.63  390.43  897.33   393.5  898.73  396.57  900.89
#Mann= 3 , 0 , 0
       0      .1       0  129.38      .1       0  175.78      .1       0
Bank Sta=129.38,175.78
XS Rating Curve= 0 ,0
Exp/Cntr=0.3,0.1

Type RM Length L Ch R = 1 ,14046.89,56.38,56.57,44.58
XS GIS Cut Line= 6
     641047.4266    4315789.9459     641012.3692    4315922.8993
       641008.18    4315950.1955     641011.0904    4315993.3227
     641033.8446     4316017.929     641094.0815    4316152.6198
#Sta/Elev= 30
       0  891.64   12.22  885.56   15.28  884.97   18.33  883.05   42.78   864.3
   48.89     862   58.05  855.42   61.11     854  119.16  854.79  146.44  853.06
   162.5  851.36  165.54  851.63  168.42     853   171.3  854.44  174.18  854.51
  182.83  856.84  200.12  859.77   217.9  860.68  248.43  859.82  260.72  860.99
  279.16  861.58  303.76   864.7   322.2   867.8  328.35  870.16  334.49  871.46
  359.09   881.8  362.16  882.26  365.23  883.47  371.38  886.43  389.82  896.74
#Mann= 3 , 0 , 0
       0      .1       0  146.44      .1       0  168.42      .1       0
Bank Sta=146.44,168.42
XS Rating Curve= 0 ,0
Exp/Cntr=0.3,0.1

Type RM Length L Ch R = 1 ,13990.32,20.43,42.15,29.97
XS GIS Cut Line= 6
     640994.2007    4315765.7275     640958.1936    4315933.0799
     640967.4613    4315941.3166     640964.7096    4315949.5716
     641027.6223     4316015.326     641088.3926    4316146.7283
#Sta/Elev= 30
       0  891.86   15.23  885.18   18.27  884.91   27.41  880.77   36.55  875.98
   45.69  870.02   51.78  867.81   76.14  853.48   79.19  852.22  115.74   852.5
  158.65  850.52  171.75  851.93  179.19  852.52  189.95  856.05  192.86  856.08
  195.89  856.88  223.19  857.94  244.42  860.08  265.66     861  298.94  860.08
  323.07  861.43  344.18  864.45   347.2  864.47  368.31     868  374.34  870.12
  377.36   870.4   404.5  881.47  407.52   881.8  410.54  882.88  428.63  892.71
#Mann= 3 , 0 , 0
       0      .1       0   79.19      .1       0  171.75      .1       0
Bank Sta=79.19,171.75
XS Rating Curve= 0 ,0
Exp/Cntr=0.3,0.1

River Reach=Red Creek       ,3
Reach XY= 30
     640956.5386    4315921.8056     640844.6196    4315804.3303
     640791.4383    4315799.9647     640721.5881    4315892.4368
      640667.613    4315903.9462     640594.5879    4315871.4023
     640540.6128    4315761.8646     640499.7345    4315731.3052
     640088.5712    4315701.5395     639886.1646    4315622.9581
     639701.2204    4315707.4926     639603.1921    4315714.2395
      639561.917    4315689.2364      639444.694    4315530.1785
     639385.7042    4315416.9796     639078.5223    4315292.3606
     639034.0722    4315187.5854     638963.4283    4315116.9415
     638757.4498    4315030.0257     638640.7683    4315049.4726
     638534.8025    4314960.9693     638457.0148    4314940.3317
638307.8736715434314969.58427181638176.262286978 4314845.1516108
638142.4980217624314832.58003033637753.7835214094314845.06041294
637510.613242819 4314931.7806802 637438.409589054314940.96130624
     637185.1332    4314854.0845     636956.1954    4314870.4384

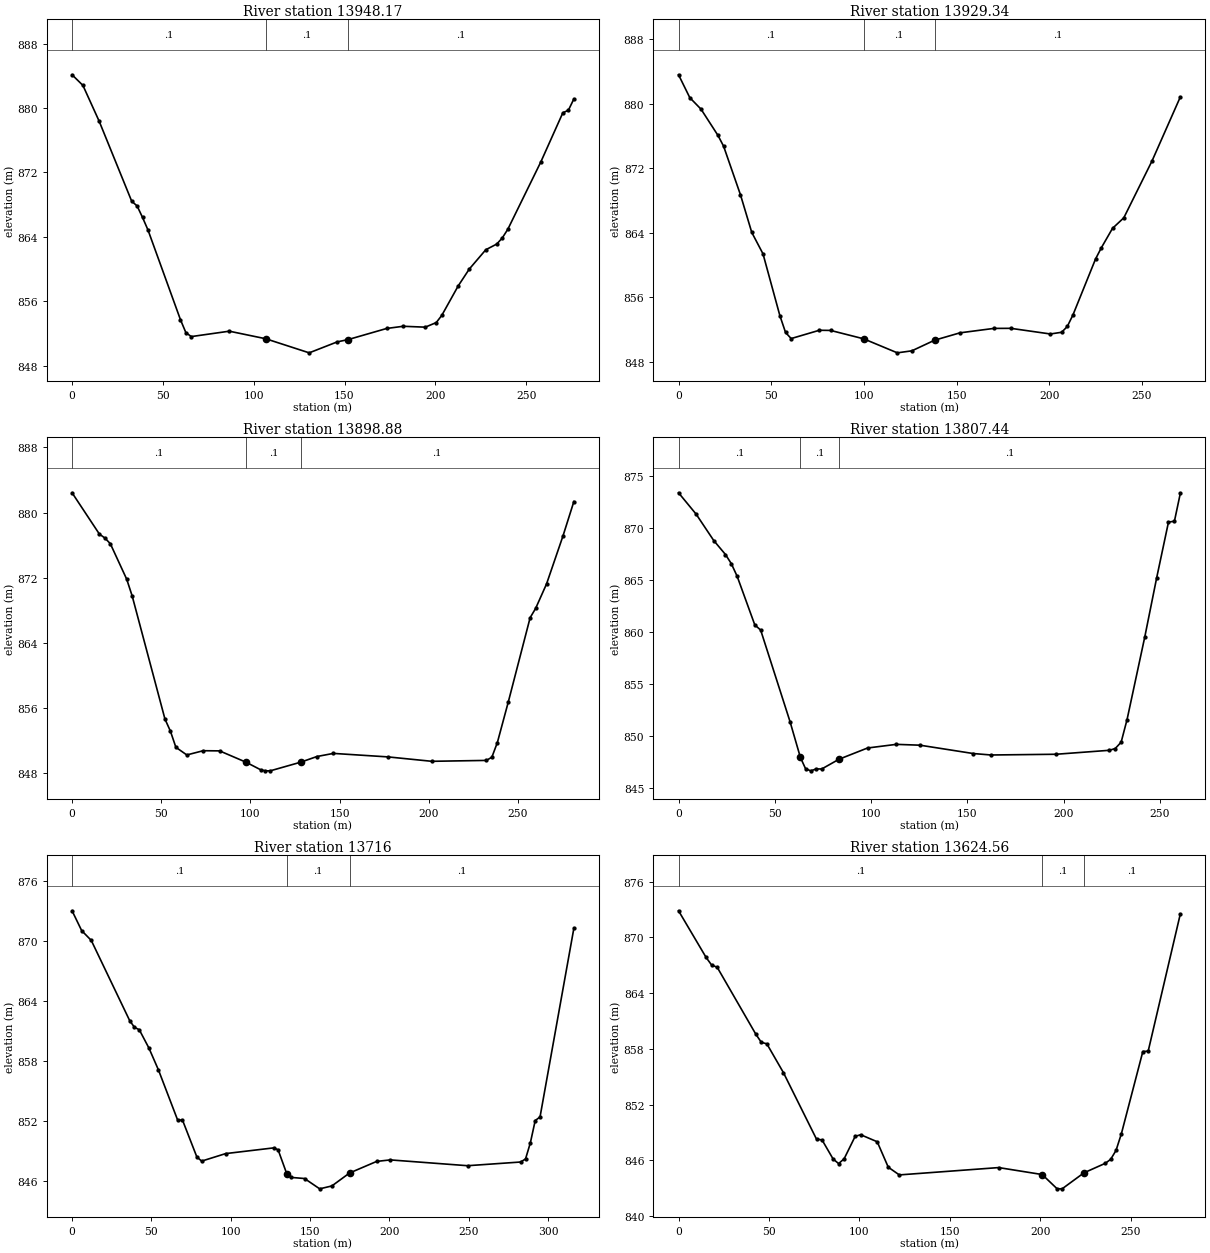
Type RM Length L Ch R = 1 ,13948.17,22.1,18.83,13.78
XS GIS Cut Line= 6
     640979.4109    4315779.7682     640950.0421    4315870.6528
     640935.7545    4315887.7185     640929.5792    4315892.5656
     640921.3241    4315900.1856     640844.8065    4316016.7084
#Sta/Elev= 30
       0  884.13    5.97  882.81   14.92  878.36   32.83  868.42   35.82  867.83
    38.8   866.4   41.79  864.85   59.69  853.69   62.68  852.08   65.66   851.6
   86.56  852.27  106.64  851.33  130.56  849.58  145.97  850.94  152.03  851.23
  173.24  852.61  182.33  852.88  194.45  852.77  200.51  853.34  203.55  854.23
  212.64  857.91   218.7  859.99  227.79  862.39  233.85   863.1  236.88  863.86
  239.91  864.93  258.09   873.3  270.22  879.41  273.25  879.72  276.28  881.12
#Mann= 3 , 0 , 0
       0      .1       0  106.64      .1       0  152.03      .1       0
Bank Sta=106.64,152.03
XS Rating Curve= 0 ,0
Exp/Cntr=0.3,0.1

Type RM Length L Ch R = 1 ,13929.34,21.77,30.46,41.33
XS GIS Cut Line= 6
      640969.489     4315777.387      640934.167    4315854.7778
     640912.7357    4315883.7497     640902.8139    4315902.4029
     640902.8139     4315908.356      640835.345    4316009.9562
#Sta/Elev= 30
       0  883.62    6.08  880.78   12.15  879.35   21.27   876.1   24.31  874.76
   33.42  868.73    39.5  864.07   45.57  861.41   54.69  853.73   57.73  851.66
   60.76   850.9   75.96  851.93   82.03  851.91   99.87  850.87  118.04  849.13
  125.89  849.38  138.17   850.7  151.81  851.61   170.1  852.16  179.25  852.17
  200.59  851.47  206.69  851.68  209.74   852.4  212.79  853.83  224.98  860.77
  228.03  862.13  234.13  864.57  240.23  865.88  255.47  872.94  270.72  880.87
#Mann= 3 , 0 , 0
       0      .1       0   99.87      .1       0  138.17      .1       0
Bank Sta=99.87,138.17
XS Rating Curve= 0 ,0
Exp/Cntr=0.3,0.1

Type RM Length L Ch R = 1 ,13898.88,107.64,91.44,55.59
XS GIS Cut Line= 6
     640960.9977     4315773.277     640909.1514    4315852.8529
     640902.8586    4315857.7631     640887.4555    4315861.5842
     640858.8804    4315893.5989     640816.7995    4316005.4493
#Sta/Elev= 30
       0  882.43   15.32  877.36   18.38  876.88   21.45  876.18   30.64  871.82
    33.7  869.77   52.08  854.66   55.15  853.17   58.21  851.19   64.34  850.25
   73.53  850.77   82.72  850.75   97.64  849.35  105.67  848.44  108.39   848.3
  111.11   848.3  128.16  849.36  137.35  850.06  146.55  850.44  177.19  850.01
  201.71  849.47  232.35  849.58  235.41  849.98  238.48  851.77  244.61  856.75
  256.86   867.1  259.93  868.23  266.06  871.24  275.25  877.11  281.38  881.35
#Mann= 3 , 0 , 0
       0      .1       0   97.64      .1       0  128.16      .1       0
Bank Sta=97.64,128.16
XS Rating Curve= 0 ,0
Exp/Cntr=0.3,0.1

Type RM Length L Ch R = 1 ,13807.44,101.41,91.44,41.08
XS GIS Cut Line= 5
     640849.8724    4315736.2352     640835.6715    4315792.3436
     640832.3876    4315805.4794     640824.6609    4315843.3015
      640807.539    4315992.8816
#Sta/Elev= 30
       0  873.36    9.14  871.31   18.28  868.78   24.37  867.44   27.42  866.56
   30.46  865.34    39.6  860.69   42.65  860.19   57.88  851.42   63.29  847.97
      66  846.88   68.71  846.69   71.42  846.87   74.39  846.87    83.3   847.8
   98.14  848.88  113.09  849.23  125.38  849.15  153.04  848.35  162.25  848.21
  196.05  848.28  223.71  848.66  226.78  848.83  229.85  849.44  232.92  851.61
  242.14  859.55  248.29   865.2  254.43  870.55  257.51  870.63  260.58  873.31
#Mann= 3 , 0 , 0
       0      .1       0   63.29      .1       0    83.3      .1       0
Bank Sta=63.29,83.3
XS Rating Curve= 0 ,0
Exp/Cntr=0.3,0.1

Type RM Length L Ch R = 1 ,13716   ,83.25,91.44,100.61
XS GIS Cut Line= 6
     640724.1951    4315693.9018      640746.741    4315818.9597
     640757.6378    4315835.0538     640772.9348    4315847.5348
      640796.844    4315872.0402      640783.065    4315986.9284
#Sta/Elev= 30
       0  873.03    6.05  871.05    12.1  870.07   36.31  862.06   39.33  861.39
   42.36  861.15   48.41  859.33   54.46  857.13   66.56  852.12   69.59  852.13
   78.66  848.44   81.69  848.03   96.82  848.78  127.07  849.35  129.85  849.16
   135.4  846.73  138.18   846.4  146.51  846.29  156.08  845.26  163.76  845.55
  174.88  846.84     192     848  200.56  848.15  249.28  847.57  282.77  847.94
  285.82  848.25  288.86  849.86  291.91  852.08  294.95  852.44  316.27  871.28
#Mann= 3 , 0 , 0
       0      .1       0   135.4      .1       0  174.88      .1       0
Bank Sta=135.4,174.88
XS Rating Curve= 0 ,0
Exp/Cntr=0.3,0.1

Type RM Length L Ch R = 1 ,13624.56,69.1,91.44,99.33
XS GIS Cut Line= 6
     640696.7004    4315689.5141     640692.0597    4315866.4387
       640697.24    4315893.0277      640698.992    4315894.7126
     640703.0898    4315908.7519     640709.4005    4315964.6813
#Sta/Elev= 30
       0  872.87   15.26  867.84   18.31  867.02   21.36  866.79   42.72  859.58
   45.77   858.7   48.82  858.54   57.98  855.44   76.29  848.27   79.34  848.19
   85.44  846.14   88.49  845.64   91.54  846.15   97.65  848.57   100.7  848.75
  109.85  847.99  115.96  845.25  122.06  844.42  176.99  845.21  201.06  844.46
  209.29  842.93  212.07  842.92  224.11  844.64  235.96  845.67  238.92   846.1
  241.89  847.06  244.85  848.86   256.7  857.71  259.66  857.75  277.43  872.53
#Mann= 3 , 0 , 0
       0      .1       0  201.06      .1       0  224.11      .1       0
Bank Sta=201.06,224.11
XS Rating Curve= 0 ,0
Exp/Cntr=0.3,0.1

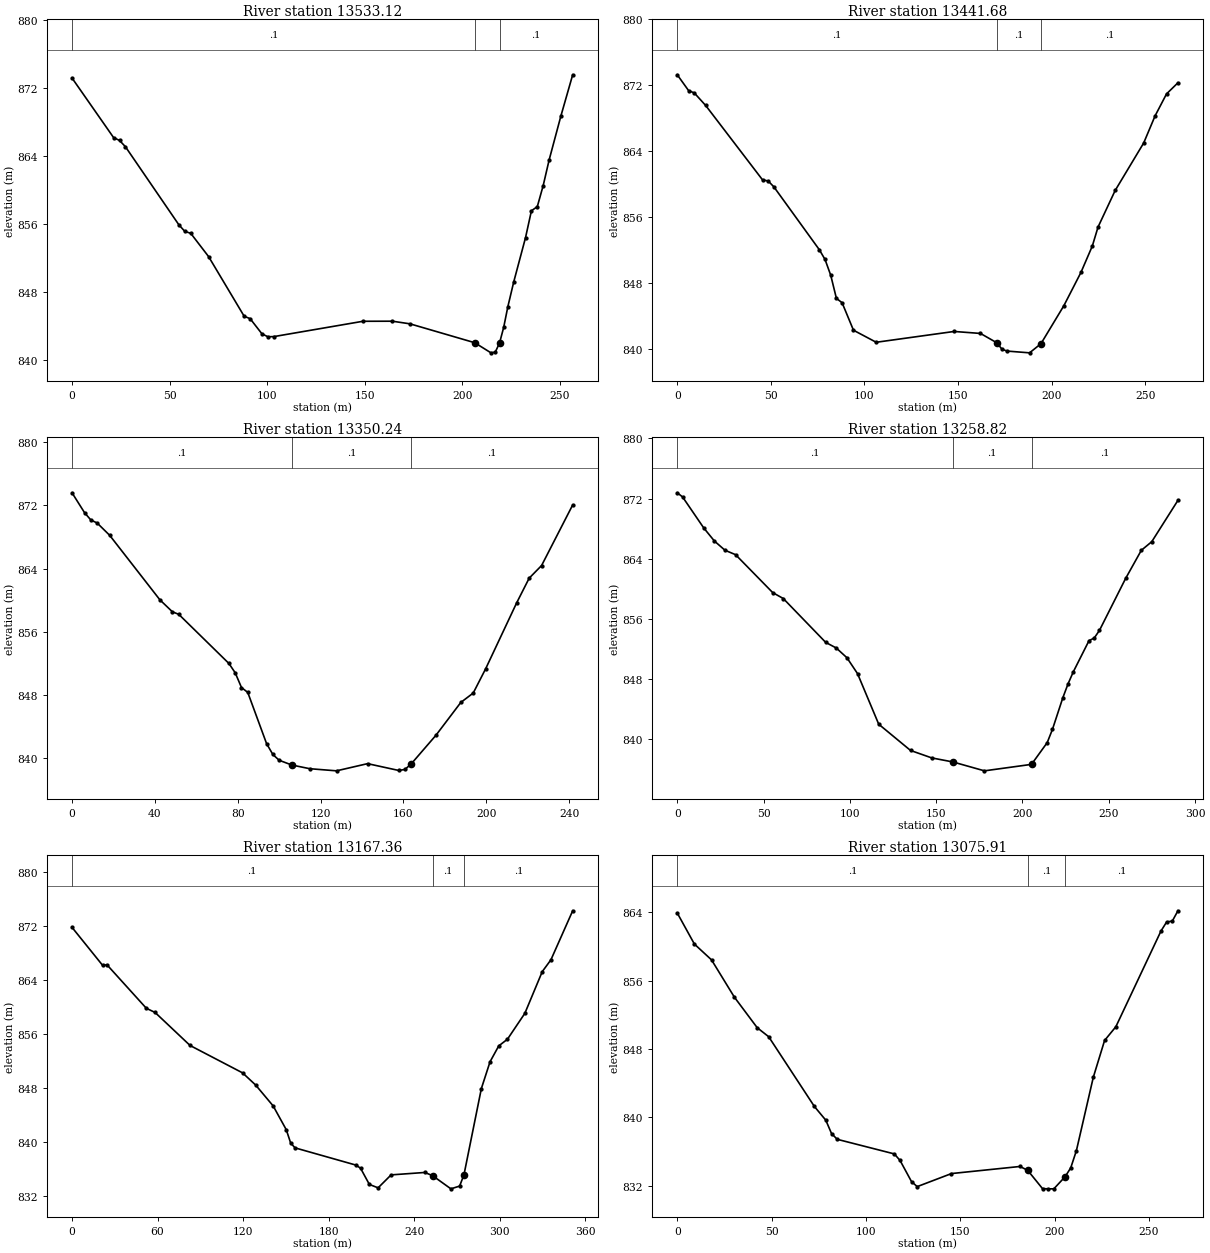
Type RM Length L Ch R = 1 ,13533.12,77.94,91.44,100.63
XS GIS Cut Line= 6
      640687.881    4315685.6688     640649.8259    4315832.9303
     640619.6586    4315874.3011     640615.0288    4315882.2389
     640608.8847    4315891.1491     640588.6606    4315917.5166
#Sta/Elev= 30
       0  873.18   21.29  866.18   24.34  865.84   27.38   865.1   54.76  855.92
    57.8  855.15   60.84  854.92   69.97  852.19   88.22  845.17   91.26  844.89
   97.34   843.1  100.39  842.76  103.43  842.78  149.06  844.58  164.15  844.59
  173.18  844.28  206.36  842.06  214.68  840.87  216.87  840.95  219.06  842.02
  221.19  843.86  223.32  846.29  226.34  849.21  232.38  854.41   235.4  857.57
  238.42  858.06  241.44  860.54  244.47  863.54  250.51  868.72  256.55  873.56
#Mann= 3 , 0 , 0
       0      .1       0  206.36      .1       0  219.06      .1       0
Bank Sta=206.36,219.06
XS Rating Curve= 0 ,0
Exp/Cntr=0.3,0.1

Type RM Length L Ch R = 1 ,13441.68,105.87,91.44,82.16
XS GIS Cut Line= 6
     640672.0059    4315674.0271     640601.6519    4315791.2085
     640576.7387    4315804.3319     640571.6089     4315807.268
     640560.9222     4315811.262     640491.0306    4315860.2942
#Sta/Elev= 30
       0  873.27    6.07  871.35    9.11  871.07   15.19  869.55   45.56  860.54
    48.6   860.4   51.63  859.69   75.93  852.07   78.97  850.89   82.01  848.98
   85.04  846.18   88.08  845.65   94.16  842.32  106.31  840.86  147.94  842.17
  162.02  841.93  170.75   840.8   173.6  839.99  176.45  839.79  188.26  839.58
  194.35  840.69  206.55  845.28   215.7  849.32   221.8  852.53  224.84  854.82
  233.99  859.25  249.24  865.01  255.34   868.3  261.43  870.95  267.53   872.3
#Mann= 3 , 0 , 0
       0      .1       0  170.75      .1       0  194.35      .1       0
Bank Sta=170.75,194.35
XS Rating Curve= 0 ,0
Exp/Cntr=0.3,0.1

Type RM Length L Ch R = 1 ,13350.24,98.76,91.42,83.12
XS GIS Cut Line= 5
     640566.1724    4315627.4604     640518.3635    4315725.5229
     640513.3104    4315735.7085     640509.1001    4315741.5854
     640469.8639    4315848.6525
#Sta/Elev= 30
       0  873.58    6.06  871.06    9.09  870.14   12.12  869.76   18.18   868.2
   42.43  860.04   48.49  858.52   51.52  858.21   75.76  851.99   78.79  850.81
   81.82  848.95   84.85  848.33   93.94  841.85   96.97  840.48     100  839.75
  106.07  839.15  114.78  838.68   127.7  838.41   142.7  839.32   157.7  838.46
   160.7  838.58  163.71  839.27  175.71  842.91  187.71  847.06  193.71  848.25
  199.71  851.32  214.72  859.68  220.72  862.78  226.72  864.38  241.73  872.04
#Mann= 3 , 0 , 0
       0      .1       0  106.07      .1       0  163.71      .1       0
Bank Sta=106.07,163.71
XS Rating Curve= 0 ,0
Exp/Cntr=0.3,0.1

Type RM Length L Ch R = 1 ,13258.82,101.78,91.46,94.17
XS GIS Cut Line= 4
     640432.8221    4315539.6185     640427.5451    4315702.3222
     640422.6402    4315713.4267     640424.3554    4315828.5441
#Sta/Elev= 30
       0  872.78    3.07  872.23   15.36   868.1    21.5  866.37   27.64  865.14
   33.79  864.55   55.29  859.51   61.43  858.72      86  852.89   92.14  852.14
   98.29  850.85  104.43  848.74  116.72  842.01  135.15  838.52  147.43  837.53
  159.72  836.99  177.96  835.81  205.23  836.67  214.32  839.56  217.35  841.31
   223.4  845.54  226.43  847.39  229.46  848.98  238.55  853.12  241.58  853.47
  244.61  854.49  259.76  861.39  268.85  865.13  274.91  866.28  290.06  871.77
#Mann= 3 , 0 , 0
       0      .1       0  159.72      .1       0  205.23      .1       0
Bank Sta=159.72,205.23
XS Rating Curve= 0 ,0
Exp/Cntr=0.3,0.1

Type RM Length L Ch R = 1 ,13167.36,83.56,91.45,92.03
XS GIS Cut Line= 6
     640360.8553    4315467.6517      640324.547    4315679.3343
     640329.0449    4315706.3219     640331.2362    4315716.9043
      640331.396    4315729.8083     640315.3469    4315813.7274
#Sta/Elev= 30
       0  871.82   21.48  866.18   24.55  866.26   52.16  859.81    58.3  859.19
   82.84  854.29  119.66  850.23  128.86  848.42  141.14  845.32  150.34  841.79
  153.41  839.82  156.48   839.1  199.43  836.53   202.5  836.06  208.64  833.67
  214.77  833.17  223.89  835.09  247.54  835.45  252.94  834.98  265.85  833.02
  271.95  833.43     275   835.1  287.21   847.9  293.31  851.88  299.41  854.23
  305.51  855.22  317.72  859.06  329.93  865.25  336.03  867.01  351.29  874.28
#Mann= 3 , 0 , 0
       0      .1       0  252.94      .1       0     275      .1       0
Bank Sta=252.94,275
XS Rating Curve= 0 ,0
Exp/Cntr=0.3,0.1

Type RM Length L Ch R = 1 ,13075.91,93.29,91.43,87.64
XS GIS Cut Line= 3
     640267.7218    4315521.6268     640243.5717    4315698.6871
     640228.5634     4315784.094
#Sta/Elev= 30
       0  863.93    9.09  860.29   18.17  858.44   30.29  854.07    42.4  850.49
   48.46  849.44   72.69  841.27   78.75  839.66   81.78   838.1   84.81  837.42
  115.09  835.71  118.12  834.94  124.18  832.47  127.21  831.88  145.38  833.41
  181.69  834.24  185.77  833.79  193.65  831.64  196.64  831.62  199.63  831.62
  205.61  833.04   208.6  834.08  211.59  836.09  220.56  844.69  226.54     849
  232.52  850.61  256.44  861.82  259.43  862.88  262.43  862.98  265.42  864.19
#Mann= 3 , 0 , 0
       0      .1       0  185.77      .1       0  205.61      .1       0
Bank Sta=185.77,205.61
XS Rating Curve= 0 ,0
Exp/Cntr=0.3,0.1

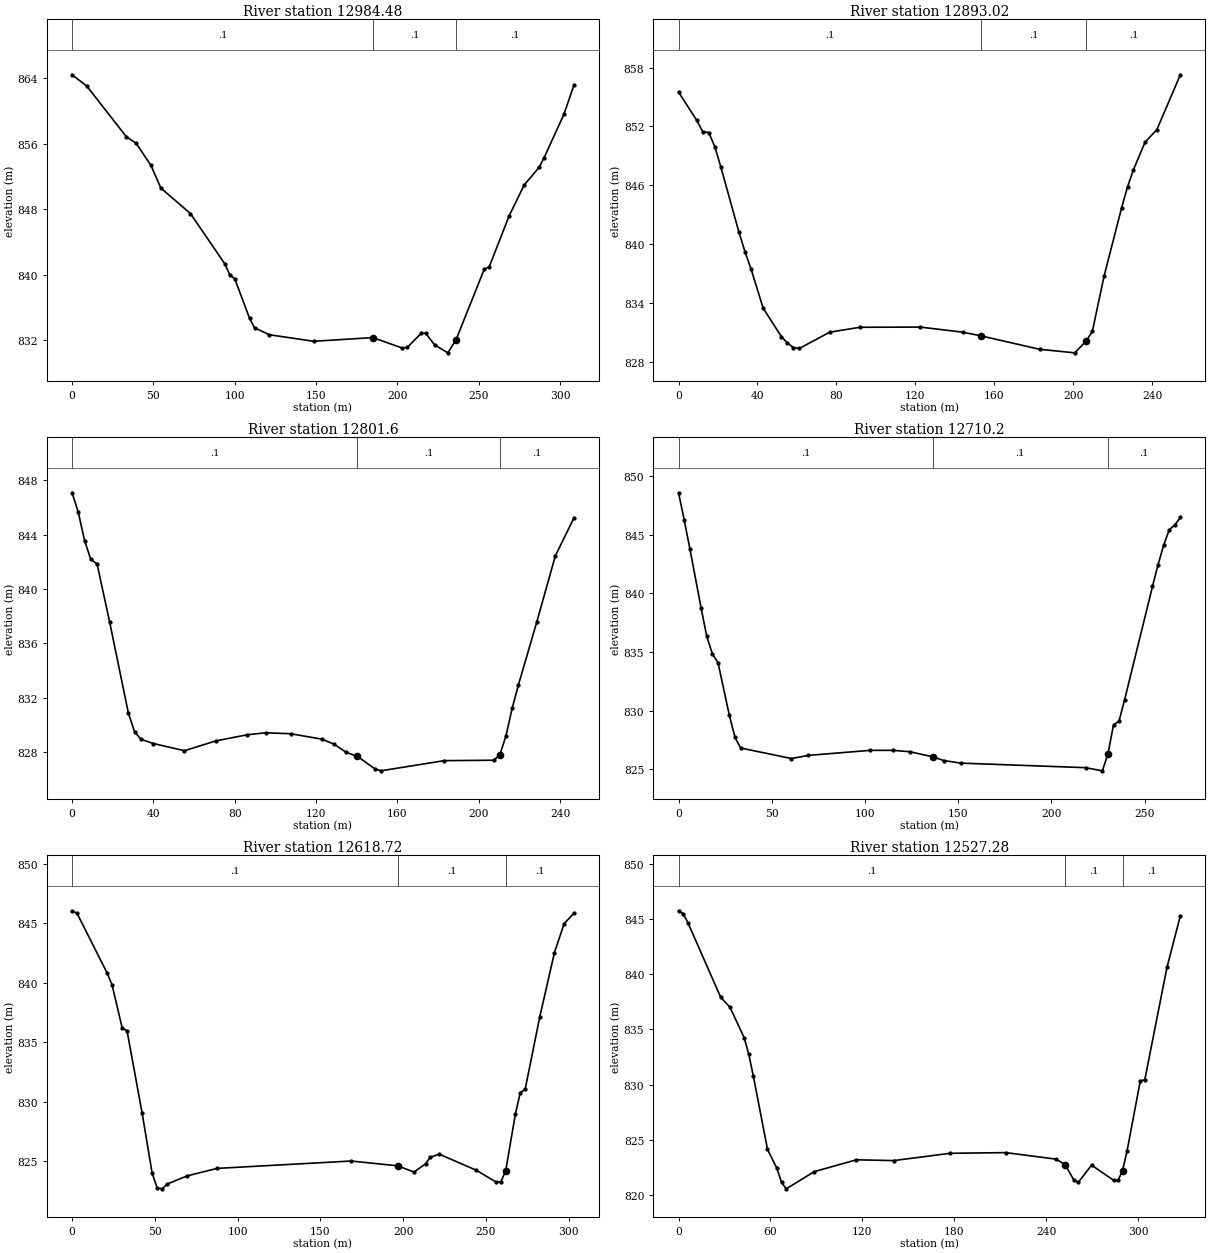
Type RM Length L Ch R = 1 ,12984.48,84.58,91.46,100.4
XS GIS Cut Line= 5
      640183.055    4315481.4101     640150.7134    4315688.1185
     640149.8402    4315709.9488     640151.2644    4315719.9964
     640148.1299     4315787.269
#Sta/Elev= 30
       0  864.43     9.1  863.04   33.35  856.87   39.42  856.06   48.52  853.36
   54.58   850.6   72.77  847.49      94  841.33   97.03  839.97  100.06  839.52
  109.16  834.68  112.19  833.54  121.29  832.69  148.58  831.89  184.97  832.34
  203.16  831.06  206.19  831.15  214.69  832.87  217.42  832.88  222.88  831.46
  231.07  830.48  236.14  832.09  253.46  840.69  256.52  840.99  268.77  847.21
  277.95  850.95  287.14  853.12   290.2  854.27  302.44   859.6  308.56  863.13
#Mann= 3 , 0 , 0
       0      .1       0  184.97      .1       0  236.14      .1       0
Bank Sta=184.97,236.14
XS Rating Curve= 0 ,0
Exp/Cntr=0.3,0.1

Type RM Length L Ch R = 1 ,12893.02,89.29,91.42,91.39
XS GIS Cut Line= 4
     640098.3881    4315516.3352     640067.3349    4315672.6149
     640061.1032    4315689.1875      640038.063    4315762.9273
#Sta/Elev= 30
       0  855.51    9.19  852.63   12.26  851.48   15.32  851.38   18.38  849.95
   21.45  847.88   30.64  841.23   33.71  839.24   36.77  837.49    42.9  833.52
   52.09  830.64   55.15  829.98   58.22  829.52   61.28  829.43    76.6  831.08
   91.92  831.58  122.57   831.6  144.01  831.08  153.21  830.71  182.98  829.34
  200.81  828.98  206.75  830.22  209.73  831.18  215.67  836.79  224.58  843.76
  227.55  845.87  230.53   847.6  236.47  850.42  242.41  851.68   254.3  857.26
#Mann= 3 , 0 , 0
       0      .1       0  153.21      .1       0  206.75      .1       0
Bank Sta=153.21,206.75
XS Rating Curve= 0 ,0
Exp/Cntr=0.3,0.1

Type RM Length L Ch R = 1 ,12801.6 ,94.23,91.4,89.77
XS GIS Cut Line= 6
     640017.6019    4315504.5832     639988.1085    4315633.3028
     639984.3507    4315643.5966     639979.4828    4315654.2509
     639976.2424    4315660.5064       639942.46    4315738.4754
#Sta/Elev= 30
       0  847.07    3.07  845.63    6.14  843.56    9.21  842.17   12.28  841.84
   18.43   837.6   27.64   830.9   30.71   829.5   33.78  828.95   39.92  828.63
   55.28   828.1   70.63  828.82   85.99  829.27    95.2  829.42  107.49  829.35
  122.84  828.95  128.98  828.57  134.79  827.98  140.27  827.69  148.87  826.77
   151.8  826.62  183.02  827.37  207.29   827.4  210.33  827.78  213.36  829.19
   216.4  831.21  219.43  832.91  228.54  837.58  237.64  842.43  246.75  845.21
#Mann= 3 , 0 , 0
       0      .1       0  140.27      .1       0  210.33      .1       0
Bank Sta=140.27,210.33
XS Rating Curve= 0 ,0
Exp/Cntr=0.3,0.1

Type RM Length L Ch R = 1 ,12710.2 ,103.58,91.48,76.56
XS GIS Cut Line= 4
     639921.2933    4315481.2998     639891.6893    4315639.0143
     639887.0422    4315644.3762     639890.6016    4315745.8837
#Sta/Elev= 30
       0  848.59    3.03  846.28    6.06  843.83   12.11  838.75   15.14  836.33
   18.17  834.83   21.19  834.08   27.25  829.59   30.28  827.71    33.3   826.8
   60.55   825.9   69.64  826.17  102.94   826.6  115.05   826.6  124.14  826.48
  136.25  826.05   142.3  825.73  151.39  825.51  218.35  825.12  227.31  824.85
   230.3  826.29  233.29  828.77  236.27   829.1  239.26  830.93   254.2  840.59
  257.18  842.45  260.17   844.1  263.16  845.42  266.15  845.84  269.13  846.48
#Mann= 3 , 0 , 0
       0      .1       0  136.25      .1       0   230.3      .1       0
Bank Sta=136.25,230.3
XS Rating Curve= 0 ,0
Exp/Cntr=0.3,0.1

Type RM Length L Ch R = 1 ,12618.72,89.74,91.44,90.74
XS GIS Cut Line= 6
     639784.7681    4315459.0748      639788.743     4315604.057
     639804.5556    4315645.0843      639815.029    4315667.2318
     639822.2731     4315687.779     639834.5098    4315754.3504
#Sta/Elev= 30
       0  846.06    3.02  845.84   21.15  840.83   24.17  839.82   30.22  836.23
   33.24  835.93    42.3  829.05   48.35     824   51.37  822.75   54.39  822.67
   57.41  823.07    69.5  823.76   87.63  824.39  168.49  825.01  196.59  824.61
   206.5  824.08  213.52  824.78  216.25  825.31  221.69  825.59   244.2  824.23
  255.97  823.25  258.91  823.26  261.85  824.16  267.74  828.96  270.68  830.76
  273.63  831.04  282.45  837.13  291.28  842.52  297.17  844.98  303.05  845.85
#Mann= 3 , 0 , 0
       0      .1       0  196.59      .1       0  261.85      .1       0
Bank Sta=196.59,261.85
XS Rating Curve= 0 ,0
Exp/Cntr=0.3,0.1

Type RM Length L Ch R = 1 ,12527.28,80.15,91.44,101.69
XS GIS Cut Line= 5
     639723.3846    4315438.9664     639708.2033    4315636.9645
      639720.197    4315677.3438     639735.7168    4315714.6434
     639741.3763    4315760.7004
#Sta/Elev= 30
       0  845.75    3.06  845.48    6.11  844.67    27.5  837.92   33.61     837
   42.77  834.27   45.83  832.76   48.88  830.74   58.05  824.14   64.16  822.43
   67.21  821.15   70.27  820.56    88.6  822.12  116.09  823.19  140.53  823.12
  177.19  823.78  213.62  823.84  246.47  823.25  252.24  822.76  258.02  821.36
   260.9  821.14  269.56  822.71     284  821.33   286.9  821.34   289.8  822.21
   292.7  823.96   301.4  830.35   304.3  830.43   318.8  840.63  327.51  845.29
#Mann= 3 , 0 , 0
       0      .1       0  252.24      .1       0   289.8      .1       0
Bank Sta=252.24,289.8
XS Rating Curve= 0 ,0
Exp/Cntr=0.3,0.1

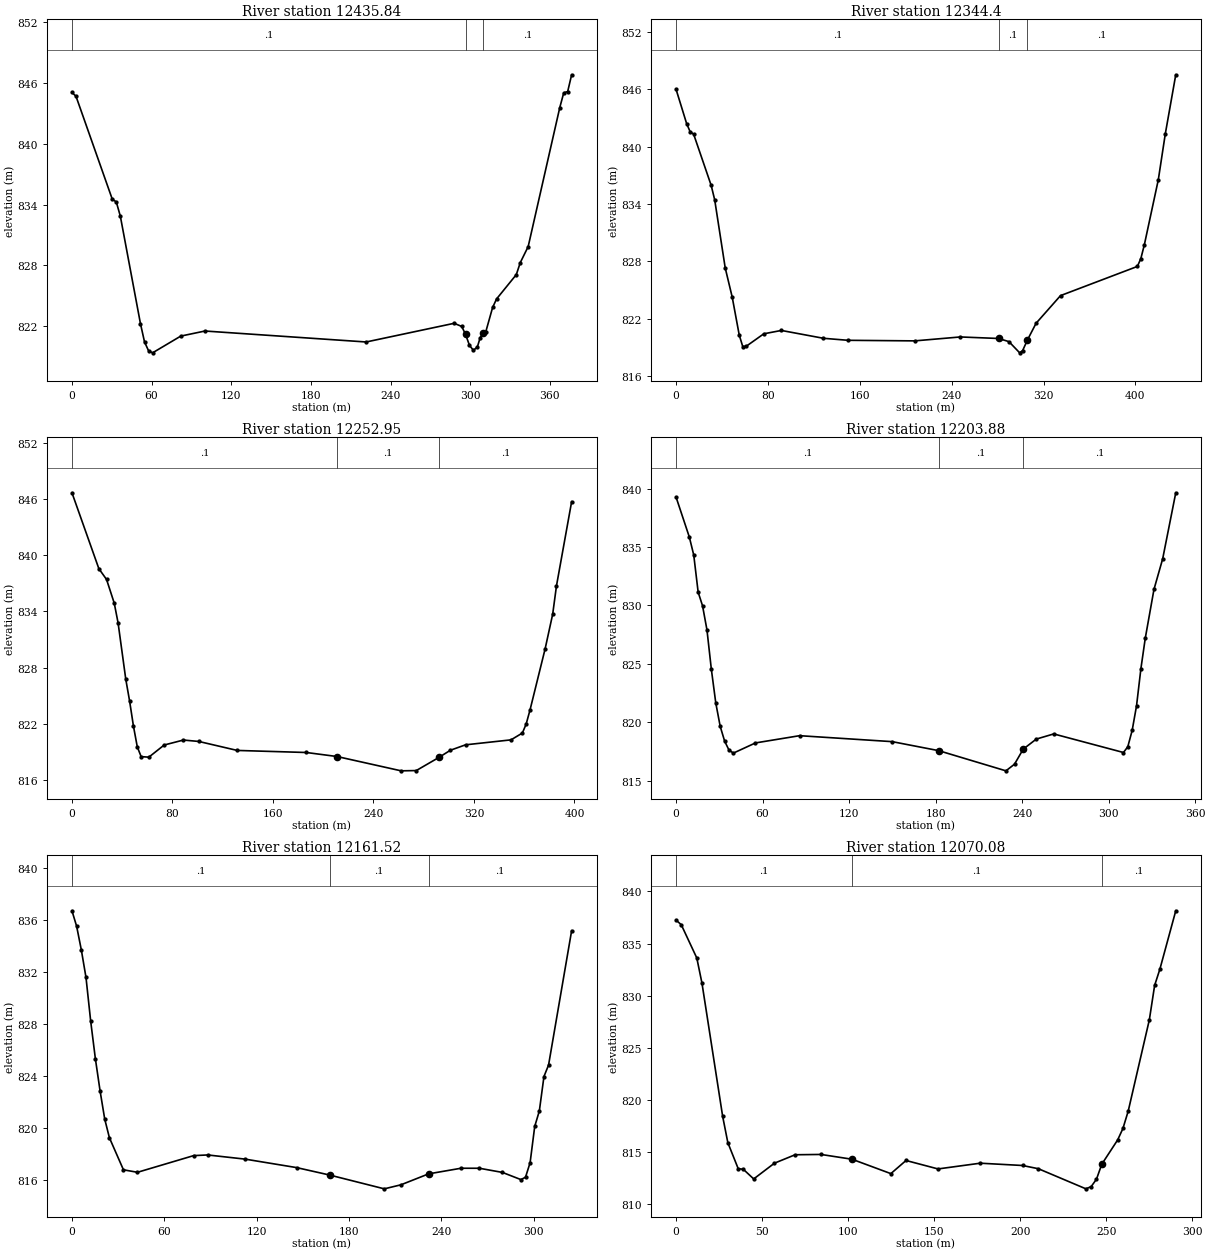
Type RM Length L Ch R = 1 ,12435.84,66.15,91.44,102.12
XS GIS Cut Line= 6
     639679.9928     4315415.683     639635.5718     4315642.064
     639639.4909    4315690.4854     639639.3566    4315716.5215
     639636.9906    4315724.6696      639637.848    4315787.1562
#Sta/Elev= 30
       0  845.05    3.04  844.67   30.36  834.53   33.39  834.26   36.43  832.86
    51.6  822.26   54.64  820.47   57.67   819.6   60.71  819.39   81.96  821.04
  100.17  821.54  221.59  820.46  287.87   822.3  293.59  821.99  296.45  821.21
  299.42  820.12  302.38  819.64  305.35  819.97   307.5   820.9  309.64   821.3
  311.75  821.49  316.83  823.86  319.81   824.7  334.69   827.1  337.67  828.28
  343.62  829.86  367.42  843.56   370.4  845.01  373.38  845.14  376.35  846.79
#Mann= 3 , 0 , 0
       0      .1       0  296.45      .1       0  309.64      .1       0
Bank Sta=296.45,309.64
XS Rating Curve= 0 ,0
Exp/Cntr=0.3,0.1

Type RM Length L Ch R = 1 ,12344.4 ,84.24,91.45,90.7
XS GIS Cut Line= 6
     639669.4095    4315407.2164     639580.6794    4315661.1012
     639577.2398     4315665.996     639562.3265    4315681.8253
     639555.5403    4315685.5092     639457.7424    4315772.3421
#Sta/Elev= 30
       0  845.97    9.17   842.4   12.22  841.55   15.28  841.29   30.56  835.94
   33.62  834.43   42.79  827.31    48.9  824.25   55.01  820.29   58.07  819.09
   61.12  819.13    76.4  820.43   91.69  820.78  128.36  819.96  149.75  819.75
  207.82  819.69  247.55   820.1  280.91  819.94   289.9  819.61  299.25  818.44
  301.83  818.68  306.02  819.79  313.52  821.53  334.81  824.42  401.73  827.47
  404.77  828.29  407.81  829.73  419.98  836.53  426.06  841.32  435.18   847.5
#Mann= 3 , 0 , 0
       0      .1       0  280.91      .1       0  306.02      .1       0
Bank Sta=280.91,306.02
XS Rating Curve= 0 ,0
Exp/Cntr=0.3,0.1

Type RM Length L Ch R = 1 ,12252.95,50.81,49.07,53.47
XS GIS Cut Line= 6
     639652.4761     4315399.808      639594.648    4315538.0994
     639537.0478    4315592.7735     639525.4061    4315597.4302
     639513.8141    4315605.5331     639404.8256    4315696.1419
#Sta/Elev= 30
       0  846.67   21.41  838.56   27.53  837.41   33.65  834.88   36.71  832.77
   42.83  826.75   45.89  824.41   48.95  821.73      52  819.52   55.06  818.48
   61.18  818.42   73.42  819.72   88.71  820.25  100.95   820.1  131.54  819.14
  186.55  818.92  210.99  818.49  262.03  816.96  274.09  816.99  292.18   818.4
  301.23  819.16  313.29  819.74  349.48  820.27  358.52     821  361.54  821.96
  364.56  823.44  376.62  829.99  382.65   833.7  385.67  836.73  397.73  845.72
#Mann= 3 , 0 , 0
       0      .1       0  210.99      .1       0  292.18      .1       0
Bank Sta=210.99,292.18
XS Rating Curve= 0 ,0
Exp/Cntr=0.3,0.1

Type RM Length L Ch R = 1 ,12203.88,35.76,42.36,42.3
XS GIS Cut Line= 6
     639626.2529    4315410.9472     639541.5861    4315534.6401
     639491.9766    4315559.7756     639481.3933    4315569.6975
     639472.7943     4315577.635     639382.8358    4315649.0726
#Sta/Elev= 30
       0  839.27    9.18  835.86   12.24  834.32    15.3  831.14   18.35  829.97
   21.41  827.91   24.47  824.52   27.53  821.65   30.59  819.65   33.65  818.39
   36.71  817.61   39.77  817.36   55.06  818.23   85.65  818.85  149.89  818.34
  182.09  817.57  228.79  815.84  234.74  816.41  240.79   817.7  249.86  818.56
  261.95     819  310.32  817.41  313.34  817.91  316.36  819.31  319.38  821.41
  322.41  824.59  325.43  827.19  331.48  831.38  337.52     834  346.59  839.65
#Mann= 3 , 0 , 0
       0      .1       0  182.09      .1       0  240.79      .1       0
Bank Sta=182.09,240.79
XS Rating Curve= 0 ,0
Exp/Cntr=0.3,0.1

Type RM Length L Ch R = 1 ,12161.52,98.5,91.44,101.93
XS GIS Cut Line= 6
     639603.6339    4315405.8141     639505.3484     4315513.755
     639466.4546    4315531.6144     639455.6085    4315536.2879
     639445.5096    4315544.7467     639370.1849    4315626.1274
#Sta/Elev= 30
       0  836.69    3.04   835.5    6.08  833.69    9.12  831.57   12.17  828.21
   15.21  825.34   18.25  822.88   21.29   820.7   24.33  819.27   33.45  816.81
   42.58  816.62   79.07   817.9    88.2  817.95  112.53  817.63  145.98  816.98
  167.38  816.41  202.94  815.35  213.77  815.66  231.75   816.5  252.73  816.93
  264.72  816.93   279.7  816.61  291.69  816.06  294.69  816.24  297.68  817.36
  300.68  820.14  303.68  821.33  306.68  823.97  309.67  824.85  324.66  835.16
#Mann= 3 , 0 , 0
       0      .1       0  167.38      .1       0  231.75      .1       0
Bank Sta=167.38,231.75
XS Rating Curve= 0 ,0
Exp/Cntr=0.3,0.1

Type RM Length L Ch R = 1 ,12070.08,99.99,91.44,64.09
XS GIS Cut Line= 6
     639474.2524     4315358.189     639427.8478    4315449.2865
     639410.7925    4315458.9611     639390.3828    4315464.1032
     639373.3436    4315470.9823     639282.1645    4315562.1831
#Sta/Elev= 30
       0  837.25    3.01  836.81   12.03  833.62   15.03  831.21   27.06  818.42
   30.07   815.9   36.08  813.41   39.09  813.34    45.1  812.42   57.13  813.93
   69.16  814.74   84.19  814.77  102.24  814.31  124.79  812.93  133.61  814.19
   152.2  813.38  176.74  813.93  201.31  813.71  210.52   813.4  238.15  811.47
  241.22  811.69  244.29   812.4  247.36  813.83  256.57  816.16  259.65  817.26
  262.72  818.93     275  827.69  278.07  830.99  281.14  832.56  290.35  838.15
#Mann= 3 , 0 , 0
       0      .1       0  102.24      .1       0  247.36      .1       0
Bank Sta=102.24,247.36
XS Rating Curve= 0 ,0
Exp/Cntr=0.3,0.1

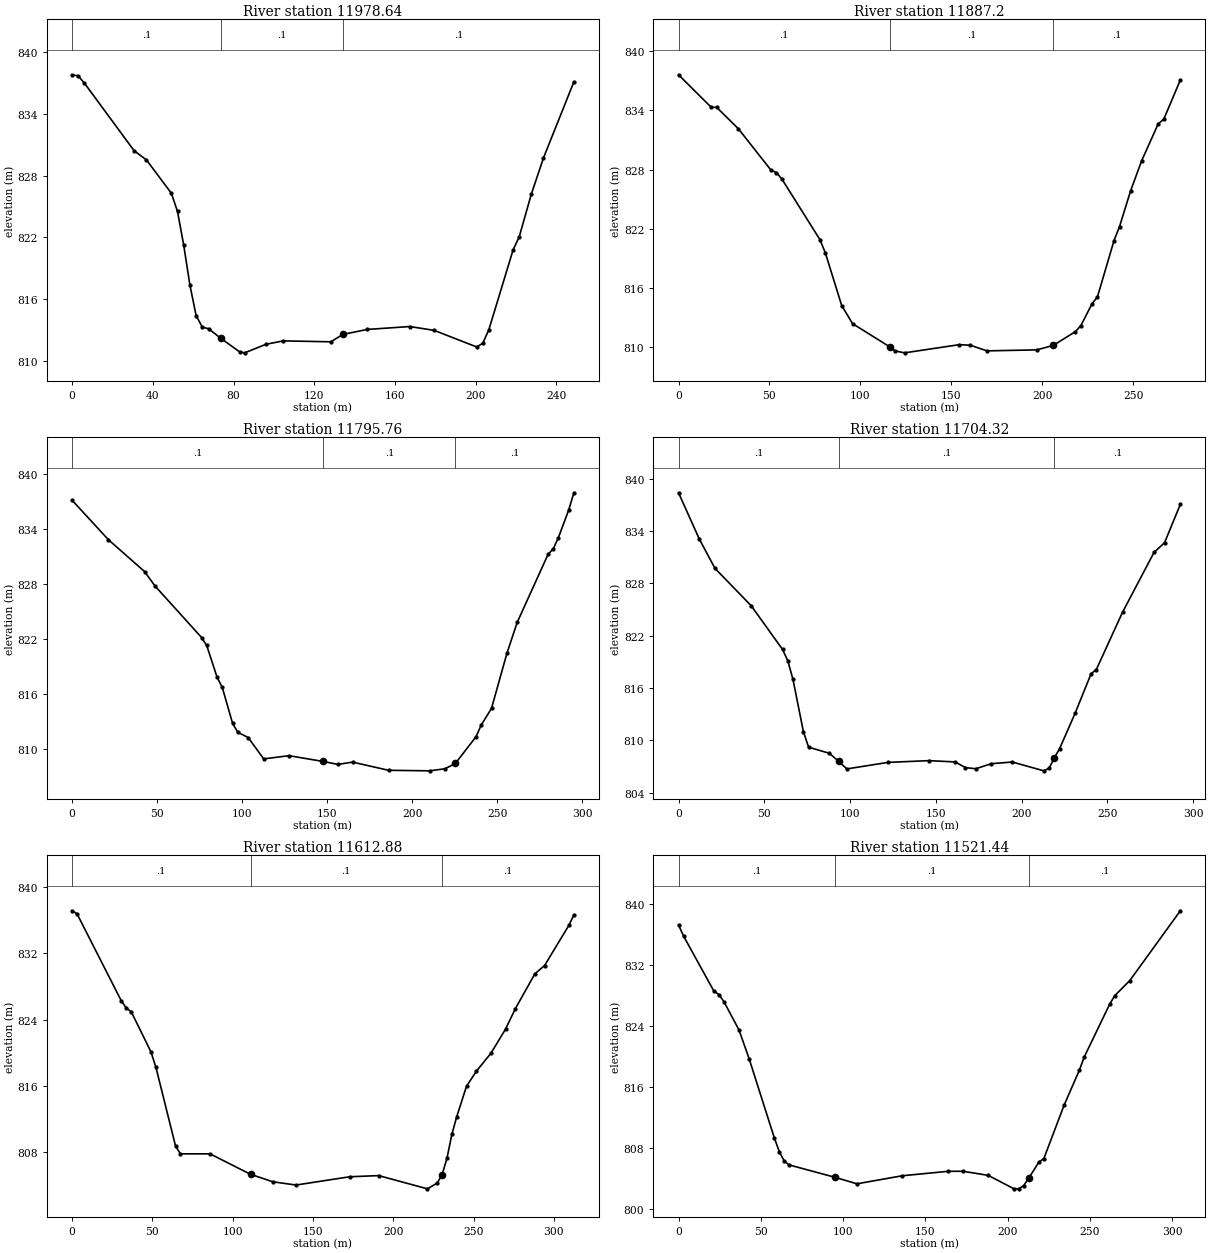
Type RM Length L Ch R = 1 ,11978.64,93.82,91.44,94.36
XS GIS Cut Line= 6
     639375.8272    4315313.7389     639350.1475    4315392.6452
     639347.4037    4315399.8841     639347.0219    4315407.9276
     639334.2858    4315434.4929      639261.527    4315530.4331
#Sta/Elev= 30
       0  837.77    3.07  837.66    6.15  836.95   30.73  830.41   36.88  829.51
   49.17  826.29   52.25  824.52   55.32  821.25   58.39  817.38   61.47  814.42
   64.54   813.3   67.61  813.15   73.76  812.21   82.98  810.91   85.56  810.81
   96.09  811.64  104.67  811.97  128.23  811.88  134.25   812.6   146.3  813.08
  167.37  813.36  179.41  812.99  200.48  811.38  203.49  811.73   206.5  813.04
  218.54   820.8  221.55  822.05  227.57   826.2  233.59  829.71  248.64  837.08
#Mann= 3 , 0 , 0
       0      .1       0   73.76      .1       0  134.25      .1       0
Bank Sta=73.76,134.25
XS Rating Curve= 0 ,0
Exp/Cntr=0.3,0.1

Type RM Length L Ch R = 1 ,11887.2 ,89.93,91.44,91.02
XS GIS Cut Line= 6
     639316.2959    4315248.6513      639272.238    4315343.5832
     639268.0087    4315351.3578     639261.2966    4315369.0663
     639256.6985    4315377.7156     639205.1706    4315501.0643
#Sta/Elev= 30
       0  837.62   17.94  834.33   20.93  834.32   32.89  832.15   50.83  827.95
   53.82   827.7   56.81  827.05   77.75   820.9   80.74  819.55   89.71  814.22
   95.69  812.38  116.21  810.02  118.92  809.62  124.33  809.42  154.39  810.25
  160.47  810.19  169.58  809.62  196.93  809.72  206.04  810.17   218.2  811.57
  221.23  812.18  227.31  814.38  230.35   815.1  239.46  820.81   242.5  822.23
  248.58  825.85  254.65   828.9  263.77  832.65  266.81  833.11  275.92  837.09
#Mann= 3 , 0 , 0
       0      .1       0  116.21      .1       0  206.04      .1       0
Bank Sta=116.21,206.04
XS Rating Curve= 0 ,0
Exp/Cntr=0.3,0.1

Type RM Length L Ch R = 1 ,11795.76,84.99,91.44,93.72
XS GIS Cut Line= 4
     639284.3077    4315223.2512     639190.1412    4315300.5378
     639174.1293    4315340.5675     639113.6511    4315455.8204
#Sta/Elev= 30
       0  837.12   21.32  832.83   42.64  829.35   48.73  827.79   76.14  822.17
   79.18   821.3   85.28  817.84   88.32  816.74   94.41  812.81   97.46  811.85
  103.55  811.28  112.69  808.95  127.57   809.3  147.69  808.67  156.31  808.35
  164.94   808.6  186.12  807.71  210.34  807.65  219.42  807.88  225.47  808.47
  237.58  811.37  240.61  812.64  246.66  814.45  255.74  820.46   261.8  823.83
  279.96  831.24  282.98  831.83  286.01  833.05  292.07  836.06  295.09  837.93
#Mann= 3 , 0 , 0
       0      .1       0  147.69      .1       0  225.47      .1       0
Bank Sta=147.69,225.47
XS Rating Curve= 0 ,0
Exp/Cntr=0.3,0.1

Type RM Length L Ch R = 1 ,11704.32,67.3,91.44,99.79
XS GIS Cut Line= 5
      639203.345    4315166.8948     639140.4574    4315232.6388
     639134.8466    4315237.0563     639089.8141    4315304.6054
     639039.0384    4315405.8141
#Sta/Elev= 30
       0  838.39   12.13  833.08   21.23  829.73   42.46  825.42   60.65  820.43
   63.69  819.14   66.72     817   72.78  811.02   75.82  809.23   87.95  808.53
   93.36  807.61   98.12  806.74  122.17  807.49  146.23  807.69  161.26  807.54
  167.28  806.89  173.29  806.76  182.36  807.34  194.61  807.53  212.97  806.52
  216.03  806.83  219.09  808.01  222.15  809.06  231.33  813.18  240.51  817.65
  243.57  818.13  258.87  824.71  277.23  831.56  283.35  832.67  292.54  837.06
#Mann= 3 , 0 , 0
       0      .1       0   93.36      .1       0  219.09      .1       0
Bank Sta=93.36,219.09
XS Rating Curve= 0 ,0
Exp/Cntr=0.3,0.1

Type RM Length L Ch R = 1 ,11612.88,94.63,91.44,83.45
XS GIS Cut Line= 6
     639120.7948    4315114.5072     639080.2976    4315207.3049
     639076.6209    4315219.0564     639038.0767    4315228.9299
     639016.1361    4315233.1018     638927.9132    4315337.5514
#Sta/Elev= 30
       0  837.16    3.07   836.8   30.68  826.26   33.75   825.4   36.82  824.96
   49.09  820.11   52.16  818.27   64.43  808.71    67.5  807.77   85.91  807.77
   111.1   805.3  125.06  804.39  139.42     804   172.9     805  190.88  805.14
  221.26  803.54  227.34  804.24  230.38  805.25  233.41  807.24  236.45  810.12
  239.49  812.27  245.57  815.94  251.64  817.74  260.76  819.93  269.87  822.85
  275.95  825.31   288.1  829.53  294.18  830.54  309.37  835.42  312.41  836.66
#Mann= 3 , 0 , 0
       0      .1       0   111.1      .1       0  230.38      .1       0
Bank Sta=111.1,230.38
XS Rating Curve= 0 ,0
Exp/Cntr=0.3,0.1

Type RM Length L Ch R = 1 ,11521.44,98.29,91.44,88.55
XS GIS Cut Line= 4
     639068.3279     4315076.169     639005.0819    4315147.0783
     638996.4515    4315157.3043     638855.6024    4315294.4507
#Sta/Elev= 30
       0  837.29    3.07  835.82   21.46  828.61   24.52  828.14   27.59  827.21
   36.78  823.48   42.91  819.71   58.24   809.3    61.3  807.47   64.37  806.22
   67.43  805.75   95.02  804.14   108.4  803.28  136.04  804.34  163.69  804.92
   172.9  804.93  188.26  804.39  203.62  802.65  206.69  802.62  209.76  803.04
  212.84  804.01  218.98  806.12  222.05   806.6  234.34  813.61  243.55  818.17
  246.63  819.96  261.98  826.85  265.06  827.98  274.27  829.98  304.99  839.15
#Mann= 3 , 0 , 0
       0      .1       0   95.02      .1       0  212.84      .1       0
Bank Sta=95.02,212.84
XS Rating Curve= 0 ,0
Exp/Cntr=0.3,0.1