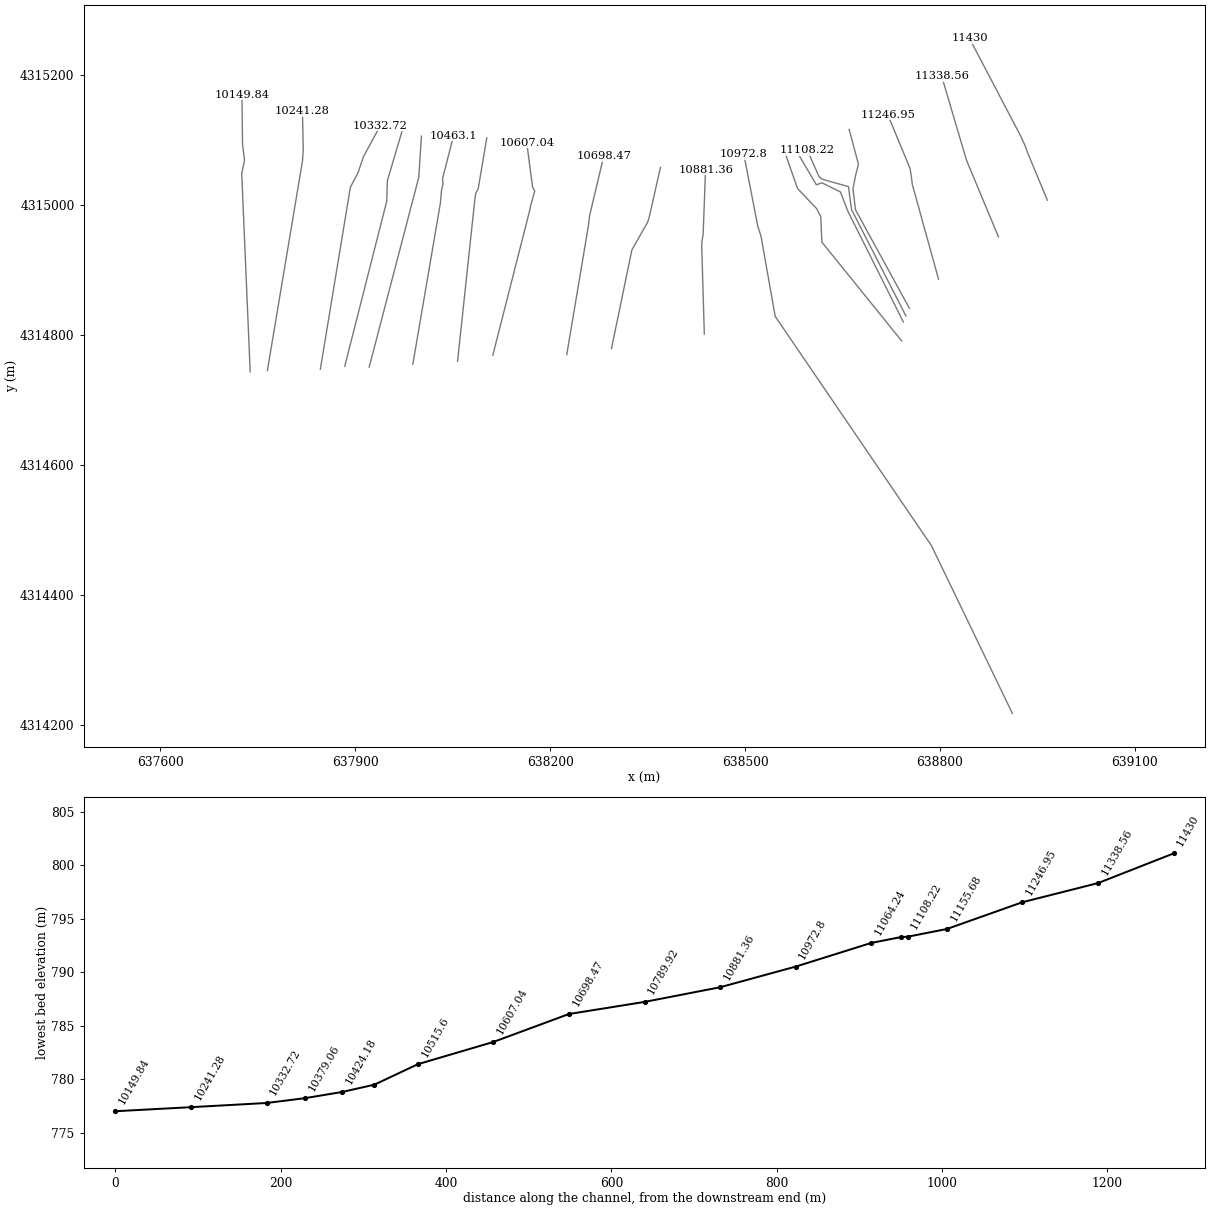
HEC-RAS study RedCreek.prj: RedCreek

--- RedCreek.g01 (geometry) --- (continued)

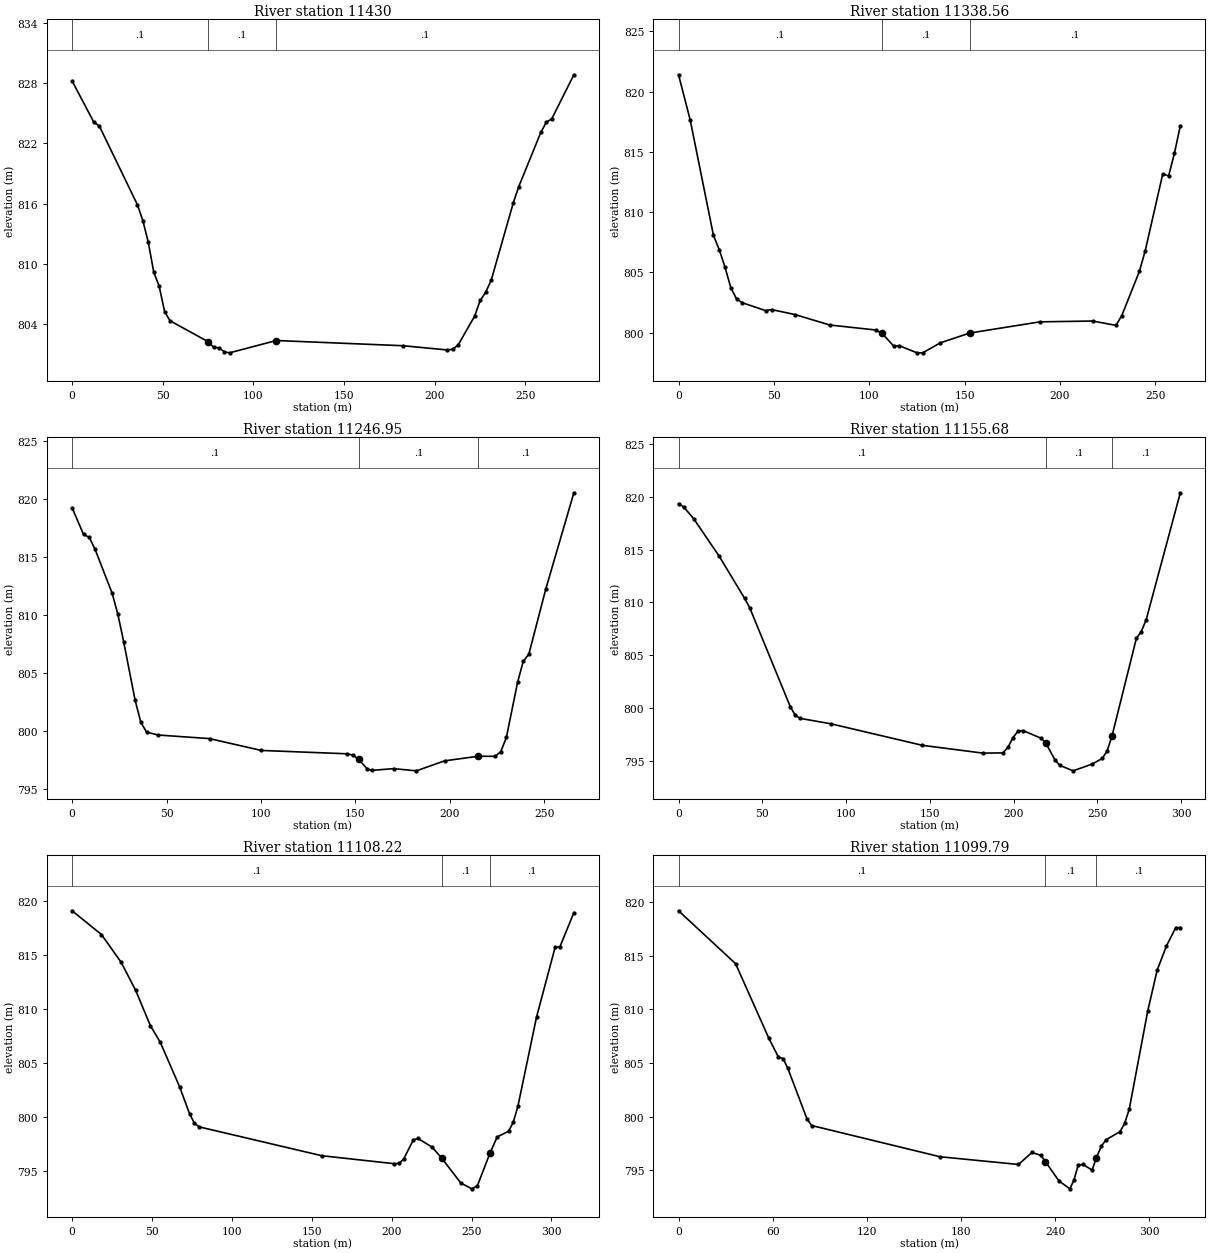
Type RM Length L Ch R = 1 ,11430   ,93.55,91.44,91.24
XS GIS Cut Line= 6
     638965.1402    4315007.9064     638934.0929    4315082.8363
     638931.3214    4315091.0361     638925.9739    4315102.1301
     638924.2963    4315106.3116     638845.2837    4315257.1444
#Sta/Elev= 30
       0  828.25   12.02  824.12   15.02  823.75   36.05  815.88   39.05   814.3
   42.06  812.13   45.06  809.15   48.06  807.74   51.07   805.2   54.07  804.29
    75.1   802.2    78.1  801.64   81.11  801.59   83.99  801.19   86.88  801.09
  112.67  802.32   182.6   801.8  206.92  801.38  209.97  801.44  213.01  801.88
  222.13  804.76  225.17  806.32  228.21  807.14  231.25  808.34  243.41  816.05
  246.45  817.69  258.62   823.1  261.66  824.12   264.7  824.47  276.86  828.86
#Mann= 3 , 0 , 0
       0      .1       0    75.1      .1       0  112.67      .1       0
Bank Sta=75.1,112.67
XS Rating Curve= 0 ,0
Exp/Cntr=0.3,0.1

Type RM Length L Ch R = 1 ,11338.56,94.3,91.61,89.08
XS GIS Cut Line= 3
      638889.921    4314951.4408     638840.6528    4315069.6549
     638802.4211    4315199.2005
#Sta/Elev= 30
       0  821.39     6.1  817.65    18.3  808.07   21.35  806.88   24.39  805.42
   27.44  803.71   30.49  802.78   33.54  802.47   45.74  801.82   48.79  801.91
   60.99   801.5   79.28  800.63  103.68  800.21  106.73  799.93  112.82  798.89
  115.87  798.91  125.02  798.32  128.07  798.32  137.28  799.15  152.63  799.96
  189.47  800.89  217.09  800.96  229.37   800.6  232.44  801.41  241.65  805.07
  244.72  806.78  253.93  813.17     257     813  260.07  814.89  263.14  817.17
#Mann= 3 , 0 , 0
       0      .1       0  106.73      .1       0  152.63      .1       0
Bank Sta=106.73,152.63
XS Rating Curve= 0 ,0
Exp/Cntr=0.3,0.1

Type RM Length L Ch R = 1 ,11246.95,93.07,91.27,83.67
XS GIS Cut Line= 5
      638797.738    4314886.2243     638757.3143    4315032.3452
     638756.2541    4315041.7003     638753.8728    4315056.7816
     638719.7188    4315139.2987
#Sta/Elev= 30
       0  819.23    6.06  816.92     9.1  816.66   12.13  815.65   21.23  811.84
   24.26  810.02   27.29  807.68   33.35  802.63   36.39  800.72   39.42  799.87
   45.48  799.62   72.77  799.31  100.06  798.29  145.54     798  148.58  797.89
  151.61  797.53  156.32  796.68  158.67  796.57  170.19  796.72  182.25  796.53
  197.13  797.39  214.99  797.79  223.92  797.78   226.9  798.18  229.88  799.41
  235.83  804.18  238.81  805.97  241.78   806.6  250.71  812.19   265.6  820.51
#Mann= 3 , 0 , 0
       0      .1       0  151.61      .1       0  214.99      .1       0
Bank Sta=151.61,214.99
XS Rating Curve= 0 ,0
Exp/Cntr=0.3,0.1

Type RM Length L Ch R = 1 ,11155.68,6.22,47.46,62.14
XS GIS Cut Line= 6
     638752.7918    4314841.6419     638669.8939     4314993.158
     638666.0588    4315025.7175     638670.3731    4315047.3336
     638674.4564    4315063.2851     638660.1874    4315116.8091
#Sta/Elev= 30
       0  819.34    3.03  819.06    9.09  817.92   24.24  814.38   39.39  810.39
   42.42  809.51   66.66  800.12   69.69  799.28   72.72     799    90.9  798.49
  145.44  796.45  181.65  795.71  193.57  795.73  196.55  796.26  199.53  797.16
  202.52  797.79   205.5  797.85  216.52  797.11  219.27  796.63  224.78  795.02
  227.54  794.55  235.43  794.03  246.95  794.68  252.78   795.2   255.7   795.9
  258.61   797.3  273.19  806.58   276.1  807.23  279.02  808.34  299.43  820.39
#Mann= 3 , 0 , 0
       0      .1       0  219.27      .1       0  258.61      .1       0
Bank Sta=219.27,258.61
XS Rating Curve= 0 ,0
Exp/Cntr=0.3,0.1

Type RM Length L Ch R = 1 ,11108.22,9.74,8.44,11.07
XS GIS Cut Line= 6
     638747.5001    4314829.7356     638663.8491    4314993.4577
     638659.0865    4315028.7797       638618.51    4315040.3049
     638613.7475    4315044.4324     638595.9706    4315084.4549
#Sta/Elev= 30
       0  819.09   18.39  816.89   30.64  814.33   39.84   811.7   49.03  808.43
   55.16  806.91   67.41  802.73   73.54  800.26   76.61  799.38   79.67  799.05
  156.28  796.38  201.68  795.64  204.65  795.66  207.62  796.11  213.56  797.85
  216.53  797.98  225.44  797.16  231.38  796.14  243.27  793.85   250.2  793.31
  253.61  793.59  261.56  796.64     266  798.12  273.12  798.65  276.04  799.47
  278.96  800.95  290.64  809.23  302.32  815.73  305.24  815.74     314  818.91
#Mann= 3 , 0 , 0
       0      .1       0  231.38      .1       0  261.56      .1       0
Bank Sta=231.38,261.56
XS Rating Curve= 0 ,0
Exp/Cntr=0.3,0.1

Type RM Length L Ch R = 1 ,11099.79,46.88,35.54,26.33
XS GIS Cut Line= 6
     638743.5313    4314820.4752     638658.0944    4314991.1426
     638646.8495    4315020.5776     638618.1422    4315034.7328
     638609.8078    4315031.5578      638581.306    4315079.9955
#Sta/Elev= 30
       0  819.18   36.35  814.25   57.56   807.3   63.62  805.55   66.65   805.4
   69.68  804.49    81.8  799.81   84.83  799.17  166.62  796.26  216.64  795.54
  225.22  796.66  230.93  796.38  233.79  795.81  242.35  794.02  249.36  793.27
     252  794.09  254.65  795.46  257.62  795.55  263.57  795.02  266.27  796.18
  269.48  797.26  272.44  797.84  281.31   798.6  284.27  799.36  287.23   800.7
  299.06  809.88  304.98  813.63  310.89  815.89  316.81   817.6  319.77  817.62
#Mann= 3 , 0 , 0
       0      .1       0  233.79      .1       0  266.27      .1       0
Bank Sta=233.79,266.27
XS Rating Curve= 0 ,0
Exp/Cntr=0.3,0.1

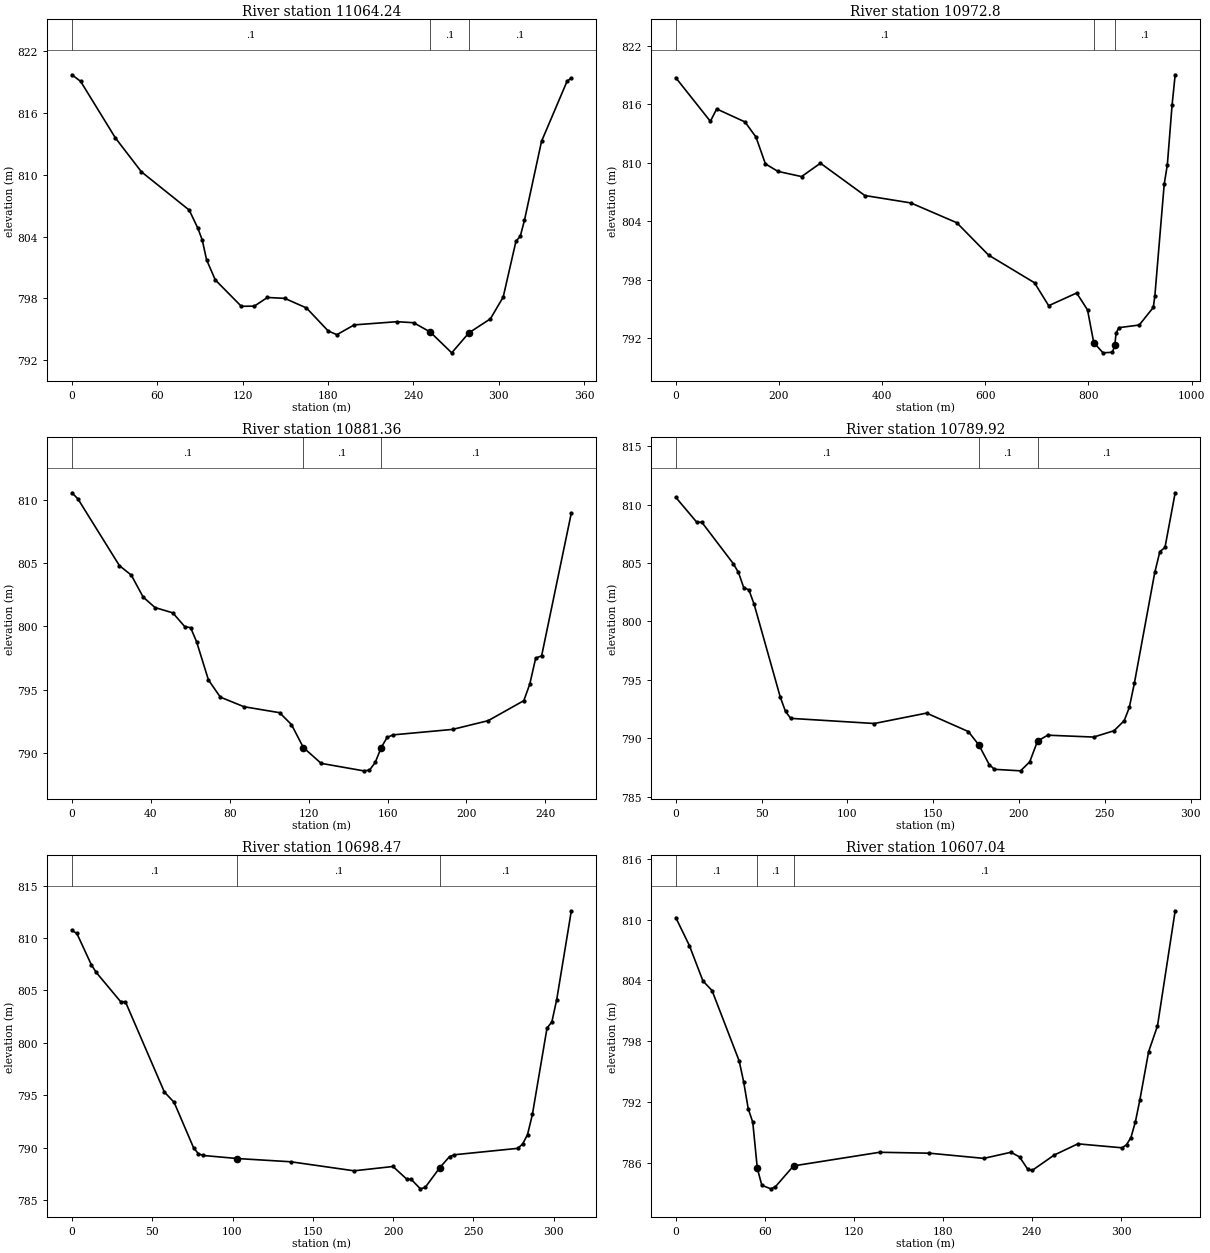
Type RM Length L Ch R = 1 ,11064.24,99.14,91.44,83.53
XS GIS Cut Line= 6
     638740.8855     4314791.371     638618.1501    4314943.4321
     638616.5687    4314982.5185     638609.9515    4314995.1748
       638580.76    4315025.9027     638560.9685    4315082.4132
#Sta/Elev= 30
       0  819.69    6.11  819.05   30.53  813.57   48.85  810.28   82.44  806.57
   88.55   804.8    91.6  803.67   94.65  801.75  100.76   799.8  119.08  797.24
  128.24  797.26   137.4   798.1  149.61  798.01  164.88  797.08  180.15  794.85
  186.25  794.49  198.42  795.44  228.51  795.75  240.24  795.65  251.84  794.75
  266.98  792.73  279.09  794.67  294.19  796.03  303.17  798.14  312.15  803.56
  315.15  804.02  318.14   805.6  330.12  813.24  348.08  819.07  351.07  819.38
#Mann= 3 , 0 , 0
       0      .1       0  251.84      .1       0  279.09      .1       0
Bank Sta=251.84,279.09
XS Rating Curve= 0 ,0
Exp/Cntr=0.3,0.1

Type RM Length L Ch R = 1 ,10972.8 ,94.77,91.44,83.51
XS GIS Cut Line= 6
     638911.2775    4314217.7531     638786.8752    4314475.8692
     638546.3529    4314829.0512     638524.6197    4314952.1149
      638519.495    4314968.3478     638498.1739    4315078.3563
#Sta/Elev= 30
       0  818.71   67.06  814.24   79.25  815.51  134.12  814.18  155.46  812.63
  173.75  809.88  198.13  809.11  243.86  808.58  280.43  809.95  366.46  806.64
  455.61  805.88  544.76  803.85  606.24  800.54  695.39   797.7  722.87  795.35
  777.09  796.65  798.17  794.92  810.22  791.57  828.29  790.52  846.49  790.58
  851.09  791.33  853.55  792.55  859.03   793.1  898.41  793.37  925.66  795.17
  928.69  796.36  946.86  807.83  952.92   809.8  962.01  815.87  968.06  819.01
#Mann= 3 , 0 , 0
       0      .1       0  810.22      .1       0  851.09      .1       0
Bank Sta=810.22,851.09
XS Rating Curve= 0 ,0
Exp/Cntr=0.3,0.1

Type RM Length L Ch R = 1 ,10881.36,99.77,91.44,85.78
XS GIS Cut Line= 5
     638437.3196    4314801.8661     638433.3168     4314937.158
     638433.5758    4314943.7624     638435.5079     4314955.401
     638439.2036    4315054.7268
#Sta/Elev= 30
       0  810.54    3.01  810.06   24.06  804.79   30.08  804.04   36.09  802.31
   42.11  801.48   51.13  801.06   57.15  799.98   60.16  799.89   63.16  798.79
   69.18  795.77    75.2  794.41   87.23  793.65  105.27  793.18  111.29  792.24
   117.3  790.43  126.33  789.18  147.86  788.59  150.81  788.64  153.76  789.26
  156.77  790.43  159.78  791.23  162.79  791.43  192.91  791.86  210.99  792.55
  229.06  794.13  232.07  795.43  235.08  797.49  238.09  797.67  253.15  808.95
#Mann= 3 , 0 , 0
       0      .1       0   117.3      .1       0  156.77      .1       0
Bank Sta=117.3,156.77
XS Rating Curve= 0 ,0
Exp/Cntr=0.3,0.1

Type RM Length L Ch R = 1 ,10789.92,92.24,91.45,90.06
XS GIS Cut Line= 5
     638294.4443    4314779.3765     638325.8923    4314931.4561
     638349.9602    4314973.7978     638352.1619    4314980.2867
     638369.8507    4315058.5125
#Sta/Elev= 30
       0  810.62   12.18   808.5   15.23  808.48    33.5  804.95   36.54  804.19
   39.59   802.9   42.63   802.7   45.68  801.46    60.9  793.53   63.95   792.3
   66.99  791.71  115.71  791.27  146.16  792.16  170.52  790.58  176.61  789.44
  182.69  787.75  185.74  787.35  200.96  787.22  206.29  787.99  210.85  789.77
  216.79  790.27  243.53  790.11  255.41  790.65  261.35  791.51  264.32  792.64
  267.29  794.73  279.17   804.2  282.14  805.98  285.11  806.33  291.05  811.01
#Mann= 3 , 0 , 0
       0      .1       0  176.61      .1       0  210.85      .1       0
Bank Sta=176.61,210.85
XS Rating Curve= 0 ,0
Exp/Cntr=0.3,0.1

Type RM Length L Ch R = 1 ,10698.47,96.83,91.43,99.24
XS GIS Cut Line= 4
     638225.6525    4314770.1161     638258.7438    4314967.2949
     638260.8041    4314984.2422     638282.5381    4315075.7104
#Sta/Elev= 30
       0  810.72    3.03  810.45   12.12  807.44   15.15  806.72   30.29  803.94
   33.32  803.92   57.56  795.32   63.62  794.34   75.73  790.01   78.76  789.43
   81.79  789.27     103  788.98  136.32  788.67   175.7  787.81  199.94  788.22
  208.47  787.02  211.32  786.99  217.01  786.09  220.04  786.23  229.14  788.12
   235.2  789.17  238.24  789.34  277.66  789.95   280.7  790.37  283.73  791.26
  286.76  793.18  295.86  801.41  298.89  802.01  301.92  804.14  311.02   812.6
#Mann= 3 , 0 , 0
       0      .1       0     103      .1       0  229.14      .1       0
Bank Sta=103,229.14
XS Rating Curve= 0 ,0
Exp/Cntr=0.3,0.1

Type RM Length L Ch R = 1 ,10607.04,85.73,91.44,82.27
XS GIS Cut Line= 6
     638111.8815    4314769.1239     638168.3256    4314990.9591
     638169.9895    4314999.0375     638176.3681    4315022.0152
     638173.0186    4315028.1272     638164.1368    4315096.1054
#Sta/Elev= 30
       0  810.19    9.16  807.44   18.31  803.95   24.42  803.01   42.73  796.07
   45.78  793.99   48.83  791.36   51.88  790.04   54.94   785.5   57.99  783.83
   64.09  783.48   67.15  783.69   79.35  785.74  137.34  787.08  170.91  786.99
  207.54  786.48  225.85  787.08  231.65  786.62  237.15  785.42  240.13  785.29
  255.04  786.81  270.95  787.91  300.76  787.52  303.74  787.83  306.72  788.53
   309.7  790.07  312.68   792.2  318.64  796.99   324.6  799.52  336.52  810.86
#Mann= 3 , 0 , 0
       0      .1       0   54.94      .1       0   79.35      .1       0
Bank Sta=54.94,79.35
XS Rating Curve= 0 ,0
Exp/Cntr=0.3,0.1

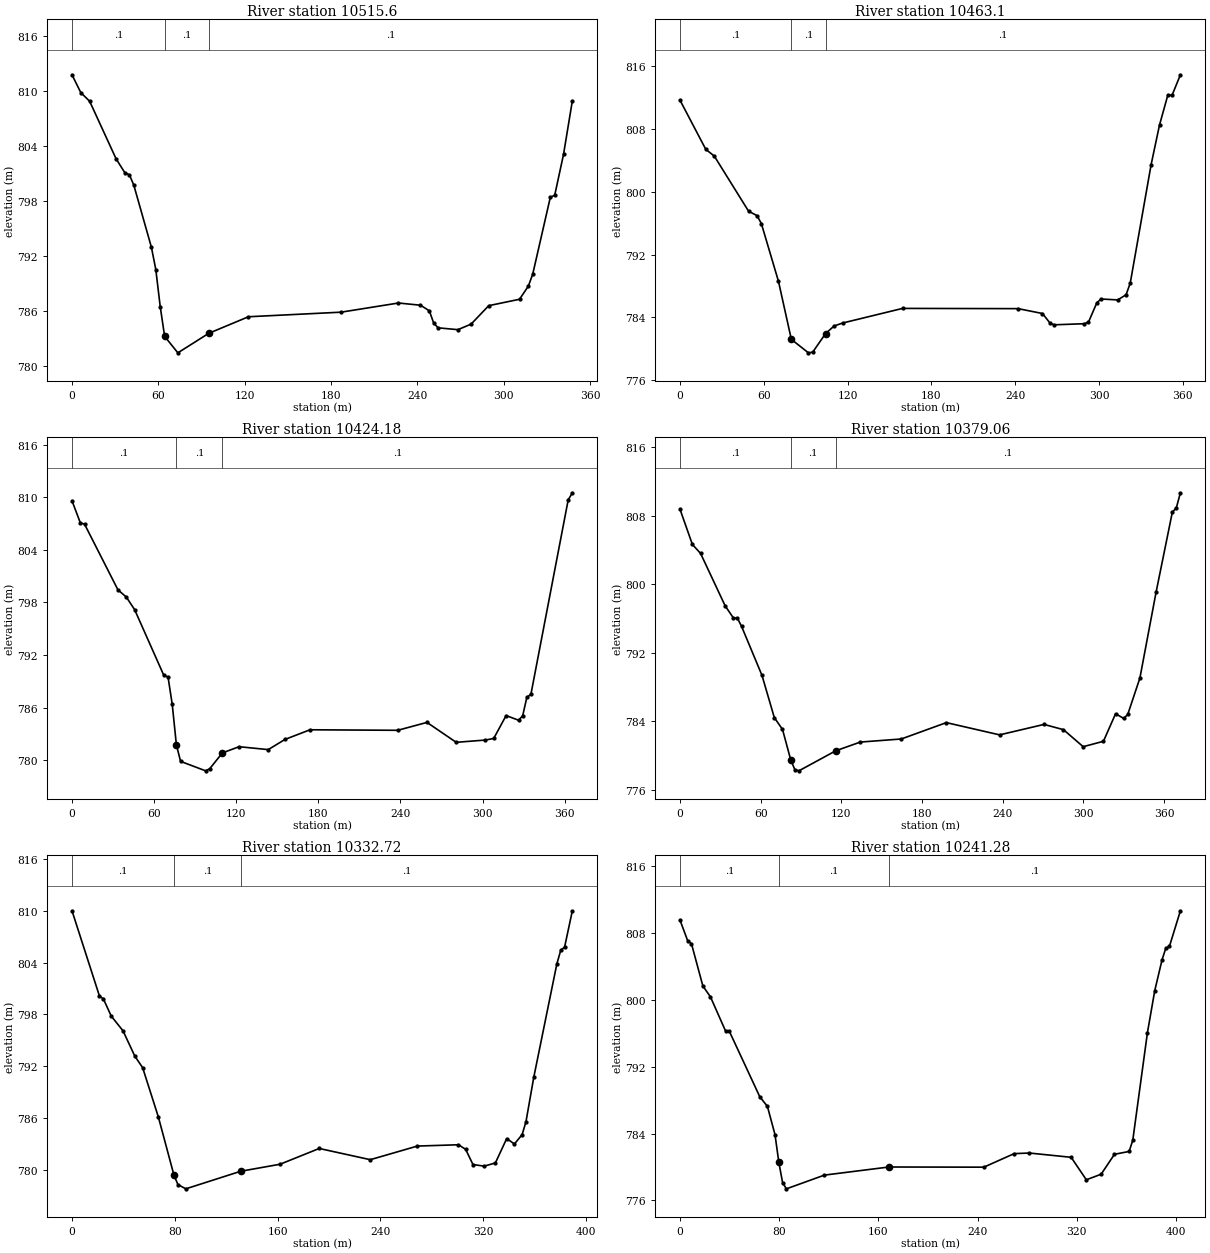
Type RM Length L Ch R = 1 ,10515.6 ,52.28,52.5,58.26
XS GIS Cut Line= 5
     638057.6418    4314759.8634     638084.6204    4315012.7649
     638085.6659    4315018.6249     638089.3881    4315025.4866
      638102.621    4315103.8225
#Sta/Elev= 30
       0  811.76    6.13  809.81   12.26  808.87   30.64  802.58   36.77  801.05
   39.84  800.84    42.9  799.73   55.16  792.93   58.22  790.49   61.29  786.44
   64.35   783.2   73.54   781.4   94.99  783.53  122.57  785.34  186.92  785.84
  226.76  786.84  242.08   786.6  248.21  785.99  251.27  784.64  254.34  784.13
   268.1  783.93  277.26  784.54  289.48  786.55  310.87  787.25  316.99  788.68
  320.04  789.99  332.26  798.38  335.32  798.61  341.43  803.06  347.54  808.89
#Mann= 3 , 0 , 0
       0      .1       0   64.35      .1       0   94.99      .1       0
Bank Sta=64.35,94.99
XS Rating Curve= 0 ,0
Exp/Cntr=0.3,0.1

Type RM Length L Ch R = 1 ,10463.1 ,41.7,38.92,38.55
XS GIS Cut Line= 6
     637988.7996    4314755.2257     638031.1331    4315002.8762
     638032.8529    4315022.0585     638035.2341    4315033.5679
     638034.4404    4315040.7116      638051.506    4315107.3868
#Sta/Elev= 30
       0  811.65   18.38  805.42   24.51  804.55   49.02  797.54   55.15  796.96
   58.21  795.95   70.47  788.59   79.66  781.21   91.92  779.49   94.98  779.58
  104.17  781.94   110.3  782.91  116.43  783.29  159.32  785.15  242.05  785.12
   259.5   784.5     265  783.26  267.75  783.06  289.44   783.2  292.44   783.4
  298.42  785.86  301.41  786.35  313.38  786.23  319.37  786.89  322.36  788.38
  337.32  803.48  343.31  808.51  349.29  812.34  352.28  812.29  358.27  814.91
#Mann= 3 , 0 , 0
       0      .1       0   79.66      .1       0  104.17      .1       0
Bank Sta=79.66,104.17
XS Rating Curve= 0 ,0
Exp/Cntr=0.3,0.1

Type RM Length L Ch R = 1 ,10424.18,44.53,45.12,42.73
XS GIS Cut Line= 3
     637921.6457    4314750.9205     637997.9618    4315043.1754
     638002.0792    4315106.5212
#Sta/Elev= 30
       0  809.59     6.1  807.07    9.15  806.93   33.56  799.44   39.66  798.62
   45.77  797.18   67.12  789.68   70.17  789.51   73.23  786.39   76.28  781.76
   79.33  779.89   97.63  778.81  100.68  779.06  109.84  780.85  122.04  781.56
   143.4  781.23   155.6  782.39  173.91  783.49  237.98  783.43  259.34  784.33
   280.7  782.06  302.05  782.32   308.1   782.5  317.17  785.11  326.24  784.58
  329.26  785.08  332.28  787.17  335.31  787.55  362.51  809.68  365.53   810.5
#Mann= 3 , 0 , 0
       0      .1       0   76.28      .1       0  109.84      .1       0
Bank Sta=76.28,109.84
XS Rating Curve= 0 ,0
Exp/Cntr=0.3,0.1

Type RM Length L Ch R = 1 ,10379.06,56.2,46.34,45.43
XS GIS Cut Line= 4
     637884.0685    4314752.2711      637948.627    4315006.2716
     637949.6853    4315038.0217     637971.9104    4315113.1635
#Sta/Elev= 30
       0  808.75    9.14  804.67   15.24  803.62   33.52   797.5   39.62  796.09
   42.66  796.05   45.71  795.11   60.95  789.37   70.09  784.45   76.19  783.07
   82.28  779.53   85.33  778.38   88.37  778.23   115.8  780.57  134.09  781.59
  164.56  781.95  198.08  783.86   237.7  782.43  270.74  783.65  285.18  783.04
  299.87  781.05  314.94  781.68  323.98   784.9  330.01  784.35  333.02  784.81
  342.07  789.07  354.12   799.1  366.18  808.42  369.19  808.95   372.2   810.7
#Mann= 3 , 0 , 0
       0      .1       0   82.28      .1       0   115.8      .1       0
Bank Sta=82.28,115.8
XS Rating Curve= 0 ,0
Exp/Cntr=0.3,0.1

Type RM Length L Ch R = 1 ,10332.72,85.61,91.44,97.24
XS GIS Cut Line= 5
     637846.5038    4314747.7455     637892.7282    4315027.9384
     637904.4348    4315050.1024     637912.8127    4315074.8871
      637938.579    4315122.3962
#Sta/Elev= 30
       0  810.02   21.37  800.13   24.43   799.8   30.54  797.81    39.7   796.1
   48.86  793.17   54.96  791.83   67.18  786.12   79.39  779.33   82.45  778.27
   88.55  777.78   131.3  779.82  161.84  780.63  192.37  782.46  232.07  781.16
  268.71  782.74  300.69  782.89  306.26  782.36  311.95   780.6  320.67  780.41
  329.39  780.78  338.21  783.61  344.22  782.98  350.22  784.07  353.22  785.58
  359.23  790.69  377.24  803.87  380.25  805.44  383.25  805.81  389.25     810
#Mann= 3 , 0 , 0
       0      .1       0   79.39      .1       0   131.3      .1       0
Bank Sta=79.39,131.3
XS Rating Curve= 0 ,0
Exp/Cntr=0.3,0.1

Type RM Length L Ch R = 1 ,10241.28,93.31,91.44,93.42
XS GIS Cut Line= 5
      637765.012    4314745.6288     637819.1006    4315068.8026
     637820.2389    4315086.6906     637820.0667    4315091.4555
     637818.9871    4315144.6213
#Sta/Elev= 30
       0  809.49    6.12  807.05    9.19  806.69   18.37  801.64    24.5  800.34
   36.75  796.23   39.81   796.2   64.31  788.39   70.43  787.25   76.56  783.87
   79.62  780.59   82.68  778.13   85.75  777.39  116.37  779.03  168.43     780
  244.99  779.98  269.48   781.6  281.73  781.67  315.42  781.16  327.67  778.47
  339.62  779.14  350.36  781.52  362.18  781.86  365.13   783.2  376.95  796.06
  382.86  801.09  388.77  804.79  391.72  806.13  394.68  806.37  403.54  810.63
#Mann= 3 , 0 , 0
       0      .1       0   79.62      .1       0  168.43      .1       0
Bank Sta=79.62,168.43
XS Rating Curve= 0 ,0
Exp/Cntr=0.3,0.1

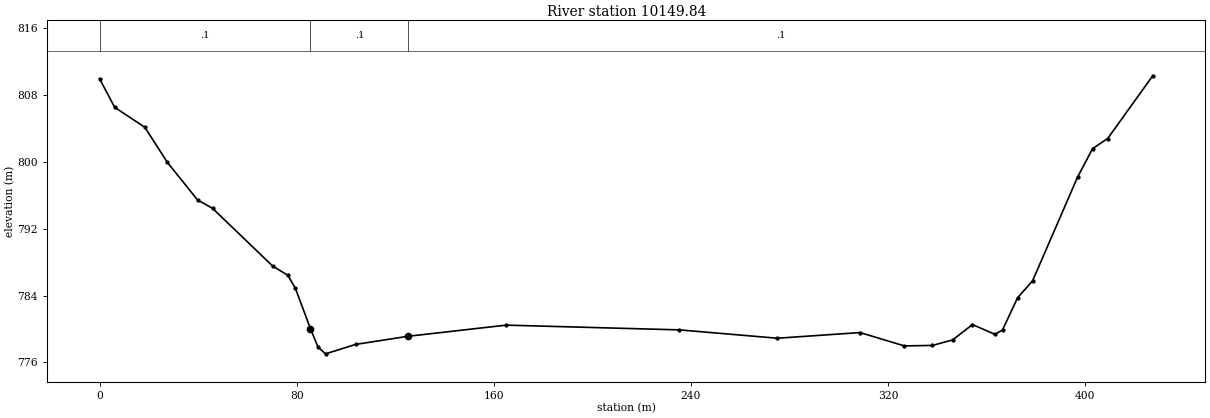
Type RM Length L Ch R = 1 ,10149.84,94.95,91.44,99.54
XS GIS Cut Line= 6
     637738.5536    4314743.5122     637725.5429     4315048.882
     637729.8632    4315069.3972     637727.7218    4315086.3941
     637726.7865    4315093.8179     637725.8536    4315170.0213
#Sta/Elev= 30
       0  809.96    6.11  806.55   18.34  804.16   27.51  799.95   39.73  795.45
   45.85  794.44    70.3  787.51   76.41  786.42   79.47  784.85   85.58  780.01
   88.64  777.82   91.69  777.01  103.92  778.14  125.32  779.12  165.05  780.45
  235.35  779.88  275.08  778.88  308.64  779.56  326.61  777.96  338.03  778.02
  346.24  778.68  354.27  780.52  363.42  779.34  366.47  779.88  372.56  783.72
  378.66  785.76  396.95  798.21  403.05  801.61  409.14  802.81  427.44  810.33
#Mann= 3 , 0 , 0
       0      .1       0   85.58      .1       0  125.32      .1       0
Bank Sta=85.58,125.32
XS Rating Curve= 0 ,0
Exp/Cntr=0.3,0.1