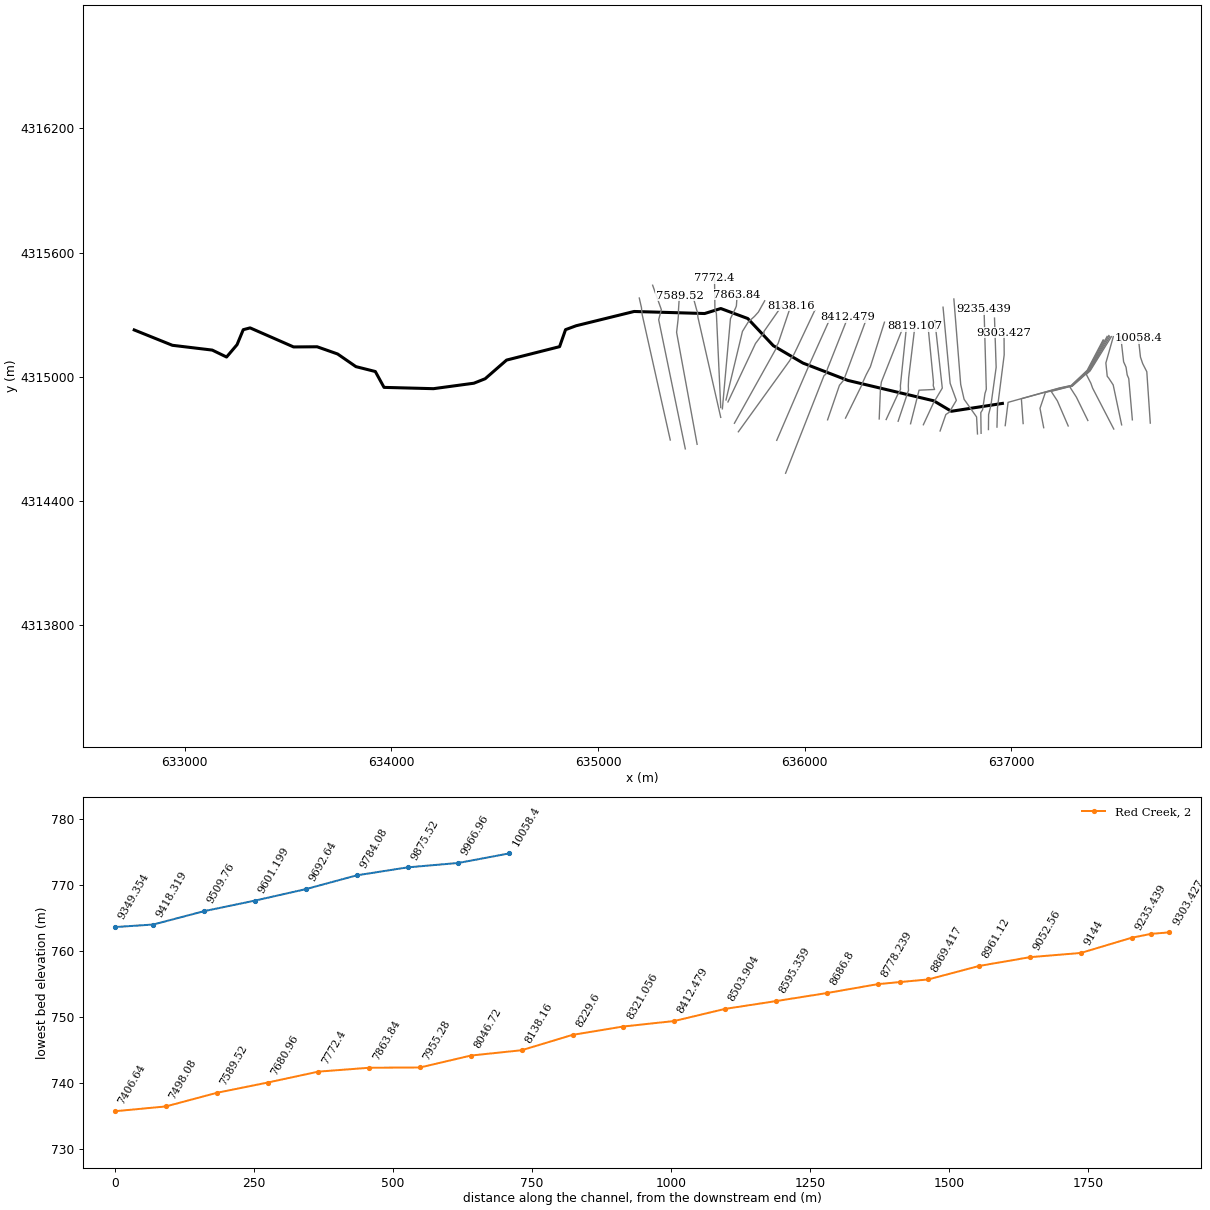
HEC-RAS study RedCreek.prj: RedCreek

--- RedCreek.g01 (geometry) --- (continued)

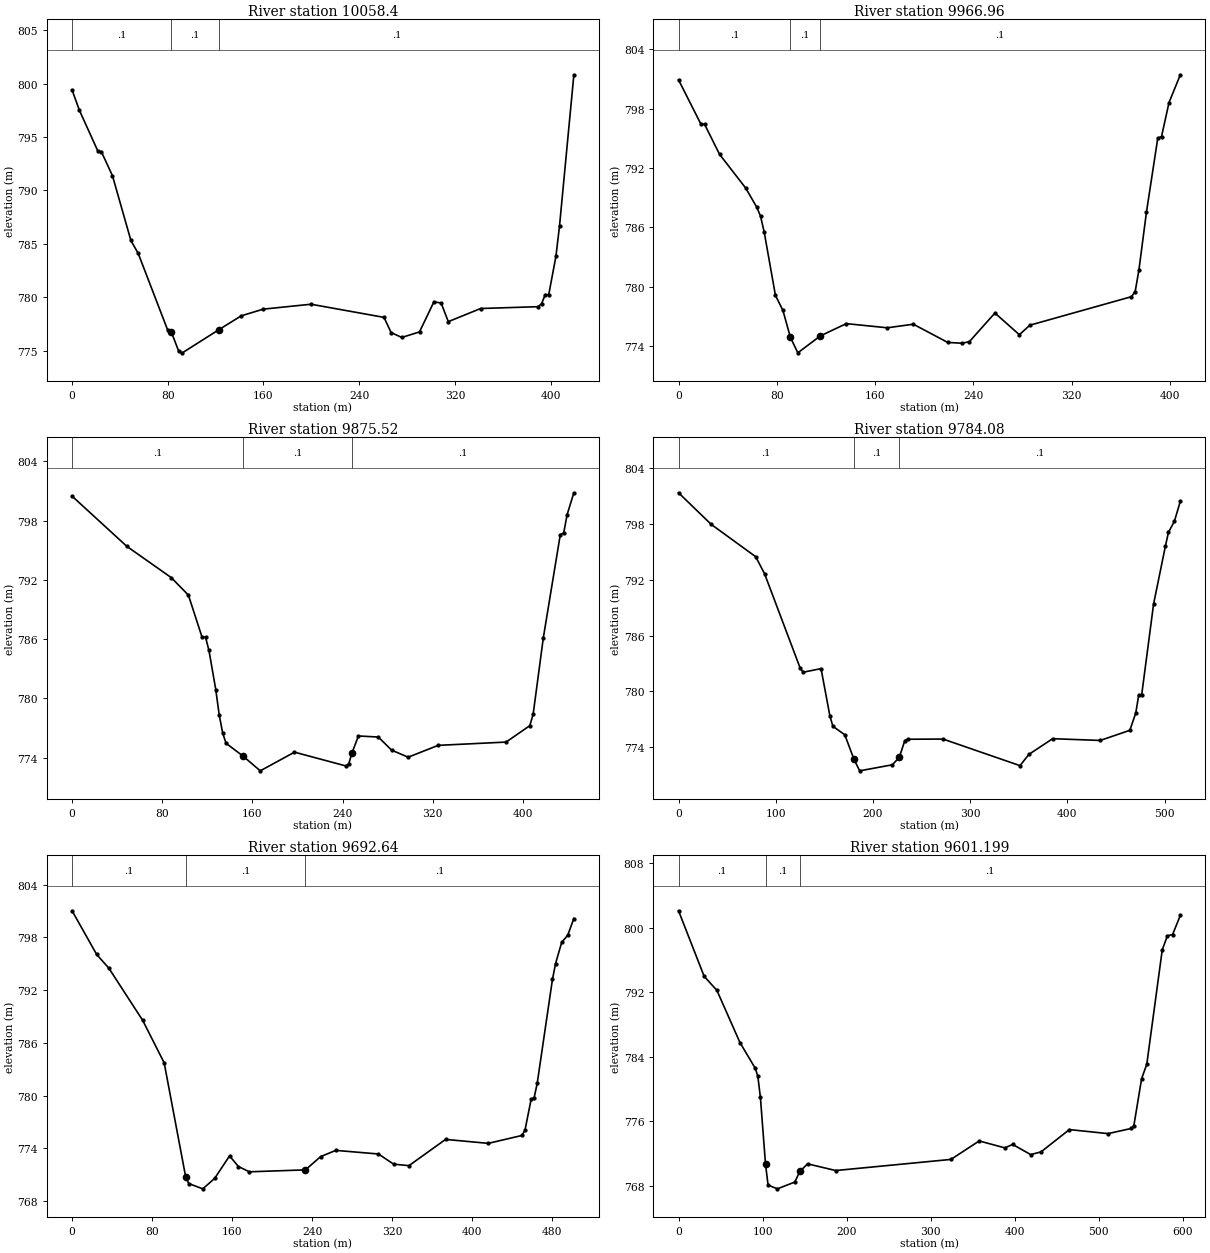
Type RM Length L Ch R = 1 ,10058.4 ,98.45,91.44,83.21
XS GIS Cut Line= 5
     637671.8785    4314775.2622     637655.0172    4315023.5429
     637634.9569     4315063.285     637624.3065    4315094.6704
     637614.1361     4315187.006
#Sta/Elev= 30
       0   799.4    6.14  797.49   21.51  793.69   24.58   793.6   33.79  791.36
   49.16  785.31    55.3  784.09   79.88  776.93   82.95  776.75    89.1  774.95
   92.17  774.79  122.89  776.97  141.32  778.25  159.76  778.88   199.7  779.34
  260.72  778.11  266.66  776.69  275.56  776.23   290.4  776.75  302.41  779.56
  308.44  779.46  314.46  777.71   341.5  778.94  389.44  779.11  392.44  779.39
  395.44  780.23  398.43  780.25  404.42  783.82  407.42  786.67  419.41  800.82
#Mann= 3 , 0 , 0
       0      .1       0   82.95      .1       0  122.89      .1       0
Bank Sta=82.95,122.89
XS Rating Curve= 0 ,0
Exp/Cntr=0.3,0.1

Type RM Length L Ch R = 1 ,9966.96 ,86.95,91.44,93.01
XS GIS Cut Line= 6
      637585.095    4314791.1372     637567.6988    4314990.6228
     637560.1291    4315007.9284     637554.4696    4315045.6563
     637542.8279    4315071.5855     637529.0032    4315193.3047
#Sta/Elev= 30
       0  800.91    18.2  796.44   21.24  796.41   33.37  793.39   54.61  789.99
   63.71  788.04   66.75  787.14   69.78   785.5   78.88  779.14   84.95  777.63
   91.02  774.92   97.09  773.34  115.29  775.04  136.53  776.29   169.9  775.87
  191.14  776.23  219.13  774.39  230.87  774.31  236.74  774.47  257.52  777.36
  277.41  775.17  285.94  776.13  368.63  779.01  371.69  779.53  374.75  781.72
  380.88  787.56  390.07  795.01  393.13  795.18  399.25  798.62  408.44  801.42
#Mann= 3 , 0 , 0
       0      .1       0   91.02      .1       0  115.29      .1       0
Bank Sta=91.02,115.29
XS Rating Curve= 0 ,0
Exp/Cntr=0.3,0.1

Type RM Length L Ch R = 1 ,9875.52 ,97.97,91.44,99.3
XS GIS Cut Line= 6
     637533.2366    4314766.7955     637492.3745    4314959.8626
     637470.3777    4314993.2842     637463.5348    4315001.6668
     637456.9202    4315065.9607     637493.0198    4315193.3047
#Sta/Elev= 30
       0  800.47   48.58  795.39   88.05  792.22  103.23  790.45  115.37  786.18
  118.41  786.19  121.44  784.86  127.51  780.88  130.55  778.34  133.59  776.51
  136.62  775.46   151.8  774.15  166.98  772.67  197.34  774.56   242.8  773.17
   245.5  773.38  248.21  774.44  254.08   776.2  271.71  776.09  283.46  774.77
  298.15  774.05  324.87  775.25  385.04  775.58   406.1  777.24   409.1  778.41
  418.13  786.15  433.17  796.58  436.18  796.73  439.19  798.59   445.2  800.81
#Mann= 3 , 0 , 0
       0      .1       0   151.8      .1       0  248.21      .1       0
Bank Sta=151.8,248.21
XS Rating Curve= 0 ,0
Exp/Cntr=0.3,0.1

Type RM Length L Ch R = 1 ,9784.08 ,89.96,91.44,97.66
XS GIS Cut Line= 6
     637495.1365    4314746.6872     637392.6499    4314944.6339
     637384.3449    4314967.9985     637362.1198    4315011.1257
     637380.3761    4315027.2653     637483.4948    4315193.3047
#Sta/Elev= 30
       0  801.38   33.59  797.98   79.39   794.5   88.55  792.65  125.19  782.49
  128.25  782.07  146.57  782.46  155.73  777.34  158.78  776.25     171  775.34
  180.16  772.78  186.26  771.46  219.85  772.11  227.06  772.91  232.76  774.72
  235.61  774.86  272.04  774.88   351.2  772.02  360.36  773.23   384.8  774.92
  433.66  774.73   464.2  775.82  470.31  777.69  473.36  779.64  476.42  779.67
  488.63  789.42  500.85  795.68   503.9  797.12  510.01  798.31  516.12  800.46
#Mann= 3 , 0 , 0
       0      .1       0  180.16      .1       0  227.06      .1       0
Bank Sta=180.16,227.06
XS Rating Curve= 0 ,0
Exp/Cntr=0.3,0.1

Type RM Length L Ch R = 1 ,9692.64 ,93.06,91.44,91.88
XS GIS Cut Line= 6
     637369.6973    4314787.9755     637314.2215    4314900.9071
     637282.2124    4314950.6811     637293.6424    4314953.2211
     637377.8198     4315027.802     637475.7425    4315193.3047
#Sta/Elev= 30
       0  801.04   24.55  796.07   36.83  794.49   70.58  788.56   92.06  783.72
  113.55  770.73  116.62  769.97  130.65  769.37  142.53  770.56  157.38  773.12
  166.29  771.91  177.15  771.31  233.23  771.53  248.42  773.04  263.62  773.75
  306.17  773.34  321.42  772.18  336.69  772.01  373.31     775  416.05  774.55
  449.63  775.45  452.68  776.05  458.78  779.55  461.83  779.75  464.89  781.39
  480.15  793.24   483.2  795.01  489.31  797.43  495.41  798.26  501.52  800.16
#Mann= 3 , 0 , 0
       0      .1       0  113.55      .1       0  233.23      .1       0
Bank Sta=113.55,233.23
XS Rating Curve= 0 ,0
Exp/Cntr=0.3,0.1

Type RM Length L Ch R = 1 ,9601.199,94.65,91.44,51.35
XS GIS Cut Line= 6
     637274.6587    4314761.5039     637222.1814    4314882.9098
     637192.1787    4314928.8233     637292.3854    4314954.2476
     637376.6799    4315029.9001     637471.5091    4315198.5964
#Sta/Elev= 30
       0  802.12   30.46     794    45.7  792.24   73.11  785.78   91.39  782.57
   94.44  781.57   97.48  778.96  103.58  770.65  106.62  768.09  117.74  767.63
  138.38  768.47  144.47  769.79  153.62  770.73  187.13   769.9  324.29  771.28
  357.97  773.57  388.58  772.71  397.76  773.14  419.24  771.88  431.53  772.21
  465.32  774.98   511.4  774.48  539.04  775.12  542.11  775.48  551.33   781.3
  557.47  783.08   575.9  797.28  582.05  799.02  588.19  799.17  597.41  801.55
#Mann= 3 , 0 , 0
       0      .1       0  103.58      .1       0  144.47      .1       0
Bank Sta=103.58,144.47
XS Rating Curve= 0 ,0
Exp/Cntr=0.3,0.1

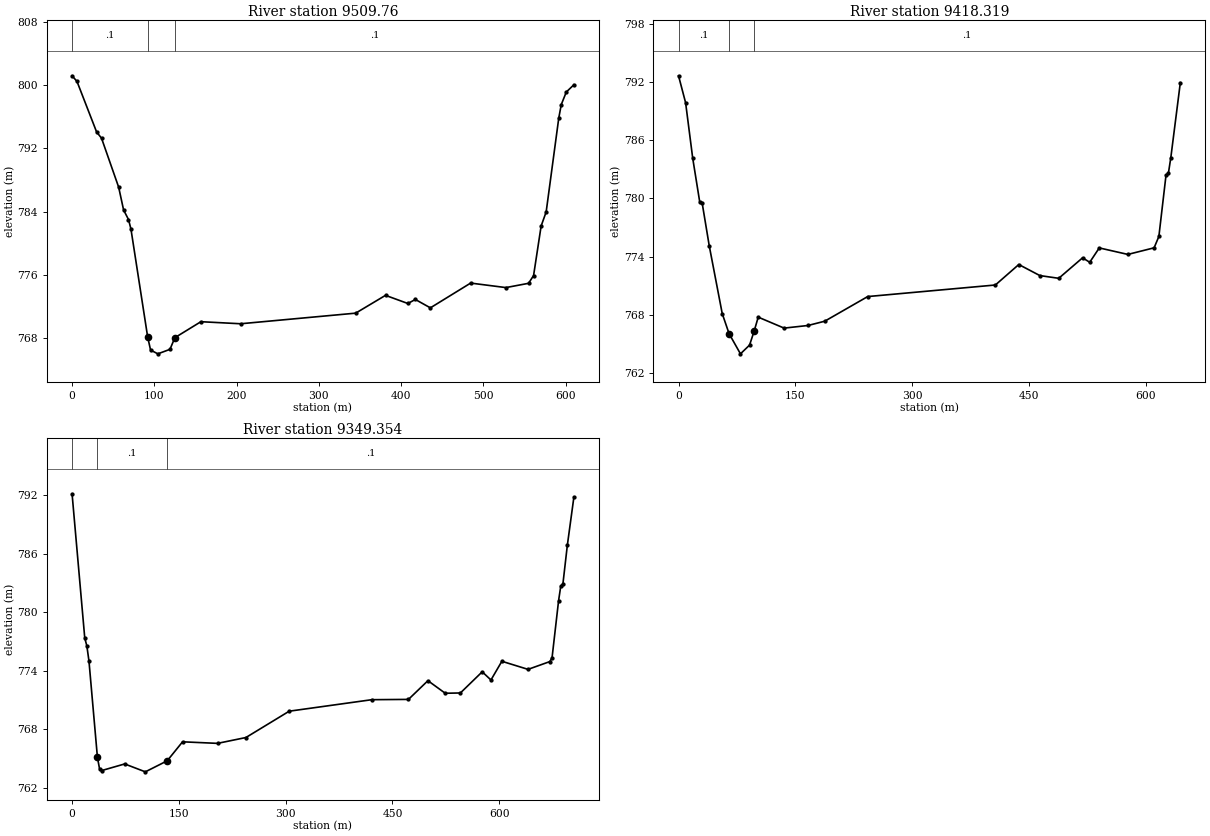
Type RM Length L Ch R = 1 ,9509.76 ,100.44,91.44,118.05
XS GIS Cut Line= 6
     637156.1252    4314753.0372     637138.1702    4314846.7427
     637164.1927    4314923.4472     637291.2929    4314955.0486
     637373.8607    4315030.3998     637463.0425    4315194.3631
#Sta/Elev= 30
       0  801.16    5.96  800.45   29.82  794.06   35.78  793.28   56.65  787.08
   62.61  784.21   68.58     783   71.56   781.8   91.87  768.17   95.41  766.51
  104.26  766.03  119.02   766.6  124.92  768.07   156.6  770.09  204.91  769.83
  344.71  771.17  380.97  773.42  408.16  772.39  417.22   772.9   435.5  771.84
  484.46  774.97   527.3   774.4  554.84  774.94  560.95  775.92  570.13  782.18
  576.25  783.96  591.55  795.81  594.61  797.52  600.73  799.11  609.91  800.02
#Mann= 3 , 0 , 0
       0      .1       0   91.87      .1       0  124.92      .1       0
Bank Sta=91.87,124.92
XS Rating Curve= 0 ,0
Exp/Cntr=0.3,0.1

Type RM Length L Ch R = 1 ,9418.319,83.09,68.97,43.37
XS GIS Cut Line= 6
     637056.6416    4314773.1455     637048.0365    4314892.9491
      637231.314    4314943.5387     637290.2633    4314956.3446
     637369.7376    4315029.8416     637447.1674    4315175.8422
#Sta/Elev= 30
       0  792.64    9.09  789.86   18.18  784.16   27.27  779.61    30.3  779.55
   39.39  775.14   56.11  768.14   64.88  766.08   79.49     764   91.18   764.9
   97.02  766.33  102.29  767.78  135.52  766.65  166.18  766.92  187.65  767.36
  242.85   769.9  406.72  771.09  436.79   773.2  463.85  772.06  488.07  771.78
  518.67  773.89  527.85  773.43   540.1  774.91  576.82  774.24  610.49  774.92
  616.61  776.09  625.79  782.41  628.85  782.61  631.91  784.19  644.15  791.93
#Mann= 3 , 0 , 0
       0      .1       0   64.88      .1       0   97.02      .1       0
Bank Sta=64.88,97.02
XS Rating Curve= 0 ,0
Exp/Cntr=0.3,0.1

Type RM Length L Ch R = 1 ,9349.354,45.89,45.93,22.26
XS GIS Cut Line= 6
     636969.8581    4314763.0914     636983.7036    4314875.6016
     637230.9661    4314944.7198     637289.1745    4314957.4198
      637366.433    4315030.4449     637443.4632    4315176.9005
#Sta/Elev= 30
       0  792.13   17.81  777.34   20.78  776.52   23.74  774.97   35.62  765.09
   38.59  763.92   41.55  763.74   73.92  764.42  102.89  763.61  133.58  764.74
  155.19  766.69  204.28  766.53  244.17  767.13  304.97  769.83  421.05  771.01
  472.45  771.04  499.79  772.96  524.09  771.67   545.4   771.7  576.05  773.87
   588.3  773.03  603.63  774.95   640.4  774.12  671.04  774.92  674.11   775.3
   683.3  781.17  686.36  782.66  689.43  782.92  695.56  786.83  704.75  791.77
#Mann= 3 , 0 , 0
       0      .1       0   35.62      .1       0  133.58      .1       0
Bank Sta=35.62,133.58
XS Rating Curve= 0 ,0
Exp/Cntr=0.3,0.1

River Reach=Red Creek       ,2
Reach XY= 30
     636956.1954    4314870.4384     636709.0038    4314832.4949
     636624.0488    4314883.1089     636208.7135    4314981.6068
     635991.2591    4315065.4538     635847.6315    4315149.7013
     635724.1281    4315280.8512      635593.556      4315329.27
     635515.3714    4315305.0606     635174.0583    4315314.9825
     634893.4671    4315245.9261634842.2981571814315227.05852168
634813.4995924174315144.91014496634556.9120710074315079.97099456
634453.3299067794314989.76470295634398.6141642284314968.13569617
634202.9986355044314941.72644086633963.9709886454314947.97879893
633921.8351357724315024.67620295633827.8421929534315048.31475933
633739.3084073154315109.43825067       633640.18    4315144.3376
     633526.2299    4315143.5321     633315.8858    4315235.6073
      633282.683    4315226.9071     633252.7825    4315154.6447
     633201.9824    4315094.7164     633132.6345    4315128.3257
     632939.6475    4315151.4697     632755.1003    4315225.6854

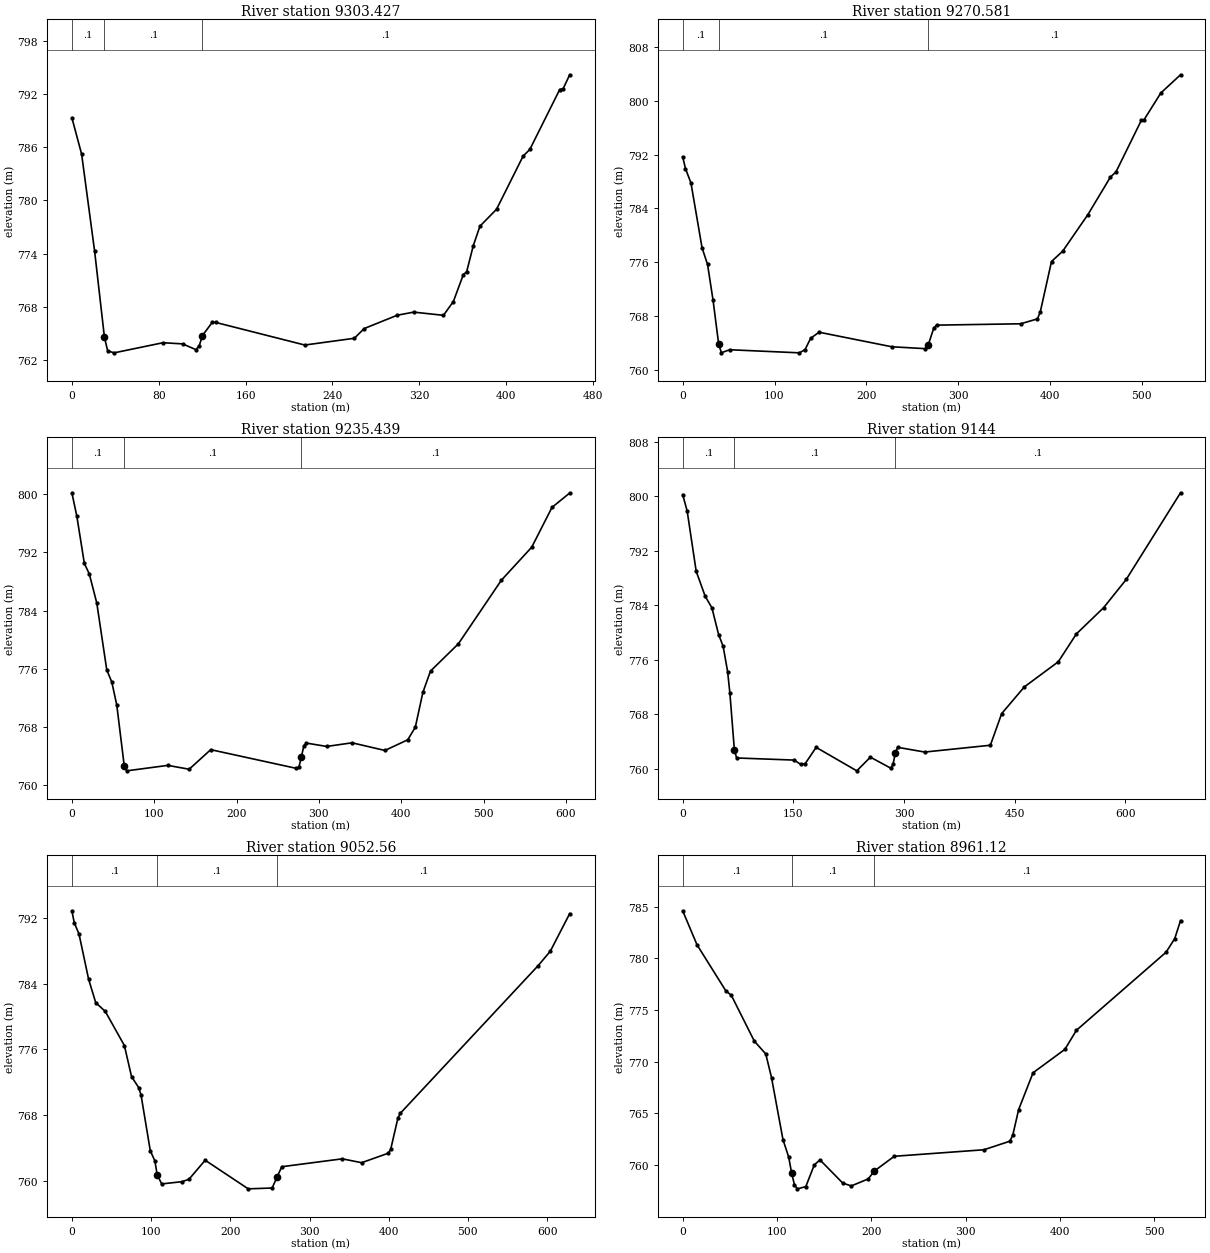
Type RM Length L Ch R = 1 ,9303.427,42.48,32.85,32.33
XS GIS Cut Line= 4
     636929.9791    4314755.9753     636932.3604    4314848.8442
     636964.9042     4315105.226     636964.1104    4315212.3825
#Sta/Elev= 30
       0  789.32    8.99  785.21   20.98  774.24   29.97  764.59   32.96  763.03
   38.96  762.81   83.91  763.95  102.02  763.82  114.18  763.17  117.22  763.58
  120.26  764.76  129.38  766.26  132.43  766.24  214.52  763.69  260.12  764.45
  269.25  765.55  299.65  767.05  314.85   767.4  342.22  767.04  351.34  768.59
  360.52  771.63  363.59  771.95  369.71   774.9  375.83  777.09  391.14     779
  415.63     785  421.76  785.74  449.31   792.5  452.37  792.57   458.5  794.16
#Mann= 3 , 0 , 0
       0      .1       0   29.97      .1       0  120.26      .1       0
Bank Sta=29.97,120.26
XS Rating Curve= 0 ,0
Exp/Cntr=0.3,0.1

Type RM Length L Ch R = 1 ,9270.581,37.37,35.14,34.69
XS GIS Cut Line= 5
      636888.704     4314744.069     636889.4978    4314816.3004
     636900.6103    4314860.7505     636926.0104    4315044.9009
     636918.0728    4315283.0264
#Sta/Elev= 30
       0  791.67    3.01  789.92    9.03  787.77   21.07  778.17   27.09  775.69
   33.11  770.35   39.13  763.93   42.14  762.59   51.17  763.04   127.2  762.58
  133.29  763.06  139.39  764.74  148.53  765.64  227.76  763.48  264.33   763.2
  267.38  763.73  273.47  766.25  276.52  766.69  368.09  766.89  386.42  767.62
  389.48  768.66  401.69  776.13  413.91  777.67   441.4   783.1  465.84  788.65
  471.95  789.43  499.44  797.05   502.5  797.16  520.82  801.14  542.21  803.83
#Mann= 3 , 0 , 0
       0      .1       0   39.13      .1       0  267.38      .1       0
Bank Sta=39.13,267.38
XS Rating Curve= 0 ,0
Exp/Cntr=0.3,0.1

Type RM Length L Ch R = 1 ,9235.439,40.93,91.44,116.87
XS GIS Cut Line= 6
     636853.1568     4314726.054     636851.7265    4314826.0173
     636860.5298    4314840.0014     636871.8349    4314918.0925
     636878.3828     4314938.937     636867.4443    4315326.1302
#Sta/Elev= 30
       0  800.18    6.06  796.94   15.15  790.48   21.21  789.02   30.29  785.02
   42.41  775.83   48.47   774.2   54.53  771.03   63.62  762.67   66.65  761.99
   116.5  762.74  142.48  762.21  168.65   764.9  272.65  762.33  275.73  762.47
   278.8  763.94  281.88  765.47  284.95   765.8  309.54  765.34  340.29  765.84
  380.25  764.79  407.92  766.25  417.14  767.98  426.36  772.78  435.59  775.69
   469.4  779.43  521.66  788.17  558.55  792.71  583.15  798.17  604.67  800.15
#Mann= 3 , 0 , 0
       0      .1       0   63.62      .1       0   278.8      .1       0
Bank Sta=63.62,278.8
XS Rating Curve= 0 ,0
Exp/Cntr=0.3,0.1

Type RM Length L Ch R = 1 ,9144    ,143.38,91.44,43.25
XS GIS Cut Line= 5
     636835.6943     4314722.879     636831.2824    4314805.0429
     636770.8681    4314890.4726     636754.4655    4314962.3309
      636721.394    4315375.3428
#Sta/Elev= 30
       0  800.26    6.09  797.84   18.28  789.01   30.47  785.33   39.62  783.63
   48.76  779.67   54.85  777.98   60.95  774.23      64  771.08   70.09  762.73
   73.14  761.57  151.04  761.26  160.01  760.63  165.99  760.72  180.94  763.13
  236.05  759.68  254.48  761.69  282.11  760.07  285.18  760.63  288.24  762.27
  291.31  763.14  328.14  762.44  417.15  763.44  432.49  768.09  463.19  772.01
  509.22   775.7  533.78   779.8  570.61  783.64   601.3  787.79  674.96  800.53
#Mann= 3 , 0 , 0
       0      .1       0   70.09      .1       0  288.24      .1       0
Bank Sta=70.09,288.24
XS Rating Curve= 0 ,0
Exp/Cntr=0.3,0.1

Type RM Length L Ch R = 1 ,9052.56 ,92.84,91.44,66.62
XS GIS Cut Line= 6
     636654.7189    4314737.1665     636682.6126     4314816.788
     636699.5764    4314828.2487       636733.36    4314885.2746
     636703.3732    4314967.6623     636669.0064    4315335.6552
#Sta/Elev= 30
       0  792.86    3.01  791.41    9.04  790.02   21.09  784.55   30.13  781.68
   42.18  780.62   66.29  776.47   75.33  772.69   84.37  771.35   87.29  770.47
   98.99  763.68  104.84  762.42  107.69  760.75  113.39  759.64  139.03  759.91
  147.81   760.2  168.29  762.52  222.62  759.04  252.85  759.14   258.9  760.45
     265  761.73  341.37  762.69   365.8  762.22   399.4  763.37  402.46  763.83
  411.62  767.65  414.67  768.23  588.78   786.2  604.05  787.95  628.49  792.52
#Mann= 3 , 0 , 0
       0      .1       0  107.69      .1       0   258.9      .1       0
Bank Sta=107.69,258.9
XS Rating Curve= 0 ,0
Exp/Cntr=0.3,0.1

Type RM Length L Ch R = 1 ,8961.12 ,82.11,91.7,52.83
XS GIS Cut Line= 4
     636573.7562    4314767.3291     636622.2935    4314872.0454
      636665.355    4314944.5822     636629.3189    4315270.5676
#Sta/Elev= 30
       0  784.61   15.19  781.32   45.56  776.89   51.63  776.42   75.93     772
   88.08  770.76   94.16  768.47  106.31  762.47  112.38  760.78  115.42  759.26
  118.43  758.12  121.44  757.71  130.48  757.92  139.52  760.03  145.55  760.51
  169.65  758.27  178.68  757.99  196.76  758.67  202.84  759.41   224.3  760.86
  319.31  761.49   346.9  762.32  349.97  762.92   356.1  765.37  371.42  768.94
  405.14   771.2   417.4  773.05  512.42   780.6  521.61  781.92  527.74  783.66
#Mann= 3 , 0 , 0
       0      .1       0  115.42      .1       0  202.84      .1       0
Bank Sta=115.42,202.84
XS Rating Curve= 0 ,0
Exp/Cntr=0.3,0.1

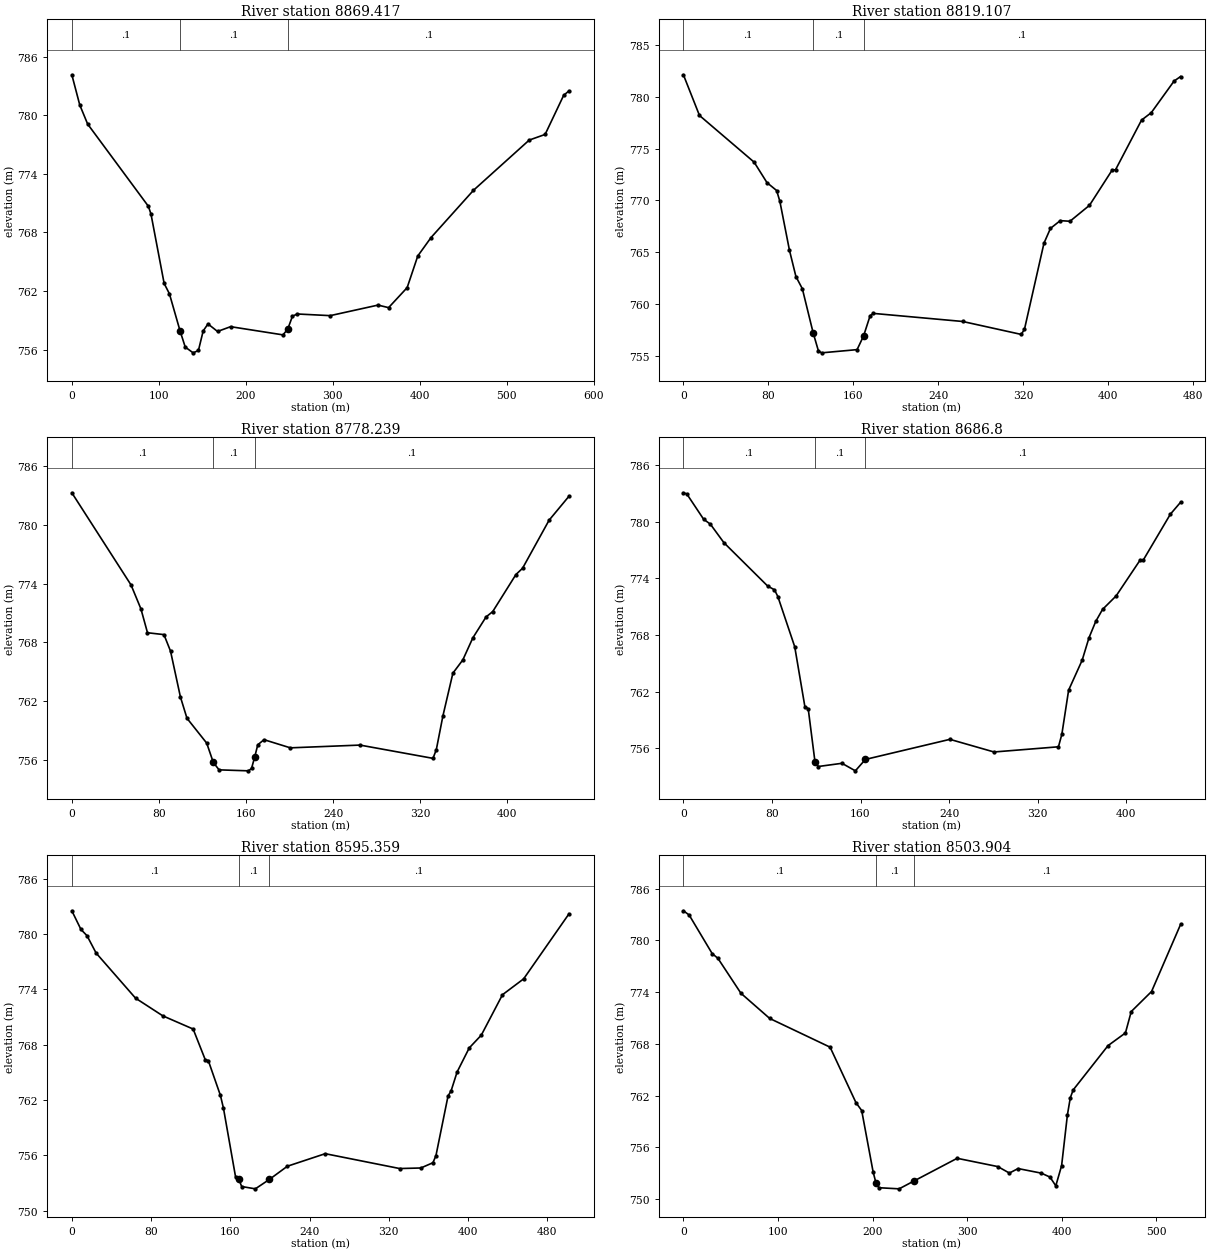
Type RM Length L Ch R = 1 ,8869.417,51.17,50.31,121.68
XS GIS Cut Line= 6
     636511.8436    4314772.0916     636552.8636    4314934.4232
     636628.0054    4314937.8628     636621.6554    4314955.8545
     636622.7137    4314972.7879     636594.3938    4315264.2176
#Sta/Elev= 30
       0  784.14     9.1  781.05   18.19  779.09   87.93  770.68   90.96  769.89
  106.12  762.77  112.18  761.71  124.31  757.94  130.37  756.25  139.47  755.66
  145.53   755.9  151.02  757.91  156.52  758.62   167.5  757.85  182.54  758.34
  242.72   757.5  248.17  758.08  253.62  759.41  259.07  759.64  297.06  759.47
  351.96  760.55  364.16  760.29  385.51  762.34  397.71  765.58  412.96  767.47
  461.76  772.31  525.81  777.45  544.11  778.03  565.46  782.04  571.56  782.49
#Mann= 3 , 0 , 0
       0      .1       0  124.31      .1       0  248.17      .1       0
Bank Sta=124.31,248.17
XS Rating Curve= 0 ,0
Exp/Cntr=0.3,0.1

Type RM Length L Ch R = 1 ,8819.107,43.62,40.87,37.78
XS GIS Cut Line= 5
     636451.7438    4314784.3916     636501.7501    4314933.6169
     636500.9564    4314955.0482     636502.5439    4314993.1483
     636532.7065    4315242.3863
#Sta/Elev= 30
       0  782.13   15.13   778.2   66.58  773.69   78.69  771.71   87.77  770.95
    90.8  769.91   99.88  765.16  105.93  762.64  111.98  761.46  122.08  757.23
  127.12  755.45  130.14  755.27  163.51  755.58  169.64  756.91  175.76  758.85
  178.83  759.08  262.89   758.3     318  757.05  321.06  757.54  339.43  765.86
  345.55  767.29  354.74  768.04  363.92  767.98  382.29  769.52  403.72  772.94
  406.78  772.95  431.28  777.75  440.46  778.47  461.89  781.52  468.02  781.96
#Mann= 3 , 0 , 0
       0      .1       0  122.08      .1       0  169.64      .1       0
Bank Sta=122.08,169.64
XS Rating Curve= 0 ,0
Exp/Cntr=0.3,0.1

Type RM Length L Ch R = 1 ,8778.239,90.64,91.44,90.72
XS GIS Cut Line= 6
     636393.7334    4314792.5175     636449.4554    4314913.2389
     636452.7292    4314916.4298      636463.316    4314938.7176
     636462.6052    4314955.8986     636491.1002    4315231.7267
#Sta/Elev= 30
       0  783.23   54.39  773.85   63.46  771.42    69.5  768.99   84.61   768.8
   90.66  767.12   99.72  762.47  105.76  760.29   123.9  757.76  129.94   755.8
  135.25  755.04  162.21  754.94  165.07  755.18  167.94  756.33   170.8  757.59
  176.54  758.11  200.73  757.28  264.72  757.56  331.76  756.21  334.81  757.09
   340.9  760.54  350.05  764.88  359.19  766.23  368.33  768.46  380.52   770.6
  386.61  771.14  407.94  774.91  414.04  775.55  438.42  780.44   456.7  782.88
#Mann= 3 , 0 , 0
       0      .1       0  129.94      .1       0  167.94      .1       0
Bank Sta=129.94,167.94
XS Rating Curve= 0 ,0
Exp/Cntr=0.3,0.1

Type RM Length L Ch R = 1 ,8686.8  ,98.31,91.44,79.48
XS GIS Cut Line= 4
     636360.0783    4314795.3397     636366.1107    4314941.5153
     636370.7014    4314974.3846     636470.1452    4315225.0239
#Sta/Elev= 30
       0  783.08    3.05  782.96   18.29  780.27   24.38  779.75   36.58  777.79
    76.2  773.18   82.29  772.79   85.34  772.07  100.58  766.75  109.73  760.41
  112.77  760.17  118.87  754.55  121.92  754.05  143.25  754.39  155.35  753.59
   164.4   754.8  240.77  756.93  280.61  755.59  338.82  756.14  341.89  757.46
  348.02  762.15  360.27  765.33   366.4   767.7  372.53  769.44  378.66  770.71
  390.92  772.14  412.37   775.9  415.43  775.94  439.94  780.81  449.14  782.07
#Mann= 3 , 0 , 0
       0      .1       0  118.87      .1       0   164.4      .1       0
Bank Sta=118.87,164.4
XS Rating Curve= 0 ,0
Exp/Cntr=0.3,0.1

Type RM Length L Ch R = 1 ,8595.359,93.7,91.46,96.47
XS GIS Cut Line= 6
     636197.0947    4314799.5731     636275.6332    4314958.8056
     636279.7891    4314970.8956     636297.2772    4315009.4533
     636317.4184    4315047.7785     636385.4784     4315263.124
#Sta/Elev= 30
       0  782.51    9.18  780.49   15.31  779.81   24.49  777.93   64.28  773.04
   91.84  771.12  122.45  769.69  134.69  766.36  137.75  766.27     150  762.49
  153.06   761.1   165.3  753.64  168.36  753.45  171.43  752.62  185.22  752.37
   199.4  753.39  217.55  754.82  255.76  756.18   330.9  754.57  352.26  754.63
  364.47   755.2  367.52  755.97  379.73  762.44  382.78  762.98  388.89  765.04
   401.1  767.64   413.3  769.03  434.67  773.41  456.03  775.13  501.81  782.18
#Mann= 3 , 0 , 0
       0      .1       0  168.36      .1       0   199.4      .1       0
Bank Sta=168.36,199.4
XS Rating Curve= 0 ,0
Exp/Cntr=0.3,0.1

Type RM Length L Ch R = 1 ,8503.904,101.55,91.42,91.47
XS GIS Cut Line= 4
     636110.3112    4314791.1064     636167.6639    4314957.9522
     636188.6781    4314983.8064     636298.6949    4315280.0574
#Sta/Elev= 30
       0  783.42    6.08  782.93   30.42  778.46    36.5  777.91   60.84  773.86
   91.26  770.94  155.13  767.61  182.49  761.18  188.54  760.27  200.66  753.14
  203.69  751.85  206.72  751.32  228.15  751.19   243.5  752.08  289.52  754.73
  332.47  753.77  344.74  753.02  353.95  753.54  378.49  753.01   387.7  752.55
  393.83  751.54  399.97  753.88  406.11  759.77  409.17  761.75  412.24  762.66
  449.06  767.79  467.47  769.26  473.61  771.74  495.08  774.06  525.76  781.83
#Mann= 3 , 0 , 0
       0      .1       0  203.69      .1       0   243.5      .1       0
Bank Sta=203.69,243.5
XS Rating Curve= 0 ,0
Exp/Cntr=0.3,0.1

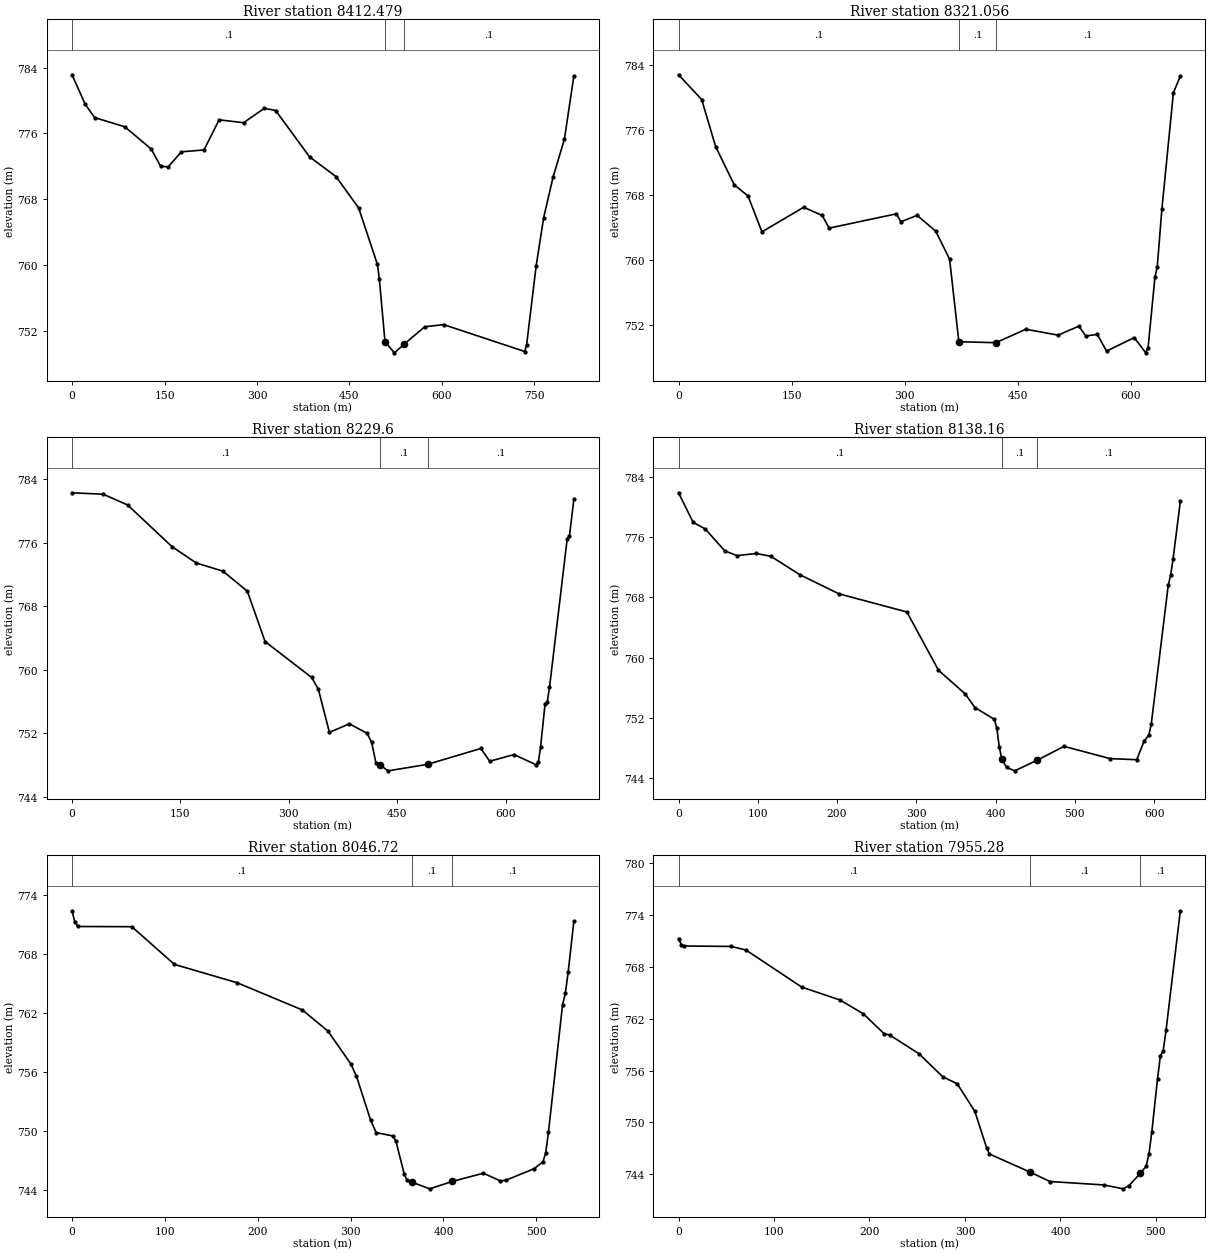
Type RM Length L Ch R = 1 ,8412.479,90.61,91.42,85.47
XS GIS Cut Line= 6
     635907.1107    4314532.8725     636093.1835    4315005.2687
     636101.0304    4315010.9642     636107.1317    4315026.5217
     636109.3232    4315036.7541     636208.7364    4315287.3334
#Sta/Elev= 30
       0  783.12   21.41  779.52    36.7  777.92   85.64   776.8  128.46   774.1
  143.75     772  155.99  771.94   177.4  773.76   214.1  773.99  238.57  777.65
  278.33   777.3  311.97  779.05  330.32  778.78  385.38  773.15   428.2  770.76
   464.9  766.96  495.49  760.08  498.55  758.31  507.72   750.7  522.99  749.35
  539.36  750.44  572.17  752.51   602.8  752.78  734.53  749.51  737.59  750.35
  752.91  759.86  765.16  765.76  780.48   770.7  798.86   775.3  814.18  782.97
#Mann= 3 , 0 , 0
       0      .1       0  507.72      .1       0  539.36      .1       0
Bank Sta=507.72,539.36
XS Rating Curve= 0 ,0
Exp/Cntr=0.3,0.1

Type RM Length L Ch R = 1 ,8321.056,96.45,91.46,86.83
XS GIS Cut Line= 3
     635864.2482    4314692.0197     636023.6525    4315061.8421
     636131.7413    4315301.7553
#Sta/Elev= 30
       0  782.79   30.74  779.74   49.19  773.95   73.78  769.25   92.22  767.85
  110.67  763.43     166  766.46   190.6  765.46  199.82  763.89  288.97  765.65
  295.12  764.68  316.64  765.46  341.23  763.52  359.68  760.07  371.97  749.89
  421.07  749.77  460.85  751.43  503.69   750.7  531.22  751.81   540.4  750.59
   555.7   750.8  567.94  748.73  604.66   750.4  619.96  748.52  623.02  749.14
  632.19  757.84  635.25  759.14  641.37  766.23  656.67  780.58  665.85  782.63
#Mann= 3 , 0 , 0
       0      .1       0  371.97      .1       0  421.07      .1       0
Bank Sta=371.97,421.07
XS Rating Curve= 0 ,0
Exp/Cntr=0.3,0.1

Type RM Length L Ch R = 1 ,8229.6  ,86.31,91.44,98.15
XS GIS Cut Line= 6
     635678.5103    4314733.2948     635924.8751    4315074.3431
     635930.5009    4315083.6314     635947.1722     4315107.336
     635961.0327       4315135.8     636047.5802    4315318.7094
#Sta/Elev= 30
       0  782.31   42.99  782.13   76.77  780.78  138.19  775.53  171.98  773.45
  208.83  772.43  242.61   769.9  267.18  763.55  331.67  759.02  340.88  757.55
  356.23   752.1  383.87  753.18  408.44  751.98  414.58  750.84  420.72  748.22
  426.15  748.01  437.38  747.25  492.22  748.07  565.81  750.07  578.07  748.46
  611.79   749.3  642.45  748.01  645.52   748.4  648.59  750.31  654.72   755.7
  657.78  755.97  660.85  757.76  685.38  776.52  688.44  776.83  694.58   781.5
#Mann= 3 , 0 , 0
       0      .1       0  426.15      .1       0  492.22      .1       0
Bank Sta=426.15,492.22
XS Rating Curve= 0 ,0
Exp/Cntr=0.3,0.1

Type RM Length L Ch R = 1 ,8138.16 ,101.26,91.44,75.94
XS GIS Cut Line= 5
     635659.4603    4314774.5699     635861.2108    4315135.8761
     635864.9822    4315150.8595     635870.9287    4315160.4328
     635932.5108     4315342.896
#Sta/Elev= 30
       0  781.94   18.39  778.01   33.72  777.12   58.24  774.22   73.57  773.57
   98.09  773.86  116.48  773.48  153.27  771.02  202.31  768.49  288.14  766.07
  327.99  758.31  361.71  755.16  373.97  753.35  398.49  751.77  401.56  750.58
  404.62  748.16  407.69  746.53  413.82  745.38  424.12  744.92  452.77  746.35
  486.39  748.18  544.47  746.55  578.09   746.4  587.26  748.84  593.38  749.68
  596.43  751.13  617.83   769.6  620.89  770.97  623.94  773.12  633.11  780.79
#Mann= 3 , 0 , 0
       0      .1       0  407.69      .1       0  452.77      .1       0
Bank Sta=407.69,452.77
XS Rating Curve= 0 ,0
Exp/Cntr=0.3,0.1

Type RM Length L Ch R = 1 ,8046.72 ,96.26,91.44,78.61
XS GIS Cut Line= 6
     635628.2063    4314877.6584     635761.5249    4315160.2578
     635788.8033    4315196.4455     635803.0345    4315209.4645
     635801.7116     4315217.402     635890.4819    4315344.6355
#Sta/Elev= 30
       0  772.41    3.06  771.22    6.13  770.81   64.33  770.79  110.28  766.95
  177.68  765.09  248.14  762.31  275.71  760.15  300.21  756.83  306.34  755.56
  321.53   751.1  327.57  749.83   345.7  749.49  348.72     749  357.79   745.6
   360.5  745.06  365.93  744.79  385.32  744.11  409.65  744.87  443.11   745.7
  461.37  744.91  467.45  744.99  497.87  746.17     507  746.85  510.04  747.71
  513.08  749.86  528.29  762.85  531.33  764.04  534.37  766.19  540.46  771.35
#Mann= 3 , 0 , 0
       0      .1       0  365.93      .1       0  409.65      .1       0
Bank Sta=365.93,409.65
XS Rating Curve= 0 ,0
Exp/Cntr=0.3,0.1

Type RM Length L Ch R = 1 ,7955.28 ,84.2,91.44,106.89
XS GIS Cut Line= 6
     635618.6813    4314887.1834     635698.3727    4315218.7759
     635726.6883    4315264.5509      635756.177    4315290.7024
     635775.2532    4315311.9466     635806.0066    4315366.6094
#Sta/Elev= 30
       0  771.27    3.07  770.55    6.14  770.43    55.3  770.38   70.66  769.96
  129.04  765.67  168.98  764.18  193.56  762.58  215.07  760.29  221.21  760.12
  251.94  757.94  276.51   755.3  291.88  754.47  310.31  751.28   322.6  747.08
  325.67  746.33  367.95  744.25  388.88  743.15  445.69  742.75  465.81   742.3
  471.79  742.68  483.73   744.1  489.71  744.92  492.69  746.33  495.68  748.89
  501.65  755.03  504.64  757.69  507.63  758.31  510.61  760.69  525.55  774.51
#Mann= 3 , 0 , 0
       0      .1       0  367.95      .1       0  483.73      .1       0
Bank Sta=367.95,483.73
XS Rating Curve= 0 ,0
Exp/Cntr=0.3,0.1

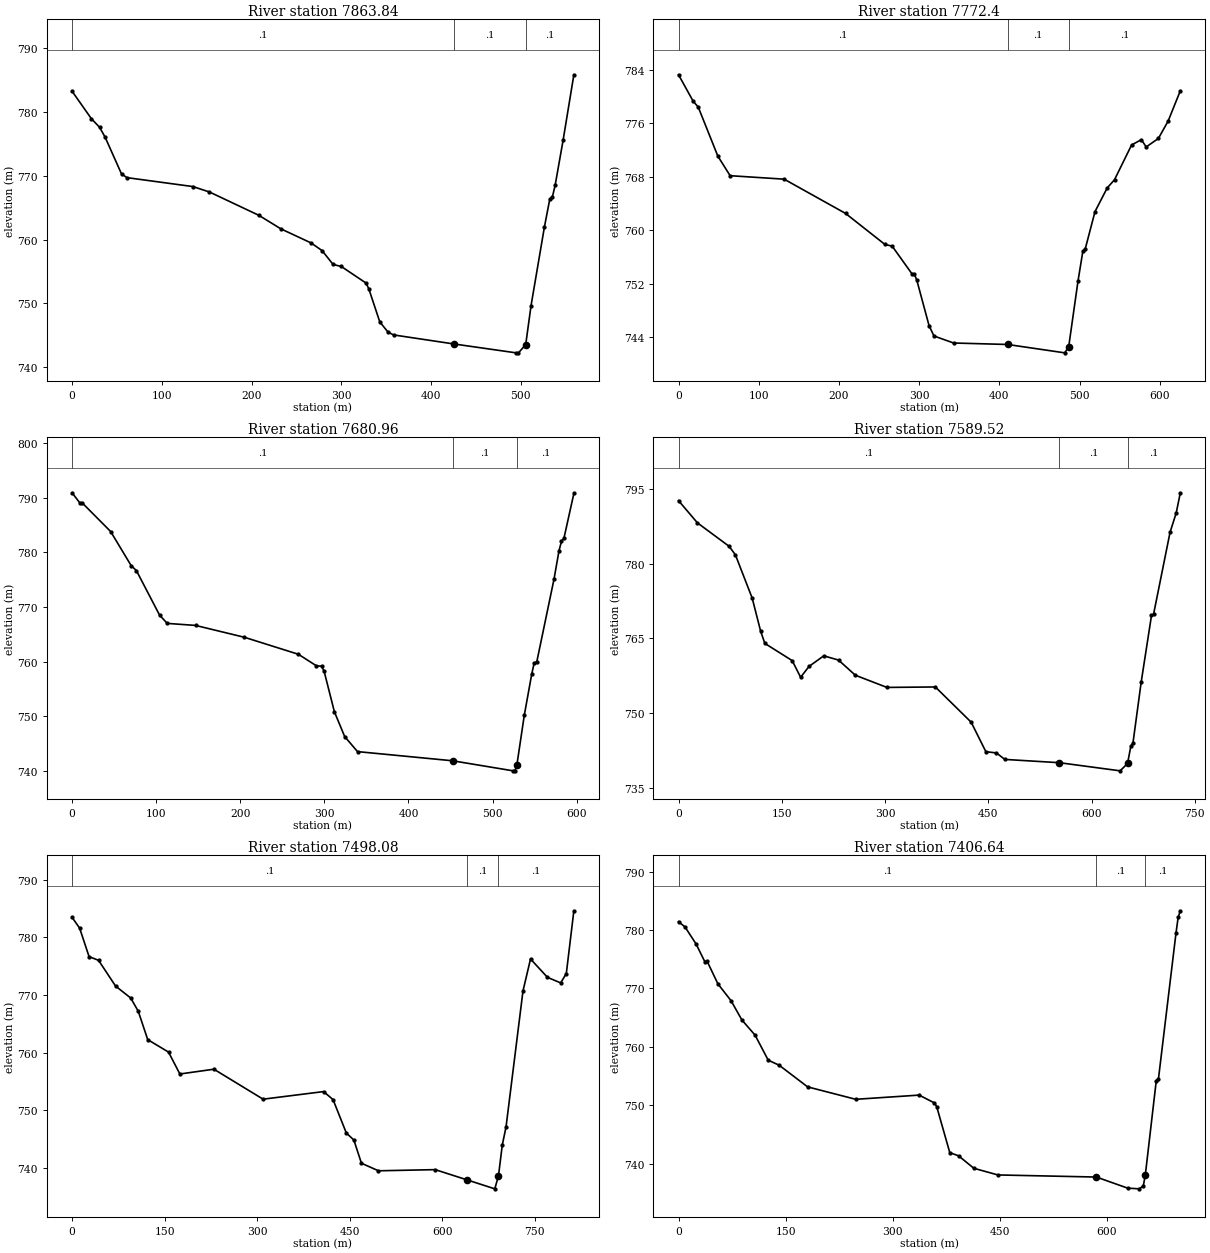
Type RM Length L Ch R = 1 ,7863.84 ,85.72,91.44,104.43
XS GIS Cut Line= 5
     635601.2187    4314844.3208     635640.3127     4315280.372
     635665.1126    4315331.6268      635668.959    4315341.6461
     635672.6564    4315395.1844
#Sta/Elev= 30
       0  783.28   21.43  778.99   30.62  777.63   36.74   776.1   55.11  770.31
   61.23  769.73  134.71  768.33  153.08  767.48  208.18  763.82  232.68   761.7
  266.35  759.49   278.6  758.29  290.85  756.12  300.03   755.8  327.58   753.2
  330.65   752.3  342.89  747.11  352.08  745.51   358.2  745.07  425.55  743.65
  494.74  742.26  497.42  742.26  505.47  743.54  511.43  749.66  526.34     762
   532.3  766.35  535.29  766.75  538.27  768.52  547.21  775.64  559.14  785.86
#Mann= 3 , 0 , 0
       0      .1       0  425.55      .1       0  505.47      .1       0
Bank Sta=425.55,505.47
XS Rating Curve= 0 ,0
Exp/Cntr=0.3,0.1

Type RM Length L Ch R = 1 ,7772.4  ,99.27,91.44,91.04
XS GIS Cut Line= 6
     635593.2812    4314850.6708     635572.1498    4315306.3959
     635567.5383    4315316.4979     635565.0662    4315330.3779
      635565.006    4315337.8284     635563.1187    4315474.5596
#Sta/Elev= 30
       0  783.25   18.37  779.27   24.49  778.44   48.99  771.09    64.3  768.16
  131.66  767.64  208.21  762.52  257.19  757.89  266.38  757.62  290.88  753.51
  293.94  753.45     297  752.57  312.31  745.75  318.43  744.19  342.93  743.14
  410.29  742.92  481.42  741.67  486.39  742.54  497.99  752.36  504.06  756.85
   507.1  757.23  519.26   762.8  534.45  766.33  543.57  767.56  564.84  772.75
  576.99  773.55  583.07  772.46  598.27  773.73  610.42  776.33  625.61  780.86
#Mann= 3 , 0 , 0
       0      .1       0  410.29      .1       0  486.39      .1       0
Bank Sta=410.29,486.39
XS Rating Curve= 0 ,0
Exp/Cntr=0.3,0.1

Type RM Length L Ch R = 1 ,7680.96 ,103.64,91.44,87.96
XS GIS Cut Line= 5
     635593.2812    4314803.0457     635483.0817    4315286.0142
     635480.2436    4315315.0263     635477.8565    4315318.7299
     635459.9309    4315384.0719
#Sta/Elev= 30
       0  790.91    9.17  789.07   12.23  789.03   45.87  783.82   70.33  777.56
   76.45  776.68  103.97  768.54  113.14     767  146.78  766.63  204.88  764.46
   269.1  761.35   290.5  759.24  296.62  759.17  299.67  758.27  311.91  750.83
  324.14  746.29  339.43  743.53  452.57  741.85  524.53  740.01  526.73  740.07
  528.94  741.08  537.78  750.22  546.61  757.73  549.56   759.8  552.51   759.9
  573.13  775.13  579.02   780.3  581.96  782.02  584.91  782.59  596.69  790.78
#Mann= 3 , 0 , 0
       0      .1       0  452.57      .1       0  528.94      .1       0
Bank Sta=452.57,528.94
XS Rating Curve= 0 ,0
Exp/Cntr=0.3,0.1

Type RM Length L Ch R = 1 ,7589.52 ,95.19,91.44,86.7
XS GIS Cut Line= 6
      635478.981    4314672.8705     635379.6628    4315214.1972
     635386.7816    4315275.7149     635389.4995    4315310.6285
     635388.6587    4315320.3482     635393.2558    4315392.0094
#Sta/Elev= 30
       0   792.6   27.52  788.14   73.38  783.46   82.55  781.76  107.01  773.06
  119.25  766.44  125.36  763.99  165.11  760.54  177.34   757.2  189.57  759.38
  210.97   761.5  232.38  760.65  256.84  757.61   302.7  755.17  373.02  755.26
     425  748.21  446.41  742.29  461.69  742.04  473.92  740.74  553.31  740.08
  641.47  738.45  652.19  739.93  657.07  743.45  660.06  744.01  672.03  756.24
  686.99  769.59  689.98  769.82  713.91  786.24  722.89  790.14  728.87  794.18
#Mann= 3 , 0 , 0
       0      .1       0  553.31      .1       0  652.19      .1       0
Bank Sta=553.31,652.19
XS Rating Curve= 0 ,0
Exp/Cntr=0.3,0.1

Type RM Length L Ch R = 1 ,7498.08 ,88.26,91.44,98.24
XS GIS Cut Line= 4
     635421.8309    4314650.6454      635292.944    4315275.2199
     635305.8349    4315324.0406     635263.7156    4315441.9628
#Sta/Elev= 30
       0  783.48   12.26  781.61   27.59  776.66   42.92  776.03   70.52  771.56
   95.05  769.49  107.31  767.19  122.64  762.27  156.37  760.11  174.76  756.31
  229.95  757.14  309.67  751.94  407.78  753.26  423.11  751.86  444.57  746.08
  456.84  744.85   469.1  740.83   496.7  739.52  588.68  739.72   640.7  737.93
  685.26  736.39  691.28  738.66  697.39  743.97   703.5  747.13  730.99  770.72
   743.2  776.26  770.69  773.07  792.07  772.11  801.23  773.74  813.45  784.62
#Mann= 3 , 0 , 0
       0      .1       0   640.7      .1       0  691.28      .1       0
Bank Sta=640.7,691.28
XS Rating Curve= 0 ,0
Exp/Cntr=0.3,0.1

Type RM Length L Ch R = 1 ,7406.64 ,95.44,91.44,93.71
XS GIS Cut Line= 6
     635349.0086    4314693.5609      635212.975    4315300.5045
     635212.1797    4315309.9111     635211.0215    4315314.9487
     635209.9322    4315332.1419     635199.1328    4315379.9356
#Sta/Elev= 30
       0  781.44    9.19  780.51   24.51  777.62   36.77  774.59   39.83   774.7
   55.15  770.78   73.54  767.89   88.86  764.57  107.24  761.99  125.63   757.7
  140.95  756.84  180.78  753.13  248.19     751  337.05  751.72  358.49  750.37
  361.56  749.76  379.94  741.86   392.2  741.32  413.65  739.18  447.35  738.04
  585.23  737.68  629.08  735.78  645.35  735.66  651.01  736.17  653.84  738.07
  669.15   754.2  672.22  754.52  696.72  779.42  699.78  782.16  702.84   783.3
#Mann= 3 , 0 , 0
       0      .1       0  585.23      .1       0  653.84      .1       0
Bank Sta=585.23,653.84
XS Rating Curve= 0 ,0
Exp/Cntr=0.3,0.1