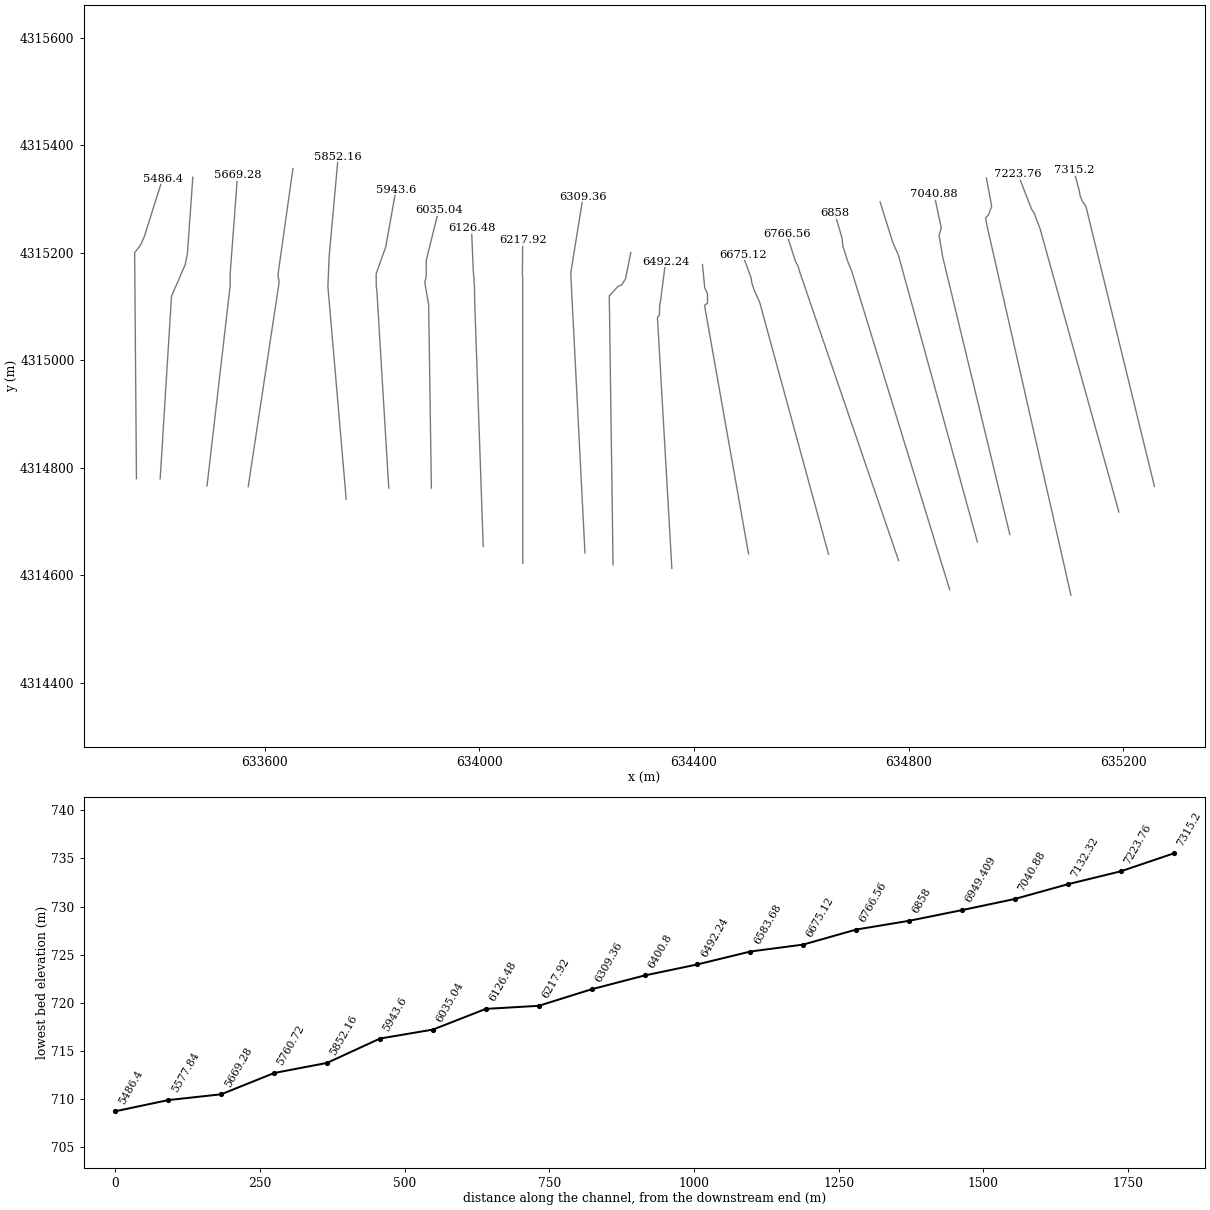
HEC-RAS study RedCreek.prj: RedCreek

--- RedCreek.g01 (geometry) --- (continued)

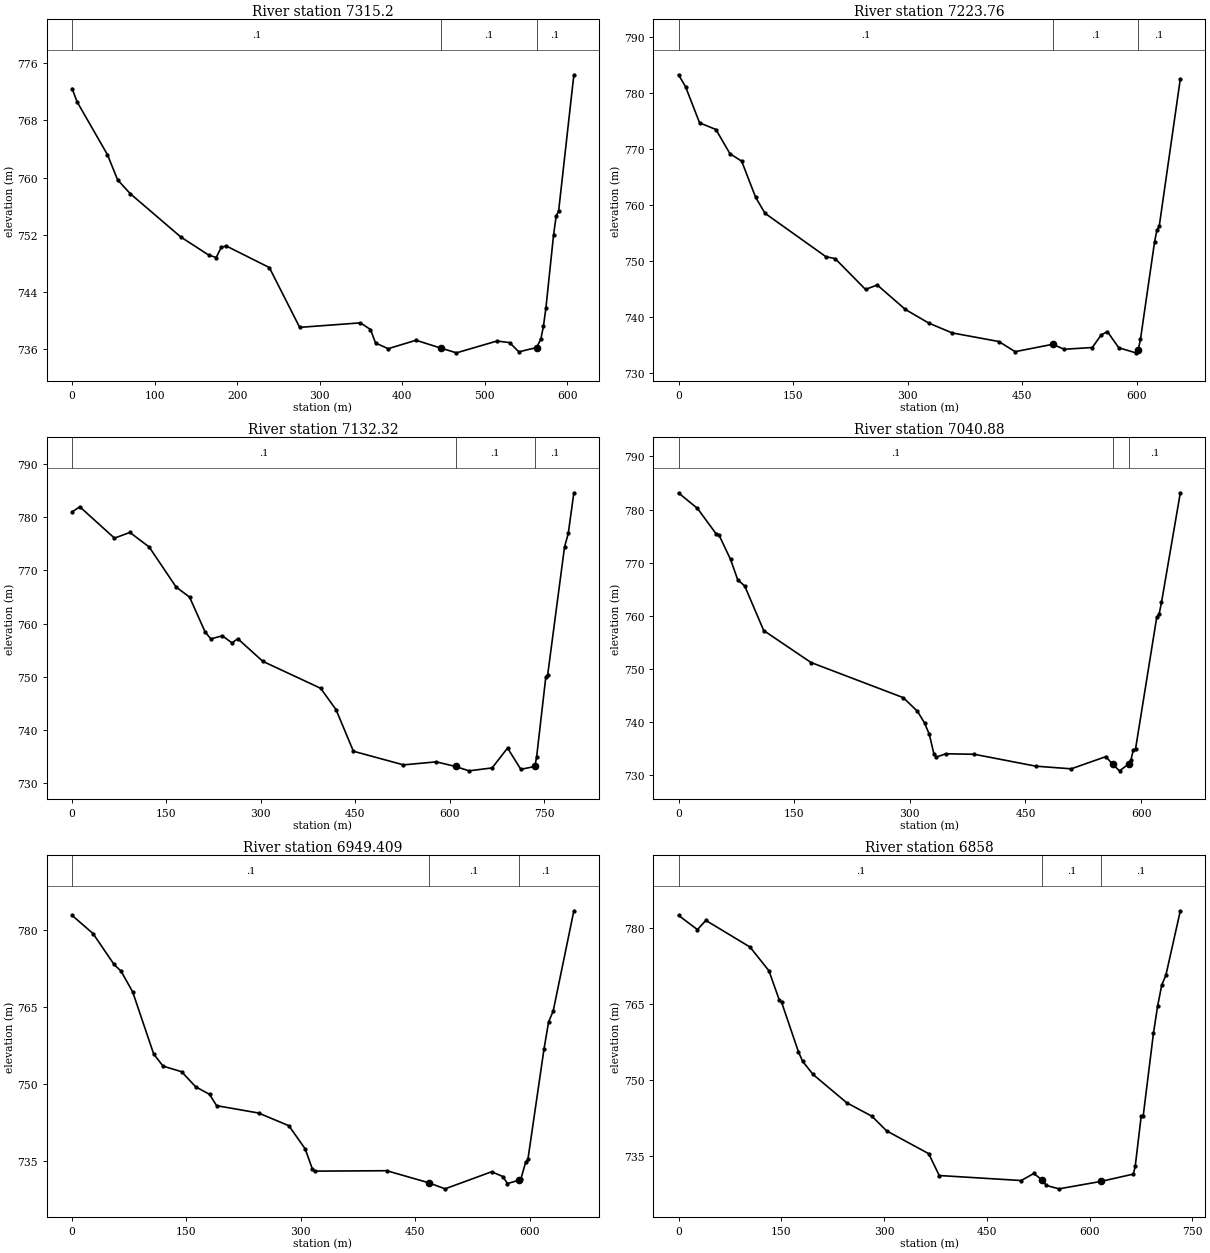
Type RM Length L Ch R = 1 ,7315.2  ,102.42,91.44,96.88
XS GIS Cut Line= 6
     635258.0027    4314765.6049     635130.3543    4315286.2324
     635123.1914    4315296.7496      635119.246    4315307.3613
     635118.0776    4315315.0191     635107.6007    4315353.5526
#Sta/Elev= 30
       0  772.46    6.13  770.59   42.88  763.21   55.14   759.7   70.45  757.77
  131.71  751.71  165.41  749.19   174.6  748.84  180.72  750.29  186.85  750.45
  238.92  747.44  275.68  739.08   349.2  739.71  361.45  738.78  367.58  736.89
  382.89   736.1  416.59  737.28  447.22  736.16   465.6  735.52  514.61  737.17
  529.92  736.95  541.14  735.66  562.68  736.26  567.84  737.48  570.91  739.22
  573.98  741.85   583.2  752.02  586.27  754.58  589.34  755.37  607.77  774.38
#Mann= 3 , 0 , 0
       0      .1       0  447.22      .1       0  562.68      .1       0
Bank Sta=447.22,562.68
XS Rating Curve= 0 ,0
Exp/Cntr=0.3,0.1

Type RM Length L Ch R = 1 ,7223.76 ,93.78,91.44,75.23
XS GIS Cut Line= 6
     635191.8568    4314717.8475     635044.7476    4315245.3459
     635037.7837    4315262.9802     635034.0416    4315274.1413
     635029.3624      4315280.35     635003.7377    4315346.1019
#Sta/Elev= 30
       0  783.28    9.18  781.15   27.53  774.71   48.95  773.51   67.31  769.19
    82.6  767.87  100.96  761.39   113.2  758.56  192.74  750.83  204.98  750.47
  244.75  744.97  260.05  745.77  296.76  741.41  327.35  738.98  357.95  737.22
  419.13  735.68  440.55  733.87   489.5  735.18   504.8   734.3  541.51  734.61
  553.04  736.83  561.17  737.46  576.14  734.57  598.41  733.66  601.48  734.11
  604.55  736.08  622.96  753.42  626.03  755.54   629.1  756.26  656.71  782.56
#Mann= 3 , 0 , 0
       0      .1       0   489.5      .1       0  601.48      .1       0
Bank Sta=489.5,601.48
XS Rating Curve= 0 ,0
Exp/Cntr=0.3,0.1

Type RM Length L Ch R = 1 ,7132.32 ,92.89,91.44,97.29
XS GIS Cut Line= 6
     635102.4274    4314563.3967     634947.4731    4315243.9721
     634943.2919    4315264.5144     634948.6326    4315270.2394
     634954.7709    4315286.1144         634945.    4315338.6274
#Sta/Elev= 30
       0  780.95   12.25  781.93   67.35  776.04   91.84  777.11  122.45  774.38
  165.31  766.85  186.74  764.95  211.23  758.45  220.42  757.11  238.79  757.69
  254.09  756.35  263.28  757.14  303.08  752.89  394.92  747.83  419.41  743.81
  446.96     736  526.55  733.44   578.6  734.01  609.21  733.14  630.64  732.32
  667.38  732.87  691.87   736.6  712.97   732.6   735.3  733.15  738.13     735
  752.71     750  755.68  750.41  782.38  774.36  788.32  776.92  797.22  784.56
#Mann= 3 , 0 , 0
       0      .1       0  609.21      .1       0   735.3      .1       0
Bank Sta=609.21,735.3
XS Rating Curve= 0 ,0
Exp/Cntr=0.3,0.1

Type RM Length L Ch R = 1 ,7040.88 ,90.96,91.47,96.08
XS GIS Cut Line= 6
     634988.6564    4314675.8448     634863.5635    4315191.7617
     634857.3039     4315229.333     634856.6196    4315232.3123
     634860.7678    4315246.4163     634847.3951    4315309.1528
#Sta/Elev= 30
       0  783.12   24.55  780.21    49.1  775.35   52.17  775.29   67.51  770.59
   76.71  766.78   85.92  765.57  110.47  757.21  171.84  751.19  291.52  744.57
  309.93     742  319.13  739.79  325.27  737.66  331.41  733.88  334.48  733.39
  346.75     734  383.57  733.91  463.36  731.67  509.39  731.17   554.3  733.47
  563.09  732.01  572.01  730.79  583.77  732.07  586.71  732.79  589.77  734.66
  592.82  734.95  620.31  759.76  623.37  760.31  626.42  762.49  650.86  783.15
#Mann= 3 , 0 , 0
       0      .1       0  563.09      .1       0  583.77      .1       0
Bank Sta=563.09,583.77
XS Rating Curve= 0 ,0
Exp/Cntr=0.3,0.1

Type RM Length L Ch R = 1 ,6949.409,94.32,91.41,90.28
XS GIS Cut Line= 4
     634928.0931    4314662.2452     634780.9009    4315195.6865
     634770.2163    4315219.7992     634746.8532    4315294.6006
#Sta/Elev= 30
       0  782.76   27.52  779.22   55.03  773.23    64.2  771.93   79.49  767.89
  107.01  755.84  119.24  753.48  143.69  752.38  162.04  749.46  180.38  747.98
  189.55  745.79  244.59  744.36  284.33  741.89  305.73   737.4   314.9  733.58
  317.96  733.07  412.74  733.15  467.77  730.81  489.17  729.63  550.32  732.95
   565.1  732.01  570.96  730.66  585.78  731.29  588.79  731.63  594.82  734.77
  597.84  735.34  618.93  756.75  624.96  762.04  630.99  764.16  658.12  783.65
#Mann= 3 , 0 , 0
       0      .1       0  467.77      .1       0  585.78      .1       0
Bank Sta=467.77,585.78
XS Rating Curve= 0 ,0
Exp/Cntr=0.3,0.1

Type RM Length L Ch R = 1 ,6858    ,96.66,91.44,94
XS GIS Cut Line= 6
     634876.4993    4314573.6096     634693.9851    4315165.8491
     634686.4155    4315184.1241     634677.4751    4315212.4159
     634675.9934    4315227.2326     634662.1863    4315273.4339
#Sta/Elev= 30
       0  782.49   27.61  779.68   39.88   781.5  104.31  776.24  131.92  771.56
  147.26  765.71  150.33  765.37  174.87  755.61  181.01  753.71  196.35  751.09
  245.44  745.51  282.25  742.85  303.73  739.96  365.09  735.46  380.43  731.15
  500.08  730.16  518.48  731.55  530.76  730.24  536.89  729.18   555.3  728.52
  616.66  729.99  663.82  731.43  666.51  732.99  675.16   742.8  678.14   742.9
  693.14  759.26  699.16  764.58  705.19  768.74  711.22  770.67  732.32   783.4
#Mann= 3 , 0 , 0
       0      .1       0  530.76      .1       0  616.66      .1       0
Bank Sta=530.76,616.66
XS Rating Curve= 0 ,0
Exp/Cntr=0.3,0.1

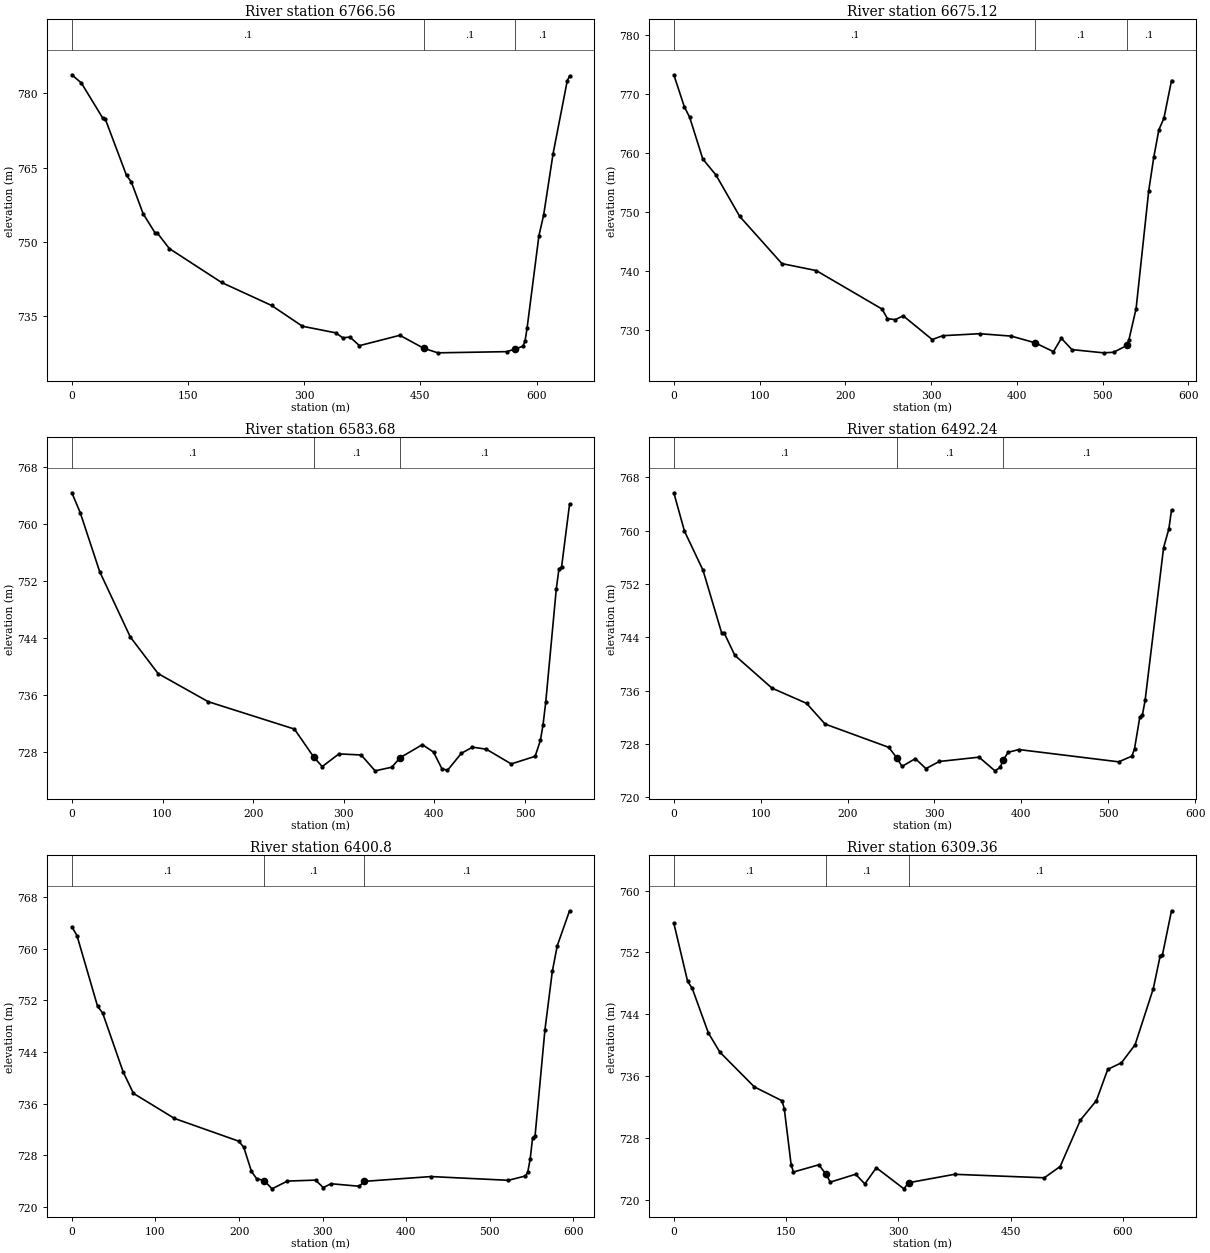
Type RM Length L Ch R = 1 ,6766.56 ,92.96,91.44,88.47
XS GIS Cut Line= 5
     634781.2491    4314627.8493     634596.8892    4315164.8534
      634594.313    4315174.2829     634589.4084    4315183.4087
     634572.5586    4315235.5323
#Sta/Elev= 30
       0  783.74   12.28  782.08    39.9  774.99   42.97  774.89   70.59  763.41
   76.73  762.13   92.07  755.68  107.42  751.83  110.48  751.77  125.83  748.66
  193.35  741.81   257.8  737.18   297.7  732.98  340.66  731.65  349.87  730.64
  359.08   730.8  371.35  729.06  423.53  731.15  454.22  728.54  472.63  727.61
  561.63  727.85  572.66  728.39  582.73  728.96  585.32  730.09  587.91   732.7
  603.12  751.25  609.21  755.41  621.38  767.79  639.64  782.47  642.68   783.5
#Mann= 3 , 0 , 0
       0      .1       0  454.22      .1       0  572.66      .1       0
Bank Sta=454.22,572.66
XS Rating Curve= 0 ,0
Exp/Cntr=0.3,0.1

Type RM Length L Ch R = 1 ,6675.12 ,109.74,91.44,88.49
XS GIS Cut Line= 6
     634650.7431    4314639.4249     634522.4598    4315107.8612
     634512.2532     4315130.206     634507.5337    4315145.0486
     634506.8494    4315152.3113     634490.6248    4315196.6237
#Sta/Elev= 30
       0  773.26    12.3  767.81   18.44  766.06   33.81  758.95   49.18  756.23
   76.85  749.21  126.03   741.2  165.99  740.02  242.84  733.48  248.99  731.87
  258.21  731.68  267.43  732.34  301.25  728.31  313.54  728.96  356.58   729.3
  393.47  728.89  421.13  727.76  442.65  726.25  451.87  728.52  464.17   726.6
  501.04  726.05  512.84  726.15  528.26   727.3  530.69  728.29  539.02  733.56
  553.76   753.6  559.66  759.29  565.56  763.92  571.46  765.88  580.31  772.28
#Mann= 3 , 0 , 0
       0      .1       0  421.13      .1       0  528.26      .1       0
Bank Sta=421.13,528.26
XS Rating Curve= 0 ,0
Exp/Cntr=0.3,0.1

Type RM Length L Ch R = 1 ,6583.68 ,118.89,91.44,84.4
XS GIS Cut Line= 6
     634501.6765     4314640.298     634419.6745    4315102.0982
     634425.1734    4315106.4638     634425.1734    4315123.8106
     634420.1541    4315134.5263     634415.8617    4315178.1655
#Sta/Elev= 30
       0  764.41    9.21  761.62   30.69  753.33   64.45  744.15   95.14     739
  150.39  735.05  245.53   731.2  267.01  727.24  276.22  725.93  294.63  727.71
  319.19  727.56  334.53  725.33  352.95  725.84  362.15  727.18  386.71  729.01
  398.98  727.97  408.19  725.64  414.33  725.39  429.67  727.79  441.95  728.66
  457.29  728.37  484.73   726.3  511.08  727.37  516.93  729.61  519.85  731.83
  522.77  734.94  534.47  750.93  537.39  753.71  540.31  754.02  549.08  762.79
#Mann= 3 , 0 , 0
       0      .1       0  267.01      .1       0  362.15      .1       0
Bank Sta=267.01,362.15
XS Rating Curve= 0 ,0
Exp/Cntr=0.3,0.1

Type RM Length L Ch R = 1 ,6492.24 ,109.62,91.44,74
XS GIS Cut Line= 6
     634358.8013    4314613.3104     634331.9509     4315079.904
     634335.4901    4315083.7301      634336.192    4315102.4483
     634337.8246    4315110.8603     634347.0417    4315183.2474
#Sta/Elev= 30
       0  765.66   12.22  759.92    33.6  754.05   54.98  744.69   58.04  744.63
   70.26  741.29  113.02  736.38  152.73  734.11  174.12     731  247.43  727.51
  256.59  725.94   262.7  724.65  277.98  725.82  290.19  724.32  305.47  725.39
  351.29  726.04  369.62  723.99  375.73  724.51  378.78  725.56  384.89  726.77
  397.11  727.18  512.04  725.34  527.24  726.19  530.28   727.3  536.36  732.05
   539.4   732.4  542.45  734.54  563.73  757.43  569.81  760.26  572.85  763.07
#Mann= 3 , 0 , 0
       0      .1       0  256.59      .1       0  378.78      .1       0
Bank Sta=256.59,378.78
XS Rating Curve= 0 ,0
Exp/Cntr=0.3,0.1

Type RM Length L Ch R = 1 ,6400.8  ,85.77,91.44,103.5
XS GIS Cut Line= 6
     634249.2635    4314619.6604     634242.2252    4315119.7997
     634258.8607    4315137.9649     634265.0697    4315139.9398
     634272.4516    4315151.3698     634282.2655    4315200.4804
#Sta/Elev= 30
       0  763.39    6.14  762.01   30.69  751.11   36.82  750.04   61.37  740.92
   73.65  737.61  122.75  733.73  199.46  730.22   205.6  729.28  214.81  725.54
  220.94  724.42  230.15  724.11  239.35  722.84  257.77  724.04  291.52  724.19
  300.73  723.03  309.93  723.63  343.69  723.24  349.83     724  429.61  724.74
  522.08  724.16   542.5  724.83  545.22  725.38  548.17  727.42  551.11  730.75
  554.06  731.05  565.84  747.43  574.68  756.48  580.57  760.44   595.3  765.86
#Mann= 3 , 0 , 0
       0      .1       0  230.15      .1       0  349.83      .1       0
Bank Sta=230.15,349.83
XS Rating Curve= 0 ,0
Exp/Cntr=0.3,0.1

Type RM Length L Ch R = 1 ,6309.36 ,93.97,91.44,91.2
XS GIS Cut Line= 4
     634196.8759    4314641.8855     634170.9234    4315151.4373
     634170.5377     4315163.011     634193.3041    4315304.1389
#Sta/Elev= 30
       0  755.79   18.44  748.25   24.59  747.35    46.1  741.59   61.47   739.1
  107.57   734.6  144.46  732.81  147.53  731.78  156.75  724.48  159.83  723.59
  193.63  724.52  202.86  723.36     209  722.28  242.81   723.3  255.11  722.05
  270.47  724.14  307.36  721.41   313.5   722.2  374.98  723.29  494.84  722.84
     516   724.3  543.08  730.31  564.37  732.82  579.58  736.87  597.83  737.72
  616.08  740.05  640.41  747.32  649.54  751.52  652.58  751.66  664.74  757.39
#Mann= 3 , 0 , 0
       0      .1       0  202.86      .1       0   313.5      .1       0
Bank Sta=202.86,313.5
XS Rating Curve= 0 ,0
Exp/Cntr=0.3,0.1

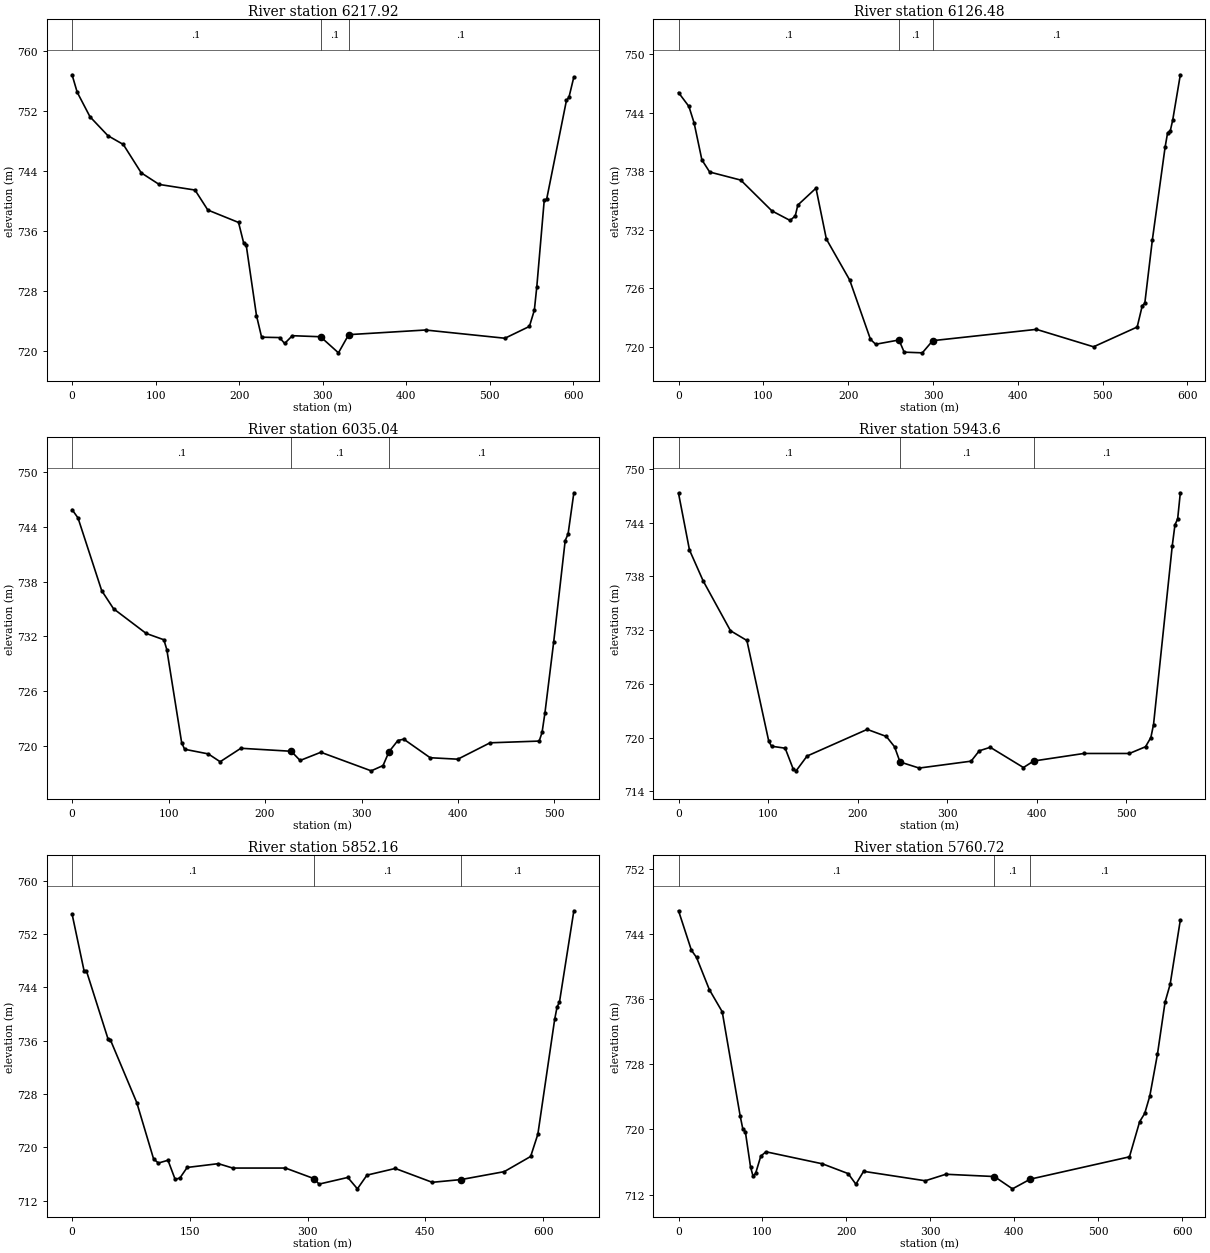
Type RM Length L Ch R = 1 ,6217.92 ,90.03,91.44,96.38
XS GIS Cut Line= 4
     634080.9882    4314622.8355     634080.8962    4315150.0914
     634080.2865    4315161.3056     634080.9566    4315223.3696
#Sta/Elev= 30
       0  756.84    6.13  754.51   21.46  751.23   42.92   748.7   61.31  747.53
   82.77  743.74  104.22  742.19  147.14  741.44  162.47  738.77  199.25  737.11
  205.38  734.36  208.45  734.06  220.71  724.67  226.84  721.78   248.3  721.73
  254.43  720.94  263.63  721.98  297.35  721.84  318.81  719.69  331.07  722.12
  423.03  722.74  518.06  721.64  547.35  723.22  553.26  725.39  556.22  728.54
  565.09  740.08  568.04  740.24  591.69  753.42  594.64  753.82  600.55  756.55
#Mann= 3 , 0 , 0
       0      .1       0  297.35      .1       0  331.07      .1       0
Bank Sta=297.35,331.07
XS Rating Curve= 0 ,0
Exp/Cntr=0.3,0.1

Type RM Length L Ch R = 1 ,6126.48 ,90.9,91.44,88.12
XS GIS Cut Line= 6
     634007.2796    4314653.9902     633991.5298    4315106.2455
     633990.9405    4315136.0242     633989.8027    4315154.8954
      633988.833    4315164.4166     633985.5065    4315245.1435
#Sta/Elev= 30
       0  746.08   12.23  744.66   18.35  742.97   27.52  739.18   36.69  737.93
   73.38   737.1  110.07  733.94  131.48  732.96  137.59  733.42  140.65  734.54
  162.05  736.27  174.28  731.05   201.8  726.84  226.26  720.76  232.38  720.25
   259.9  720.69  266.01  719.44  287.42  719.37  299.65  720.62  421.95  721.78
   489.3  719.99  540.72  722.02   546.7   724.2   549.7  724.45  558.67     731
  573.64  740.48  576.63  741.97  579.62  742.11  582.61  743.26  591.59  747.91
#Mann= 3 , 0 , 0
       0      .1       0   259.9      .1       0  299.65      .1       0
Bank Sta=259.9,299.65
XS Rating Curve= 0 ,0
Exp/Cntr=0.3,0.1

Type RM Length L Ch R = 1 ,6035.04 ,92.82,91.44,84.13
XS GIS Cut Line= 6
     633910.7064    4314762.4696     633905.6424     4315103.147
     633898.3428    4315145.1197     633901.1026    4315155.1075
     633901.1026    4315185.6669      633924.166     4315278.685
#Sta/Elev= 30
       0  745.92    6.14  745.01    30.7  737.02   42.97  735.03   76.74  732.32
   95.15  731.62   98.22  730.53  113.57  720.32  116.64  719.59   141.2  719.08
  153.48  718.22  174.96   719.7  227.14  719.37  236.35  718.36  257.84  719.26
  310.02  717.22   322.3   717.8  328.44  719.31  337.65  720.55  343.76   720.7
  371.15  718.66  399.79   718.5  433.22   720.3  484.14  720.49  487.13  721.45
  490.13  723.61  499.11  731.33  511.09  742.52  514.08  743.24  520.07  747.77
#Mann= 3 , 0 , 0
       0      .1       0  227.14      .1       0  328.44      .1       0
Bank Sta=227.14,328.44
XS Rating Curve= 0 ,0
Exp/Cntr=0.3,0.1

Type RM Length L Ch R = 1 ,5943.6  ,96.62,91.44,101.39
XS GIS Cut Line= 6
     633831.3313    4314762.4696     633809.2192    4315128.0312
     633808.0101    4315138.0595     633807.8632    4315161.0606
     633825.7227     4315211.067     633844.6896    4315317.0288
#Sta/Elev= 30
       0  747.29   12.21  740.96   27.47  737.51   57.99  731.94    76.3  730.85
  100.71   719.6  103.77  719.04  119.02  718.82  128.18  716.44  131.23  716.29
  143.44  717.94  210.58  720.92  231.95  720.13   241.1  718.98  247.21  717.28
  268.57   716.6  326.55  717.37  335.71  718.53  347.92  718.92  384.96  716.66
  396.46  717.39  452.43  718.23  503.26  718.23  521.21  718.98  527.19  720.01
  530.18  721.46  551.11  741.46   554.1  743.78  557.09  744.42  560.08  747.35
#Mann= 3 , 0 , 0
       0      .1       0  247.21      .1       0  396.46      .1       0
Bank Sta=247.21,396.46
XS Rating Curve= 0 ,0
Exp/Cntr=0.3,0.1

Type RM Length L Ch R = 1 ,5852.16 ,94.68,91.44,90.07
XS GIS Cut Line= 4
     633751.9782    4314741.8982     633717.8919    4315137.5073
     633720.2248    4315193.0719     633737.0488    4315378.8569
#Sta/Elev= 30
       0  755.02   15.27   746.5   18.33  746.46   45.82  736.26   48.87  736.11
   82.47  726.69  103.85  718.25  109.96  717.63  122.18  718.05  131.34  715.17
  137.45   715.4  146.61  716.97  186.32  717.54  204.65  716.88  271.84  716.88
   308.5  715.28  314.61  714.47  351.26  715.47  363.48  713.76  375.69  715.82
  411.71  716.82   458.8  714.74   495.5  715.15  550.55  716.34  584.19  718.62
  593.36  721.96  614.77  739.19  617.83  741.05  620.89  741.79  639.23   755.5
#Mann= 3 , 0 , 0
       0      .1       0   308.5      .1       0   495.5      .1       0
Bank Sta=308.5,495.5
XS Rating Curve= 0 ,0
Exp/Cntr=0.3,0.1

Type RM Length L Ch R = 1 ,5760.72 ,91.64,91.44,100.07
XS GIS Cut Line= 5
     633569.3933    4314765.1154       633626.35    4315140.5474
      633626.894    4315147.7401     633624.7633    4315158.4368
     633652.7372    4315356.4604
#Sta/Elev= 30
       0  746.85   15.31  742.01   21.44  741.12   36.75  737.16   52.06  734.45
    73.5  721.62   76.56  720.08   79.62  719.72   85.75  715.42   88.81  714.25
   91.87  714.62   97.99  716.72  104.12  717.26  171.49  715.78  202.11  714.58
   211.3  713.28  220.49  714.86  293.98   713.7  318.48   714.5  376.32  714.22
  397.85  712.71  419.06   713.9  537.23  716.64  549.36  720.95  555.42  721.97
  561.48  724.11  570.57  729.23  579.66  735.64  585.72  737.83  597.84  745.71
#Mann= 3 , 0 , 0
       0      .1       0  376.32      .1       0  419.06      .1       0
Bank Sta=376.32,419.06
XS Rating Curve= 0 ,0
Exp/Cntr=0.3,0.1

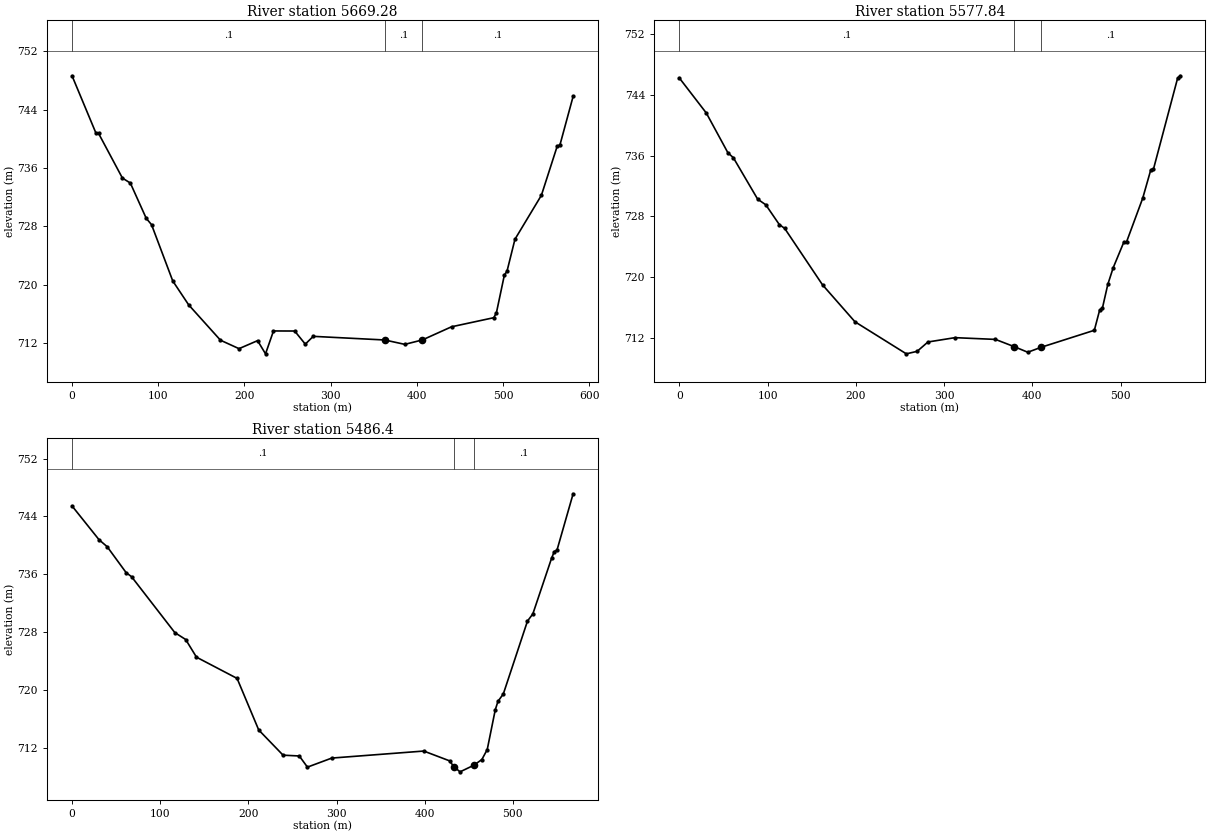
Type RM Length L Ch R = 1 ,5669.28 ,96.57,91.44,82.34
XS GIS Cut Line= 4
     633492.6639    4314766.4383     633535.8152    4315138.9841
     633535.5857    4315158.0266     633549.5495    4315344.5541
#Sta/Elev= 30
       0  748.65   27.67   740.8   30.74  740.75   58.41  734.62   67.63  733.93
   86.07  729.09   92.22  728.22  116.81   720.5  135.26  717.22  172.15  712.37
  193.67  711.21  215.18  712.31  224.41   710.5  233.63  713.64  258.22  713.63
  270.52  711.83  279.74   712.9  362.74   712.4  385.92   711.8  406.35  712.41
  440.08  714.21  489.14  715.46   492.2  716.15   501.4  721.31  504.47  721.84
  513.67  726.22  544.33  732.25  562.73  739.01   565.8  739.14  581.13  745.82
#Mann= 3 , 0 , 0
       0      .1       0  362.74      .1       0  406.35      .1       0
Bank Sta=362.74,406.35
XS Rating Curve= 0 ,0
Exp/Cntr=0.3,0.1

Type RM Length L Ch R = 1 ,5577.84 ,95.49,91.44,82.71
XS GIS Cut Line= 5
     633405.3513    4314779.6675     633426.4308    4315118.9028
     633451.9442    4315177.6609     633456.0679    4315197.8168
     633466.2056    4315340.5853
#Sta/Elev= 30
       0  746.22   30.62   741.6   55.12  736.36   61.24  735.72    88.8  730.26
   97.99  729.52   113.3  726.92  119.42  726.41  162.29  718.98  199.03  714.12
  257.21   709.9  269.46  710.23  281.71  711.46  312.33  712.03  358.19   711.8
  379.54  710.84   394.8  710.11  409.83  710.76   470.2     713  476.29  715.69
  479.34  715.91  485.43  719.03  491.52  721.22   503.7  724.63  506.74  724.65
  525.02  730.39  534.15  734.12   537.2  734.22   564.6  746.21  567.65   746.5
#Mann= 3 , 0 , 0
       0      .1       0  379.54      .1       0  409.83      .1       0
Bank Sta=379.54,409.83
XS Rating Curve= 0 ,0
Exp/Cntr=0.3,0.1

Type RM Length L Ch R = 1 ,5486.4  ,81.54,91.44,107.49
XS GIS Cut Line= 6
     633361.1658    4314779.9321     633357.8191    4315200.2973
     633367.4625    4315212.3544     633370.4925    4315217.9479
     633375.8789    4315230.3064     633409.8492    4315337.6749
#Sta/Elev= 30
       0  745.45   30.68  740.78   39.89  739.82   61.37  736.24   67.51  735.68
   116.6  727.96  128.88  727.01  141.15  724.57  187.18  721.64  211.72  714.52
  239.34  711.04  257.75  710.93  266.96  709.39  294.57  710.64   398.9  711.61
   428.1  710.26  433.24  709.42  440.06  708.74  455.66  709.65  464.79  710.44
  470.88  711.82  480.01  717.32  483.05  718.47  489.14   719.5  516.53  729.56
  522.62  730.55  543.93  738.26  546.97  739.16  550.01  739.36  568.28  747.13
#Mann= 3 , 0 , 0
       0      .1       0  433.24      .1       0  455.66      .1       0
Bank Sta=433.24,455.66
XS Rating Curve= 0 ,0
Exp/Cntr=0.3,0.1