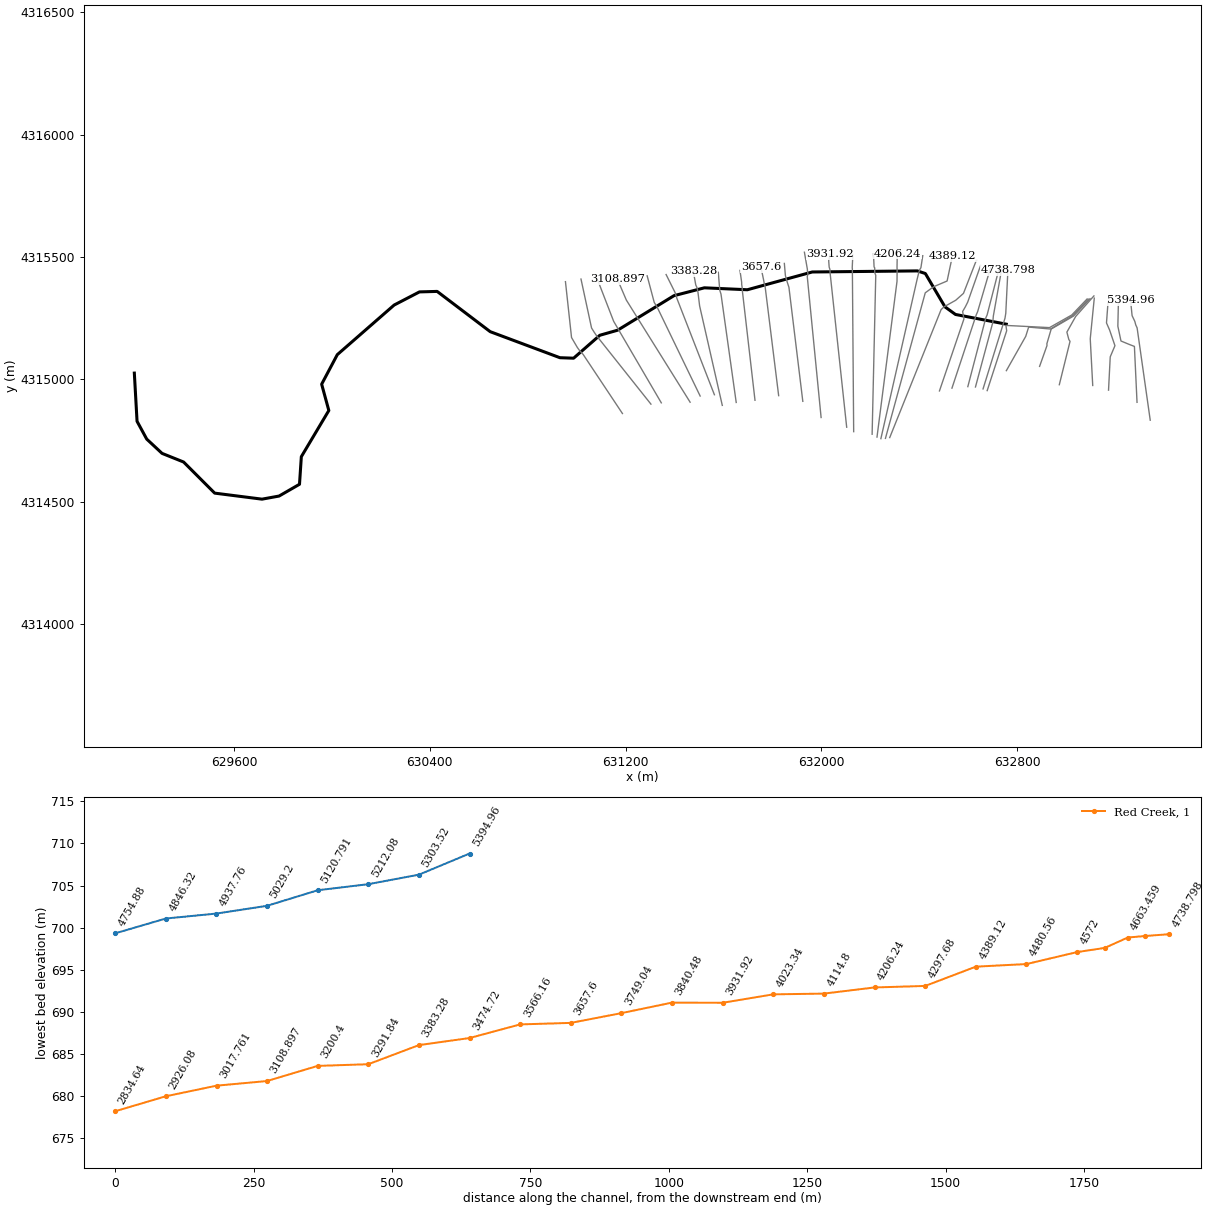
HEC-RAS study RedCreek.prj: RedCreek

--- RedCreek.g01 (geometry) --- (continued)

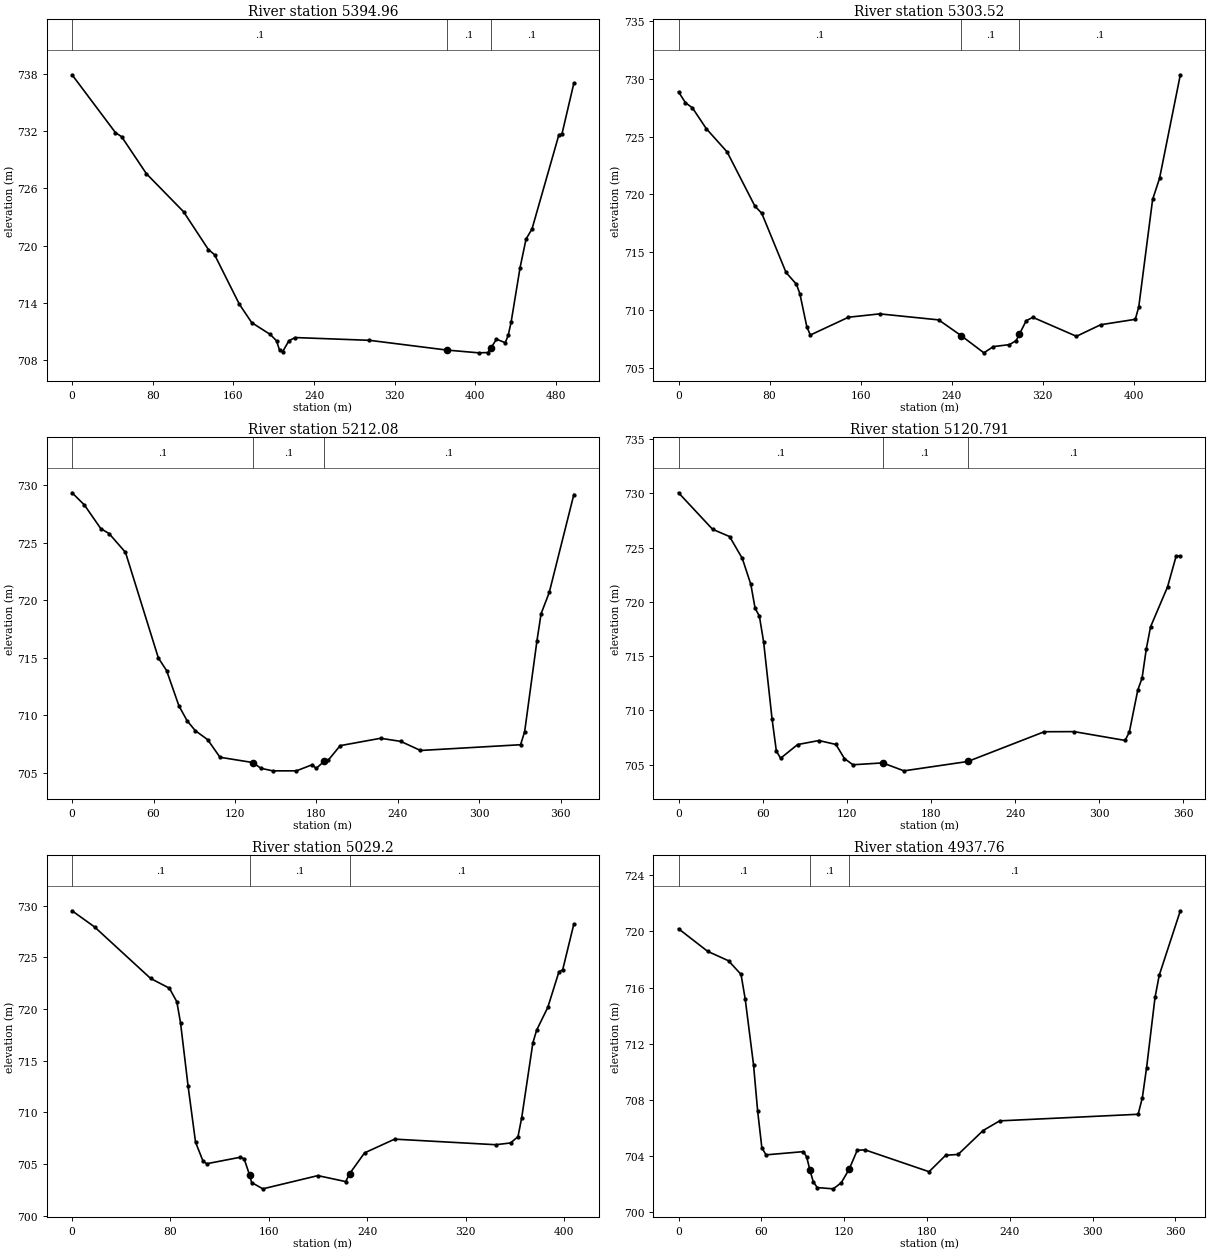
Type RM Length L Ch R = 1 ,5394.96 ,82.34,91.44,70.14
XS GIS Cut Line= 6
     633343.2623    4314833.5544     633289.6297    4315210.6566
     633284.1668     4315222.387     633280.3294    4315237.0321
     633269.1615    4315260.5783     633262.8288    4315322.5054
#Sta/Elev= 30
       0  737.89      43  731.84   49.15  731.41   73.72  727.54  110.58  723.56
  135.16  719.61   141.3  719.07  165.87  713.89  178.16  711.96  196.59  710.72
  202.74  710.06  205.81  709.06  208.88  708.93  215.02  710.06  221.17   710.4
  294.89  710.11  371.68  709.09  403.25   708.8   412.2  708.83  415.09  709.26
  420.89  710.23  429.57  709.86  432.47  710.62  435.36  711.99  444.26  717.71
  450.19   720.7  456.11  721.76  482.79  731.62  485.76  731.68  497.61  737.01
#Mann= 3 , 0 , 0
       0      .1       0  371.68      .1       0  415.09      .1       0
Bank Sta=371.68,415.09
XS Rating Curve= 0 ,0
Exp/Cntr=0.3,0.1

Type RM Length L Ch R = 1 ,5303.52 ,110.2,91.44,40.8
XS GIS Cut Line= 6
     633289.2871    4314906.5796     633278.6233     4315134.858
     633254.6275     4315144.154     633223.7073     4315157.017
     633210.9397    4315217.4938      633213.087    4315308.7471
#Sta/Elev= 30
       0  728.86    6.09  727.92   12.19  727.48   24.38  725.68   42.66  723.67
   67.03  718.99   73.13  718.36   94.46  713.24   103.6  712.22  106.65  711.38
  112.74  708.53  115.79  707.83   149.3  709.37  176.73  709.66  228.53  709.14
  248.54  707.76  268.26  706.29  276.62  706.83   290.7     707  296.59  707.34
  299.53  707.91  305.42  709.07  311.31  709.36  349.57  707.72  370.87  708.72
  401.29  709.19  404.34  710.27  416.51  719.56  422.59  721.38  440.85  730.34
#Mann= 3 , 0 , 0
       0      .1       0  248.54      .1       0  299.53      .1       0
Bank Sta=248.54,299.53
XS Rating Curve= 0 ,0
Exp/Cntr=0.3,0.1

Type RM Length L Ch R = 1 ,5212.08 ,87.46,91.29,72.56
XS GIS Cut Line= 6
     633172.8702    4314956.3214     633179.8323    4315092.3134
     633199.0784    4315137.7957     633176.9625    4315202.4954
     633164.5271    4315230.8059     633170.7536    4315315.0971
#Sta/Elev= 30
       0  729.33    9.08  728.27   21.18  726.21   27.23  725.79   39.34  724.15
   63.55  714.97    69.6  713.88   78.68  710.81   84.73  709.51   90.78  708.65
   99.86  707.87  108.94  706.34  133.14  705.88  139.08  705.38  147.79  705.16
  165.22  705.16  176.84  705.69  179.75  705.37  185.56  705.98  188.53  706.07
  197.45  707.35  227.18  707.99  242.04  707.72  256.59  706.93  330.29  707.43
   333.3  708.57  342.36  716.47  345.38  718.81  351.42  720.67  369.53  729.18
#Mann= 3 , 0 , 0
       0      .1       0  133.14      .1       0  185.56      .1       0
Bank Sta=133.14,185.56
XS Rating Curve= 0 ,0
Exp/Cntr=0.3,0.1

Type RM Length L Ch R = 1 ,5120.791,103.73,91.59,99.91
XS GIS Cut Line= 3
     633108.3118    4314975.3714     633098.1614     4315166.151
     633114.6618    4315332.0304
#Sta/Elev= 30
       0  730.04   24.26  726.68   36.39  726.01   45.49  723.99   51.55   721.6
   54.59   719.4   57.62   718.7   60.65  716.32   66.72  709.17   69.75  706.26
   72.78   705.6   84.91  706.86  100.07  707.23   112.2  706.87  118.27  705.57
  124.33     705  145.56  705.17  160.72  704.44   206.2   705.3  260.76  708.04
  281.98  708.05  318.35  707.24  321.38     708  327.44  711.89  330.47  712.97
   333.5  715.67  336.53   717.7  348.65  721.38  354.72  724.19  357.75  724.23
#Mann= 3 , 0 , 0
       0      .1       0  145.56      .1       0   206.2      .1       0
Bank Sta=145.56,206.2
XS Rating Curve= 0 ,0
Exp/Cntr=0.3,0.1

Type RM Length L Ch R = 1 ,5029.2  ,87.33,91.44,69.45
XS GIS Cut Line= 6
     632971.7865    4314978.5464     633015.6057    4315155.5636
     633010.6627    4315163.0791     633002.7252    4315193.2416
     633038.7086    4315257.2709     633113.2066    4315341.0263
#Sta/Elev= 30
       0   729.5   18.26  727.94    63.9  722.95   79.12  722.01    85.2   720.7
   88.24  718.64   94.33  712.56  100.42  707.11   106.5  705.27  109.54  705.02
  136.93  705.65  139.97  705.49  144.43  703.91  146.06   703.2  155.17  702.59
   199.9  703.87  222.59  703.29  225.65  704.04  237.89  706.07  262.37   707.4
  344.51  706.86  356.63  707.03  362.69  707.64  365.72  709.48   374.8  716.72
  377.83  717.94  386.92  720.15  396.01   723.6  399.04  723.79  408.13  728.22
#Mann= 3 , 0 , 0
       0      .1       0  144.43      .1       0  225.65      .1       0
Bank Sta=144.43,225.65
XS Rating Curve= 0 ,0
Exp/Cntr=0.3,0.1

Type RM Length L Ch R = 1 ,4937.76 ,95.94,91.44,92.06
XS GIS Cut Line= 6
     632891.2207    4315053.3795     632921.5332    4315138.6944
     632920.9238    4315145.7351     632938.6525    4315205.8939
      633029.791    4315258.7058     633097.2599     4315329.482
#Sta/Elev= 30
       0  720.19   21.13  718.58   36.22  717.91   45.27  716.94   48.29   715.2
   54.32  710.52   57.34  707.19   60.36   704.6   63.38  704.09   90.54  704.32
    92.9  703.92   95.25  702.98   97.61  702.18   100.5  701.76   112.1  701.67
  117.89   702.1  123.69  703.08  129.48  704.42  135.28  704.44  181.52  702.89
  193.56  704.06  202.59  704.12  220.65  705.82  232.68  706.51  333.01  706.98
  336.07  708.17  339.13   710.3  345.24   715.3  348.29  716.88  363.57  721.47
#Mann= 3 , 0 , 0
       0      .1       0   95.25      .1       0  123.69      .1       0
Bank Sta=95.25,123.69
XS Rating Curve= 0 ,0
Exp/Cntr=0.3,0.1

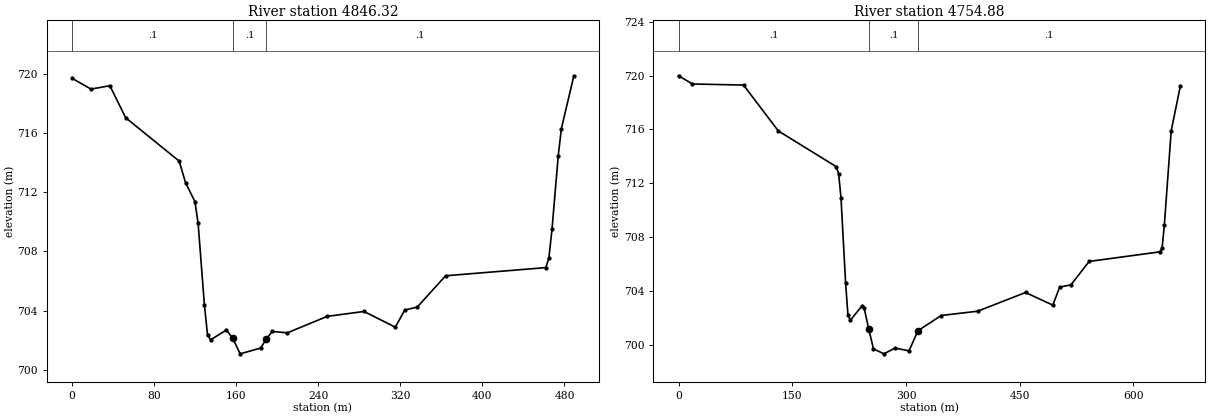
Type RM Length L Ch R = 1 ,4846.32 ,81.11,91.44,43.73
XS GIS Cut Line= 6
      632755.401    4315035.8817     632834.6206    4315175.9523
     632846.4807    4315213.7993     632935.6984    4315205.8618
     633027.4949     4315261.428     633090.1878    4315327.8059
#Sta/Elev= 30
       0  719.68   18.43  718.95   36.86  719.18   52.22  717.02  104.43  714.09
  110.58  712.64  119.79  711.35  122.86   709.9     129  704.39  132.08  702.34
  135.15  702.03  150.51  702.69  156.65  702.12  163.87  701.08  183.76  701.47
  189.32  702.07  195.15  702.59  209.95   702.5  248.76  703.61  284.59  703.94
  315.09  702.88  324.29  704.03  336.55  704.24  364.14  706.35  461.78   706.9
  464.82  707.54  467.87   709.5  473.95  714.45     477  716.28  489.17  719.85
#Mann= 3 , 0 , 0
       0      .1       0  156.65      .1       0  189.32      .1       0
Bank Sta=156.65,189.32
XS Rating Curve= 0 ,0
Exp/Cntr=0.3,0.1

Type RM Length L Ch R = 1 ,4754.88 ,21.72,16.08,32.79
XS GIS Cut Line= 6
     632677.0842    4314954.3899     632756.7531    4315198.8228
     632753.5924    4315220.6231     632931.6271    4315211.5945
     633022.8259     4315263.271     633085.2312    4315328.5115
#Sta/Elev= 30
       0  719.99   18.36  719.38    85.7   719.3   131.6  715.89  208.12  713.23
  211.18  712.68  214.24  710.93  220.36  704.57  223.42  702.21  226.48  701.81
  241.79  702.87  244.85  702.71  250.97  701.13  257.09  699.69  270.86  699.32
  285.55  699.75  303.96  699.54  315.75  701.04  346.46  702.17  394.54  702.49
  457.65  703.88  493.62  702.94   502.6  704.28  517.58  704.45  541.54  706.19
  634.68   706.9  637.69  707.17   640.7  708.89  649.73  715.89  661.77  719.23
#Mann= 3 , 0 , 0
       0      .1       0  250.97      .1       0  315.75      .1       0
Bank Sta=250.97,315.75
XS Rating Curve= 0 ,0
Exp/Cntr=0.3,0.1

River Reach=Red Creek       ,1
Reach XY= 30
     632755.1003    4315225.6854     632547.5342     4315265.373
     632504.6717    4315296.3293     632424.5027    4315432.4577
     632391.9589    4315443.1734     631962.5393    4315438.8077
631697.2583550574315366.24645896     631521.6103     4315374.117
      631397.403    4315341.9949     631167.2002    4315201.0791
      631094.572    4315180.4416     630987.4155    4315086.7789
      630931.456    4315088.7633     630646.6315    4315195.0599
      630429.805    4315359.4326     630357.5736    4315357.4482
     630254.1845     4315303.803630021.9037144484315101.23778292
 629957.977946054314980.66634078     629987.2885    4314873.1936
     629874.9726    4314684.6776      629867.432    4314571.9649
     629784.0881    4314523.9429     629714.2379    4314511.2429
     629520.9594    4314535.8492     629393.9592    4314662.8494
     629305.8528    4314698.1714     629243.2517    4314756.4531
      629203.744    4314829.1673      629192.671    4315025.9183

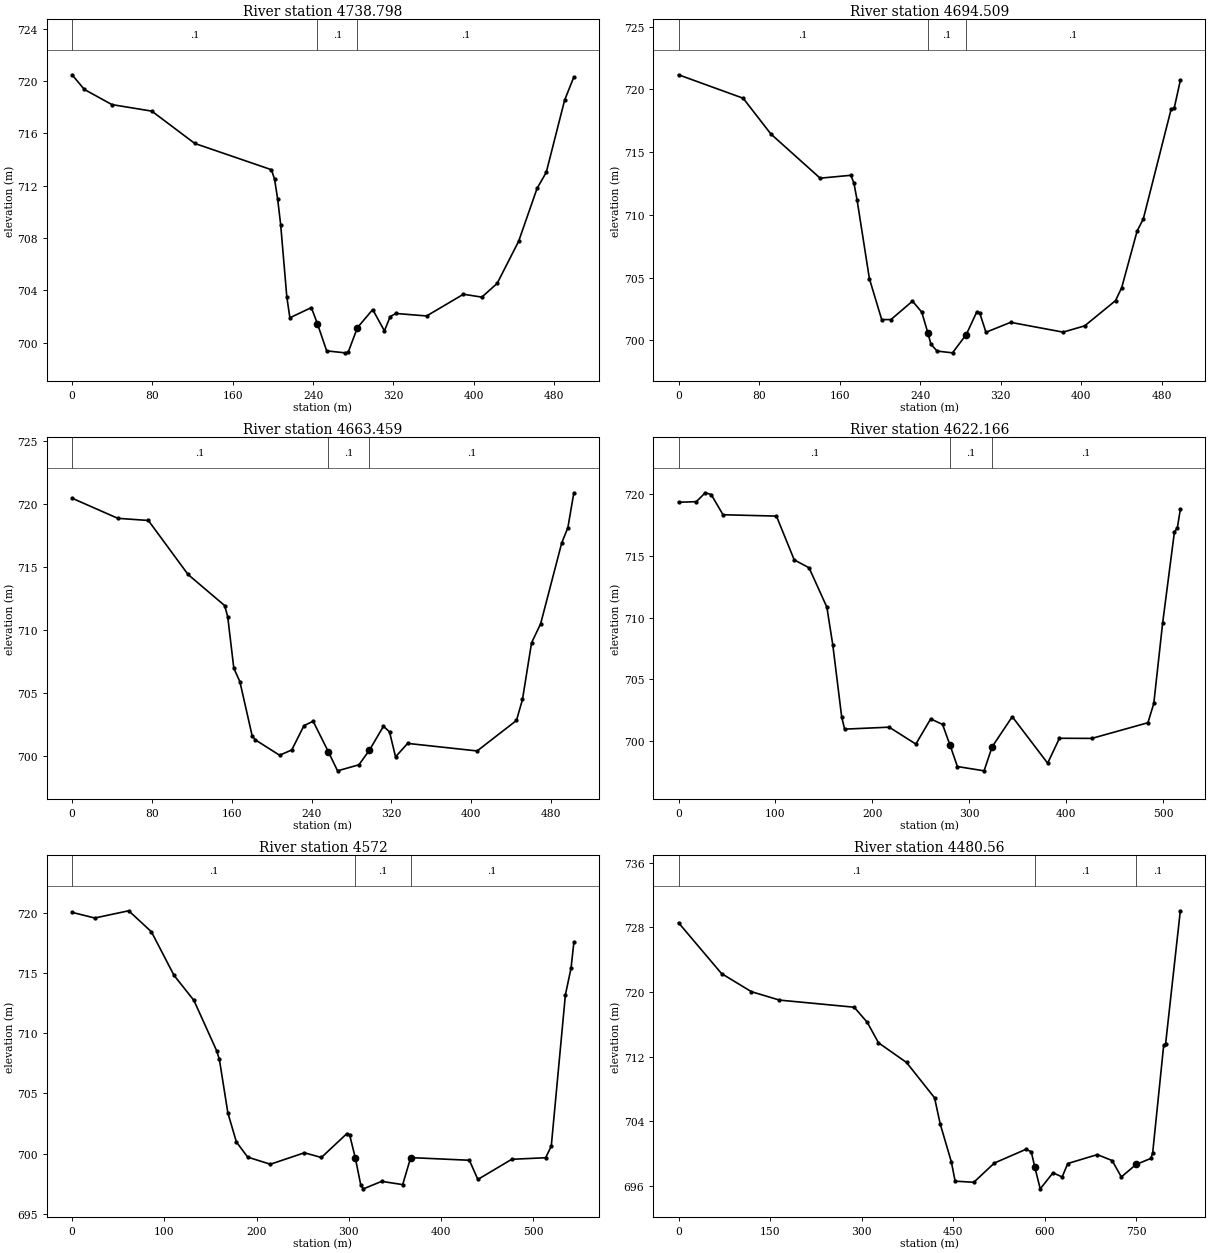
Type RM Length L Ch R = 1 ,4738.798,41.43,44.29,48.36
XS GIS Cut Line= 4
     632660.1843     4314961.342     632749.8782    4315250.2676
     632753.0532    4315270.1114     632761.7845     4315447.118
#Sta/Elev= 30
       0  720.48   12.22  719.36   39.73   718.2   79.45   717.7  122.23  715.23
  198.63  713.22  201.69   712.5  204.74  711.01   207.8  709.02  213.91   703.5
  216.96   701.9  238.36  702.68  244.47  701.43  253.63  699.37  271.97  699.22
  275.03  699.26  284.19  701.14  299.47  702.53  311.14   700.9  316.88  701.99
  322.62  702.23  353.18  702.04  389.85   703.7  408.18  703.48  423.46  704.53
  444.85  707.75  463.18  711.79  472.35  713.02  490.68  718.55  499.85  720.31
#Mann= 3 , 0 , 0
       0      .1       0  244.47      .1       0  284.19      .1       0
Bank Sta=244.47,284.19
XS Rating Curve= 0 ,0
Exp/Cntr=0.3,0.1

Type RM Length L Ch R = 1 ,4694.509,32.88,31.05,25.4
XS GIS Cut Line= 4
      632629.228    4314969.2795     632699.8719    4315232.0113
     632702.2531    4315258.9988     632737.1782    4315455.0555
#Sta/Elev= 30
       0  721.16   64.19  719.29   91.71  716.44  140.62  712.92  171.19  713.15
  174.24   712.5   177.3  711.18  189.53  704.91  201.75  701.65  210.93  701.65
  232.32  703.12  241.49  702.25  247.61  700.59  250.67  699.68  256.78  699.14
  272.06     699  285.75  700.46  296.15  702.26  299.16  702.16  305.28  700.64
  329.79  701.43  381.88  700.65  403.32  701.15  433.96  703.16  440.09   704.2
  455.41  708.71  461.53  709.67  489.11   718.4  492.17  718.48   498.3  720.71
#Mann= 3 , 0 , 0
       0      .1       0  247.61      .1       0  285.75      .1       0
Bank Sta=247.61,285.75
XS Rating Curve= 0 ,0
Exp/Cntr=0.3,0.1

Type RM Length L Ch R = 1 ,4663.459,43.46,41.29,40.77
XS GIS Cut Line= 4
     632597.9857     4314970.599     632671.4593    4315251.5655
     632676.6951    4315262.8686     632726.5735    4315456.3749
#Sta/Elev= 30
       0  720.48   45.85  718.88   76.42  718.71  116.17  714.42  152.85  711.95
  155.91  711.07  162.02  706.98  168.13   705.9  180.36  701.62  183.42  701.29
  207.88  700.06   220.1  700.48  232.33  702.41   241.5  702.76  256.79  700.33
  265.96  698.82  287.36   699.3  297.89  700.46  311.95  702.36  318.01  701.92
  324.07  699.93  336.18     701  405.81   700.4  445.18  702.82  451.23  704.49
  460.31  708.99   469.4   710.5  490.59  716.94  496.65  718.12   502.7  720.91
#Mann= 3 , 0 , 0
       0      .1       0  256.79      .1       0  297.89      .1       0
Bank Sta=256.79,297.89
XS Rating Curve= 0 ,0
Exp/Cntr=0.3,0.1

Type RM Length L Ch R = 1 ,4622.166,42.46,50.17,53.5
XS GIS Cut Line= 4
      632533.184     4314964.517      632632.403    4315263.7614
     632637.9592    4315276.4614     632691.1406    4315457.4367
#Sta/Elev= 30
       0  719.36   18.36  719.41   27.55  720.13   33.67  719.99   45.91  718.35
  101.01  718.24  119.37  714.69  134.68  714.05  153.04  710.86  159.16   707.8
  168.35  701.95  171.41  700.97  217.32  701.13  244.87  699.76  260.17   701.8
  272.41  701.35  280.23  699.65  287.72  697.94  315.26  697.59  323.58  699.54
  344.34  701.98  380.85  698.21  393.02  700.23  426.48  700.22  484.29  701.49
  490.37  703.05   499.5  709.57  511.67  716.96  514.71   717.3  517.75  718.78
#Mann= 3 , 0 , 0
       0      .1       0  280.23      .1       0  323.58      .1       0
Bank Sta=280.23,323.58
XS Rating Curve= 0 ,0
Exp/Cntr=0.3,0.1

Type RM Length L Ch R = 1 ,4572    ,99.44,91.44,44.41
XS GIS Cut Line= 6
      632482.098    4314953.1364     632582.1058    4315246.8138
     632576.8108    4315277.4689     632588.2416    4315297.2306
      632597.502    4315315.7514     632650.3733       4315465.9
#Sta/Elev= 30
       0  720.02   24.57  719.55   61.43  720.15   86.01  718.41  110.58  714.79
  132.08  712.72  156.66  708.56  159.73  707.82  168.94  703.38  178.16  700.98
  190.44  699.72  215.02  699.13  251.88  700.08  270.31  699.69  297.95  701.67
  301.02  701.55  307.17  699.63  313.07  697.39  315.89  697.09  335.69  697.71
  358.47  697.44  367.14  699.68   430.8  699.46  439.99  697.87  476.72  699.54
  513.46  699.67  519.58  700.63  534.89  713.18  541.01  715.39  544.07  717.53
#Mann= 3 , 0 , 0
       0      .1       0  307.17      .1       0  367.14      .1       0
Bank Sta=307.17,367.14
XS Rating Curve= 0 ,0
Exp/Cntr=0.3,0.1

Type RM Length L Ch R = 1 ,4480.56 ,92.04,91.44,87.39
XS GIS Cut Line= 6
     632278.8976    4314762.6361     632488.9177    4315285.3419
     632501.6228    4315297.0561     632548.4931    4315323.2833
     632580.2432    4315351.4614     632632.9108    4315486.5375
#Sta/Elev= 30
       0  728.56   70.42  722.28   119.4  720.04  165.32     719  287.78  718.12
  309.21  716.25  327.58  713.72  373.51  711.29  419.43  706.92  428.61  703.71
  446.98  698.99  453.11  696.62  483.72  696.48   517.4  698.86  569.25  700.56
   577.9  700.25  583.61  698.36  592.56  695.67  613.46  697.65  628.47  697.14
  637.65   698.8  686.13   699.9  710.29  699.17  725.39  697.14  749.55  698.68
  773.72  699.43  776.74  700.11  794.86  713.46  797.88  713.55  822.05  730.04
#Mann= 3 , 0 , 0
       0      .1       0  583.61      .1       0  749.55      .1       0
Bank Sta=583.61,749.55
XS Rating Curve= 0 ,0
Exp/Cntr=0.3,0.1

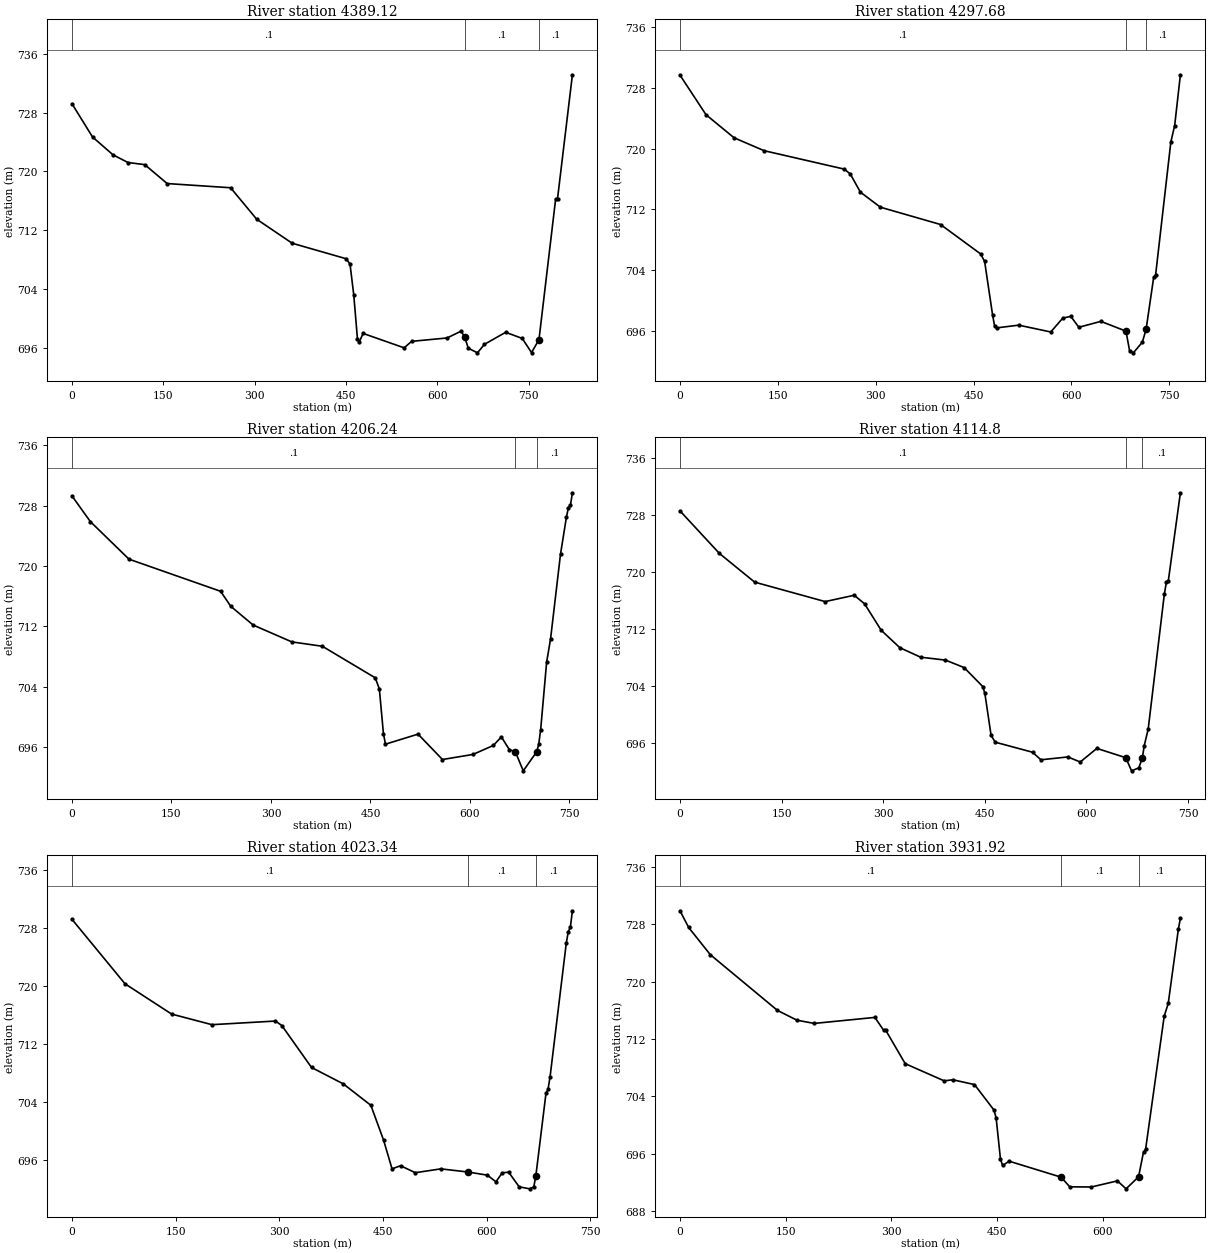
Type RM Length L Ch R = 1 ,4389.12 ,82.24,91.44,122.25
XS GIS Cut Line= 6
     632261.4351     4314759.461     632424.0399    4315353.6517
     632449.7334    4315372.4684     632462.6297    4315380.4816
      632513.337    4315401.9383     632534.8344    4315503.4724
#Sta/Elev= 30
       0   729.2   33.71  724.69   67.43  722.26   91.95  721.22  119.53  720.93
  156.31  718.36  260.51  717.79  303.42  713.51  361.65  710.25  450.54  708.14
  456.67   707.4   462.8  703.22  468.92  697.18  471.99  696.86  478.12     698
  545.55  696.04  557.81  696.92  616.04  697.38   639.2  698.31  644.99  697.49
  650.92  695.99  665.95  695.36  677.48  696.52  712.32  698.15   739.5  697.32
  754.76   695.4  766.97  697.13  794.44   716.3   797.5  716.32  821.92  733.14
#Mann= 3 , 0 , 0
       0      .1       0  644.99      .1       0  766.97      .1       0
Bank Sta=644.99,766.97
XS Rating Curve= 0 ,0
Exp/Cntr=0.3,0.1

Type RM Length L Ch R = 1 ,4297.68 ,90.43,91.44,98.21
XS GIS Cut Line= 6
     632242.7819    4314758.2704     632390.6935    4315408.2398
     632397.4707    4315435.6998     632401.7639    4315448.7382
      632406.304    4315456.1295     632413.8486    4315505.2496
#Sta/Elev= 30
       0  729.68   39.93  724.46   82.94  721.42  129.02  719.72  251.89  717.29
  261.11  716.64  276.46  714.26  307.18  712.27  399.34  709.99  460.77  706.11
  466.92  705.12  479.21  698.01  482.28  696.59  485.35  696.36  519.14  696.72
  568.29  695.82  586.72  697.65  599.01  697.88  611.29  696.44  645.08  697.22
  683.56  695.93  689.21   693.3  694.87  693.07   708.6  694.47  714.38  696.15
  726.04  703.04  728.97  703.33  752.35  720.88   758.2  723.04  766.97  729.73
#Mann= 3 , 0 , 0
       0      .1       0  683.56      .1       0  714.38      .1       0
Bank Sta=683.56,714.38
XS Rating Curve= 0 ,0
Exp/Cntr=0.3,0.1

Type RM Length L Ch R = 1 ,4206.24 ,97.61,91.44,94.75
XS GIS Cut Line= 5
     632226.9069    4314764.6204     632308.6957     4315400.805
     632309.1736    4315448.7687     632308.7323    4315457.0486
     632309.6891    4315513.8646
#Sta/Elev= 30
       0  729.28   27.62  725.89   85.93  720.91  224.04  716.66  239.38  714.67
  273.14  712.19  331.45  709.96  377.49  709.38  457.28   705.2  463.42  703.72
  469.56  697.83  472.63  696.42  521.73  697.75  558.56  694.39  604.59  695.06
  635.28  696.25  647.42  697.38  659.41   695.7   668.4  695.43  680.39  692.89
  700.67  695.41  703.66  696.38  706.65  698.35  715.62  707.27   721.6  710.38
  736.56  721.58  745.53   726.5  748.52  727.75  751.51  728.03   754.5   729.7
#Mann= 3 , 0 , 0
       0      .1       0   668.4      .1       0  700.67      .1       0
Bank Sta=668.4,700.67
XS Rating Curve= 0 ,0
Exp/Cntr=0.3,0.1

Type RM Length L Ch R = 1 ,4114.8  ,93.19,91.46,88.9
XS GIS Cut Line= 6
     632207.0102    4314776.2621     632221.8516    4315425.0695
     632217.6465    4315436.4472     632217.6688     4315455.233
     632214.9724      4315459.73     632212.5103    4315513.1378
#Sta/Elev= 30
       0  728.64   58.16  722.67   110.2  718.64  214.29  715.91  257.14   716.8
  272.45   715.6  296.94  711.89  324.49  709.44   355.1  708.11  391.83   707.7
  419.39  706.65  446.94  703.98     450  703.02  459.18  697.14   465.3  696.18
  520.41  694.77  532.65  693.71  572.45  694.11  590.81   693.4   615.3  695.31
  658.07     694  666.47  692.16  677.21  692.58  682.51  693.99  685.14  695.66
  691.08  698.02  714.84  716.91  717.81  718.59  720.78  718.83   738.6  731.18
#Mann= 3 , 0 , 0
       0      .1       0  658.07      .1       0  682.51      .1       0
Bank Sta=658.07,682.51
XS Rating Curve= 0 ,0
Exp/Cntr=0.3,0.1

Type RM Length L Ch R = 1 ,4023.34 ,90.14,91.42,95.16
XS GIS Cut Line= 4
     632131.6038    4314786.8455     632126.2714    4315452.5628
     632125.6753    4315455.1439     632128.2534    4315511.0182
#Sta/Elev= 30
       0  729.17    76.7   720.3  144.19  716.13  202.48  714.67  294.52  715.17
  303.72  714.55  346.68  708.78  392.69  706.52  432.58  703.57  450.98  698.78
  463.26  694.82  475.53  695.25     497  694.29  533.82  694.82   573.7  694.38
  601.31  693.95  613.58  693.04  622.79  694.27  631.99  694.37  647.33  692.34
  662.67  692.07  668.39  692.34  671.33   693.8  686.05  705.21  688.99  705.76
  691.94  707.46  715.49  725.93  718.43  727.49  721.38  728.09  724.32  730.35
#Mann= 3 , 0 , 0
       0      .1       0   573.7      .1       0  671.33      .1       0
Bank Sta=573.7,671.33
XS Rating Curve= 0 ,0
Exp/Cntr=0.3,0.1

Type RM Length L Ch R = 1 ,3931.92 ,96.48,91.44,89.87
XS GIS Cut Line= 6
     632103.0618    4314804.9695     632035.3441    4315434.4614
     632034.6447     4315448.773     632031.5011    4315458.7158
     632029.5233    4315485.1246     632035.4275     4315510.306
#Sta/Elev= 30
       0   729.9   12.29  727.57   43.03  723.77   138.3  715.99  165.96  714.62
  190.55  714.17  276.61  715.01   288.9  713.23  291.97  713.22  319.64  708.55
  374.96  706.15  387.25   706.3  417.98  705.63  445.65  702.07  448.72  700.95
  454.87  695.22  457.94  694.33  467.16  694.93  540.92   692.7  553.21  691.35
  583.95  691.33  620.83  692.18  633.12  691.07  650.86  692.75  657.88  696.22
  660.82  696.57  687.24  715.17  692.98  716.97  707.35  727.33  710.23  728.85
#Mann= 3 , 0 , 0
       0      .1       0  540.92      .1       0  650.86      .1       0
Bank Sta=540.92,650.86
XS Rating Curve= 0 ,0
Exp/Cntr=0.3,0.1

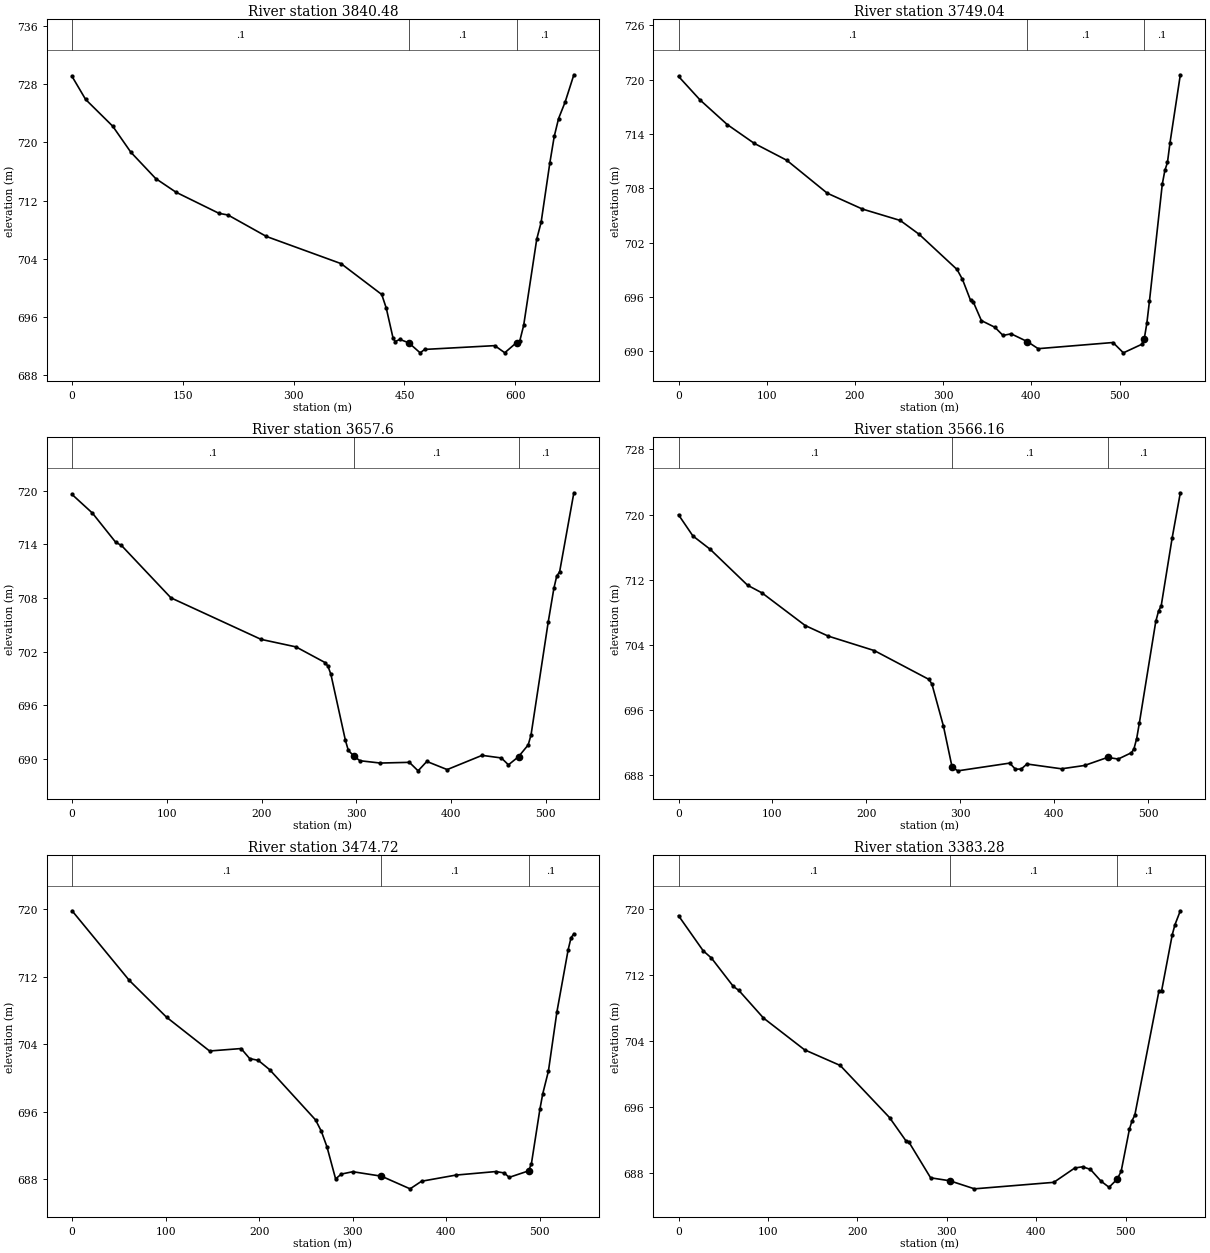
Type RM Length L Ch R = 1 ,3840.48 ,89.98,91.44,95.63
XS GIS Cut Line= 6
     631998.5512     4314844.657     631941.9747    4315420.2012
     631944.9139    4315429.6849     631942.5741     4315443.055
     631942.4847    4315449.6212     631930.3331    4315519.4731
#Sta/Elev= 30
       0  729.07   18.36  725.91   55.08  722.23   79.56  718.66  113.22  715.04
  140.75  713.16  198.89  710.26  211.13  710.03  263.15  707.08  364.13  703.35
   419.2  699.11  425.32  697.24   434.5  693.13  437.56  692.64  443.68  692.94
  455.92  692.46  471.22  691.09  477.34  691.56   572.2  692.08  585.76   691.1
  601.82  692.51   606.2  692.78  611.34  694.86  629.07  706.73  634.97  709.02
  646.79   717.2   652.7  720.82  658.61  723.29  667.47  725.55  679.29   729.3
#Mann= 3 , 0 , 0
       0      .1       0  455.92      .1       0  601.82      .1       0
Bank Sta=455.92,601.82
XS Rating Curve= 0 ,0
Exp/Cntr=0.3,0.1

Type RM Length L Ch R = 1 ,3749.04 ,92.29,91.44,91.91
XS GIS Cut Line= 5
     631923.8062    4314910.6377     631867.1041     4315376.191
     631856.2088    4315409.7618     631852.6489    4315424.2519
     631848.3998    4315473.7052
#Sta/Elev= 30
       0  720.35   24.52  717.74   55.18  715.04   85.83  712.96  122.61   711.1
  168.59  707.46  208.44  705.71  251.36  704.45  272.81  702.92  315.73  699.04
  321.86  697.95  331.05  695.63  334.12  695.46  343.32   693.4  358.64  692.66
  367.84  691.76  377.03  691.94  395.43  691.08  407.69   690.3  492.52  690.98
  504.29  689.84  525.05  690.78  527.97   691.4  530.89  693.11  533.81  695.52
  548.41  708.47  551.33  709.98  554.25  710.85  557.17  713.05  568.84  720.53
#Mann= 3 , 0 , 0
       0      .1       0  395.43      .1       0  527.97      .1       0
Bank Sta=395.43,527.97
XS Rating Curve= 0 ,0
Exp/Cntr=0.3,0.1

Type RM Length L Ch R = 1 ,3657.6  ,93.94,91.44,89.75
XS GIS Cut Line= 6
     631825.1164     4314933.921     631769.8916    4315378.5061
     631768.1465    4315385.8191     631766.5182     4315390.531
     631762.6634    4315411.0214      631752.719    4315458.1451
#Sta/Elev= 30
       0  719.56   21.48  717.48   46.03  714.22   52.16  713.86  104.33  708.01
  199.45  703.37  236.28  702.53  266.96  700.78  270.03  700.37   273.1  699.48
  288.44  692.09  291.51  690.97  297.65   690.3  303.78  689.81  325.26  689.55
  355.95  689.63  365.15  688.68  374.36  689.73  395.84  688.82  432.66  690.41
  453.01  690.12  460.51  689.35  471.11  690.26  481.37  691.58  484.38  692.72
  502.44  705.29  508.46  709.08  511.47  710.45  514.48  710.91  529.53  719.75
#Mann= 3 , 0 , 0
       0      .1       0  297.65      .1       0  471.11      .1       0
Bank Sta=297.65,471.11
XS Rating Curve= 0 ,0
Exp/Cntr=0.3,0.1

Type RM Length L Ch R = 1 ,3566.16 ,95.53,91.44,92.23
XS GIS Cut Line= 6
     631728.4551    4314915.0121     631676.0419    4315368.6459
       631676.52    4315371.0582      631674.029    4315388.5728
     631674.0064    4315396.4846     631666.9847    4315445.3364
#Sta/Elev= 30
       0  719.97   15.32  717.37   33.71  715.73   73.55  711.31   88.88  710.37
  134.85  706.36  159.37  705.06   208.4  703.28  266.64  699.73   269.7  699.16
  281.96  693.99  291.15  688.96  297.28   688.5  352.45  689.45  358.58   688.7
  364.71  688.72  370.84  689.34  407.62  688.75  432.13  689.16  456.65  690.15
  467.96  689.95  482.08  690.73  484.71   691.2  487.62  692.47  490.52  694.42
  507.94  706.86  510.84  708.12  513.75  708.81  525.36  717.12  534.07  722.68
#Mann= 3 , 0 , 0
       0      .1       0  291.15      .1       0  456.65      .1       0
Bank Sta=291.15,456.65
XS Rating Curve= 0 ,0
Exp/Cntr=0.3,0.1

Type RM Length L Ch R = 1 ,3474.72 ,91.53,91.44,96.26
XS GIS Cut Line= 6
     631651.7258    4314906.0163     631589.4983    4315348.9653
      631584.776    4315363.2066      631583.485    4315378.6984
     631582.9051     4315383.046     631578.5998    4315437.3218
#Sta/Elev= 30
       0  719.84   61.27  711.58   101.1  707.22  147.06  703.22  180.76  703.51
  189.95  702.32  199.14  702.11  211.39     701  260.41  695.05  266.54  693.72
  272.67  691.84  281.86  688.06  287.99  688.63  300.24  688.91  330.88  688.38
  361.52  686.88  373.77  687.78  410.53  688.51   453.3  688.93   462.3  688.76
  467.48  688.24  488.28  689.01  491.31  689.88  500.38  696.33  503.41  698.15
  509.46  700.83  518.53  707.84  530.63  715.25  533.66  716.64  536.68  717.11
#Mann= 3 , 0 , 0
       0      .1       0  330.88      .1       0  488.28      .1       0
Bank Sta=330.88,488.28
XS Rating Curve= 0 ,0
Exp/Cntr=0.3,0.1

Type RM Length L Ch R = 1 ,3383.28 ,90.05,91.44,93.07
XS GIS Cut Line= 6
     631594.8403      4314894.11     631502.2031    4315300.2422
     631495.5043    4315355.4674     631492.2219    4315373.2862
     631486.4854    4315385.6647     631476.4396    4315441.6547
#Sta/Elev= 30
       0  719.22   27.57  714.96   36.76  714.08   61.26  710.63   67.39  710.15
   94.95  706.79   140.9  702.93  180.71  701.03  235.85   694.7  254.23  691.87
  257.29  691.76  281.79  687.38  303.23  687.02   330.8  686.04  419.49  686.83
  442.91  688.57   451.7  688.72  460.48   688.4  472.19  686.98  481.25  686.23
  490.31  687.21  494.77  688.16  504.04  693.29  507.04  694.34  510.03  694.98
  536.98  710.05  539.97  710.08  551.95  716.93  554.94  718.13  560.93  719.82
#Mann= 3 , 0 , 0
       0      .1       0  303.23      .1       0  490.31      .1       0
Bank Sta=303.23,490.31
XS Rating Curve= 0 ,0
Exp/Cntr=0.3,0.1

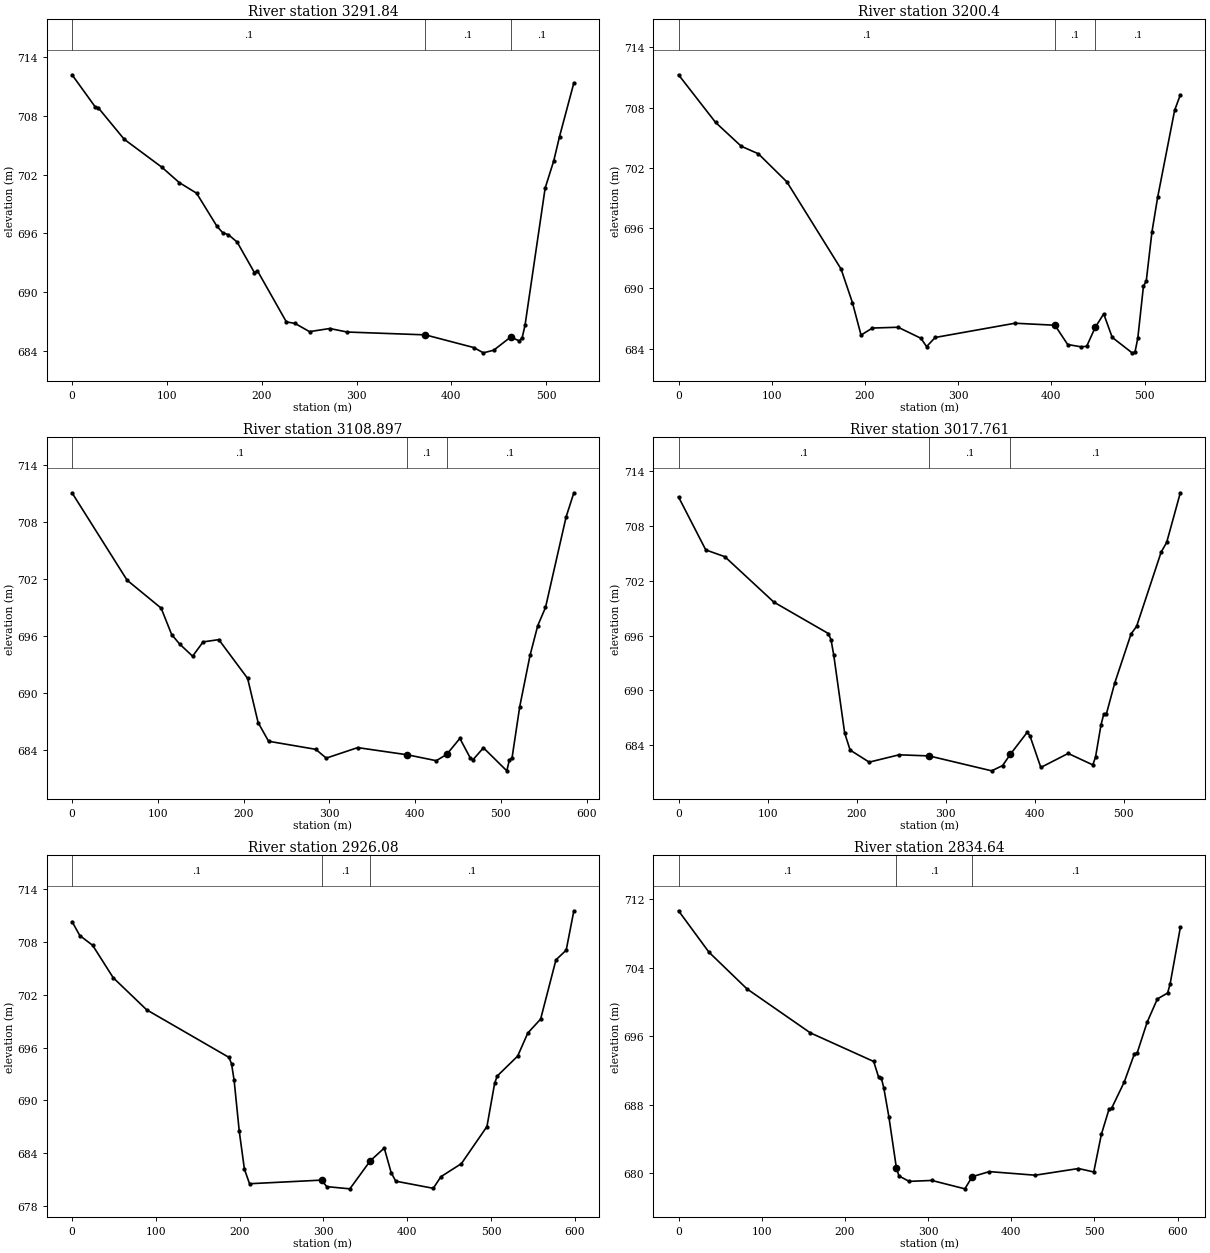
Type RM Length L Ch R = 1 ,3291.84 ,88.07,91.44,92.08
XS GIS Cut Line= 5
     631562.5941     4314937.601     631409.6123    4315330.2544
     631407.5763    4315336.7314     631401.8077    4315355.0835
     631365.3138    4315428.2387
#Sta/Elev= 30
       0  712.23   24.43  708.94   27.48  708.87   54.97  705.63   94.66  702.77
  112.98   701.2  131.31  700.11  152.68  696.74  158.79  696.07   164.9  695.86
  174.06  695.11  192.38  691.97  195.43  692.18  225.97  686.94  235.13  686.78
   250.4  685.94  271.77  686.26   290.1   685.9  372.54  685.61  423.67  684.31
  433.69  683.77  444.68  684.04  462.57  685.39  471.65  684.99  474.68  685.31
  477.71  686.61   498.9  700.63  507.99  703.43  514.04   705.9  529.18   711.4
#Mann= 3 , 0 , 0
       0      .1       0  372.54      .1       0  462.57      .1       0
Bank Sta=372.54,462.57
XS Rating Curve= 0 ,0
Exp/Cntr=0.3,0.1

Type RM Length L Ch R = 1 ,3200.4  ,91.89,91.5,97.52
XS GIS Cut Line= 4
     631504.3857    4314932.3093     631328.4317    4315295.7891
     631316.8067    4315314.3623     631287.8282    4315423.2192
#Sta/Elev= 30
       0  711.27   39.77  706.52    67.3  704.15   85.66   703.4  116.25   700.6
  174.38  691.92  186.62  688.56   195.8  685.34  208.03  686.04  235.57  686.12
  260.04  685.02  266.16  684.19  275.34   685.1     361  686.52  403.83  686.32
  417.52   684.4  431.83  684.17  437.92  684.22  447.05   686.1  456.19  687.45
  465.32  685.11  486.63  683.57  489.68  683.62  492.72     685  498.81   690.2
  501.85  690.74  507.94  695.61  514.03  699.05   532.3  707.74  538.39  709.27
#Mann= 3 , 0 , 0
       0      .1       0  403.83      .1       0  447.05      .1       0
Bank Sta=403.83,447.05
XS Rating Curve= 0 ,0
Exp/Cntr=0.3,0.1

Type RM Length L Ch R = 1 ,3108.897,91.94,91.14,88.47
XS GIS Cut Line= 3
     631463.3752    4314907.1738     631202.6941    4315324.3298
     631165.9842    4315409.9971
#Sta/Elev= 30
       0  711.09   64.16  701.88  103.88  698.93   116.1  696.15  125.27  695.16
  140.55  693.86  152.77  695.37   171.1  695.61  204.71  691.52  216.93  686.86
  229.15  684.89  284.15  684.04  296.37  683.11  333.03  684.22  391.08  683.46
  424.69  682.84  436.91  683.51  452.19  685.19  464.41  683.11  467.47  682.94
  479.69   684.2  506.94  681.77  509.95  682.93  512.95  683.08  521.97  688.53
     534  693.95  543.02  697.09  552.04     699  576.09  708.56  585.11   711.1
#Mann= 3 , 0 , 0
       0      .1       0  391.08      .1       0  436.91      .1       0
Bank Sta=391.08,436.91
XS Rating Curve= 0 ,0
Exp/Cntr=0.3,0.1

Type RM Length L Ch R = 1 ,3017.761,93.88,91.68,93.06
XS GIS Cut Line= 3
     631345.6353     4314904.528     631151.0552    4315237.2409
     631086.6899    4315403.4029
#Sta/Elev= 30
       0  711.13   30.59  705.35      52  704.61  107.06  699.65  168.24  696.22
   171.3  695.54  174.36  693.85   186.6  685.35  192.72  683.49  214.13  682.17
  247.78  682.97  281.43  682.85  351.78  681.22  364.02   681.8  372.72  683.03
  391.58  685.42  394.65  685.06  406.94  681.59  437.66  683.12  465.31  681.87
  468.39  682.72  474.53  686.24   477.6  687.41  480.67  687.47  489.89  690.79
  508.33  696.18  514.47  696.99  542.12  705.12  548.27  706.16  563.63  711.59
#Mann= 3 , 0 , 0
       0      .1       0  281.43      .1       0  372.72      .1       0
Bank Sta=281.43,372.72
XS Rating Curve= 0 ,0
Exp/Cntr=0.3,0.1

Type RM Length L Ch R = 1 ,2926.08 ,92.76,91.44,90.62
XS GIS Cut Line= 6
     631303.3019    4314899.2363     631091.1424    4315165.9062
     631083.3974    4315175.3723     631072.3388    4315191.5561
     631060.6972     4315210.077     631017.5514    4315409.8831
#Sta/Elev= 30
       0  710.29    9.21  708.71   24.56   707.6   49.12  703.92   89.03  700.28
  187.27  694.88  190.34  694.15  193.41  692.28  199.55  686.49  205.69  682.19
  211.83  680.54  297.79  680.95  303.93  680.21  331.56  679.96   355.8  683.13
   372.6  684.59  380.81  681.81  386.27  680.83  431.09  680.02  440.24  681.34
  464.65  682.82  495.16  687.03  504.31  691.92  507.36  692.76  531.77  695.02
  543.97  697.65  559.23  699.23  577.53  705.95  589.74  707.05  598.89  711.52
#Mann= 3 , 0 , 0
       0      .1       0  297.79      .1       0   355.8      .1       0
Bank Sta=297.79,355.8
XS Rating Curve= 0 ,0
Exp/Cntr=0.3,0.1

Type RM Length L Ch R = 1 ,2834.64 ,102,91.44,52.3
XS GIS Cut Line= 6
      631186.885    4314860.8716     631026.5158     4315101.882
     631012.2536    4315117.4159     631002.7489    4315130.3667
     630978.9363    4315171.0464     630954.0512    4315399.2998
#Sta/Elev= 30
       0  710.62   36.57  705.79   82.28  701.51  158.46  696.38  234.64  693.04
  240.73  691.17  243.78  691.13  246.83  689.95  252.92  686.59  262.06  680.56
  265.11  679.68   277.3  679.05  304.55  679.16  344.32  678.18  353.16   679.6
  373.78  680.19  428.88  679.77  480.93  680.55   499.3  680.15  508.48  684.55
  517.67  687.48  520.73  687.57  536.03  690.66  548.28  693.96  551.34  693.99
  563.59  697.65  575.83  700.34  588.08  701.02  591.14   702.1  603.39  708.67
#Mann= 3 , 0 , 0
       0      .1       0  262.06      .1       0  353.16      .1       0
Bank Sta=262.06,353.16
XS Rating Curve= 0 ,0
Exp/Cntr=0.3,0.1