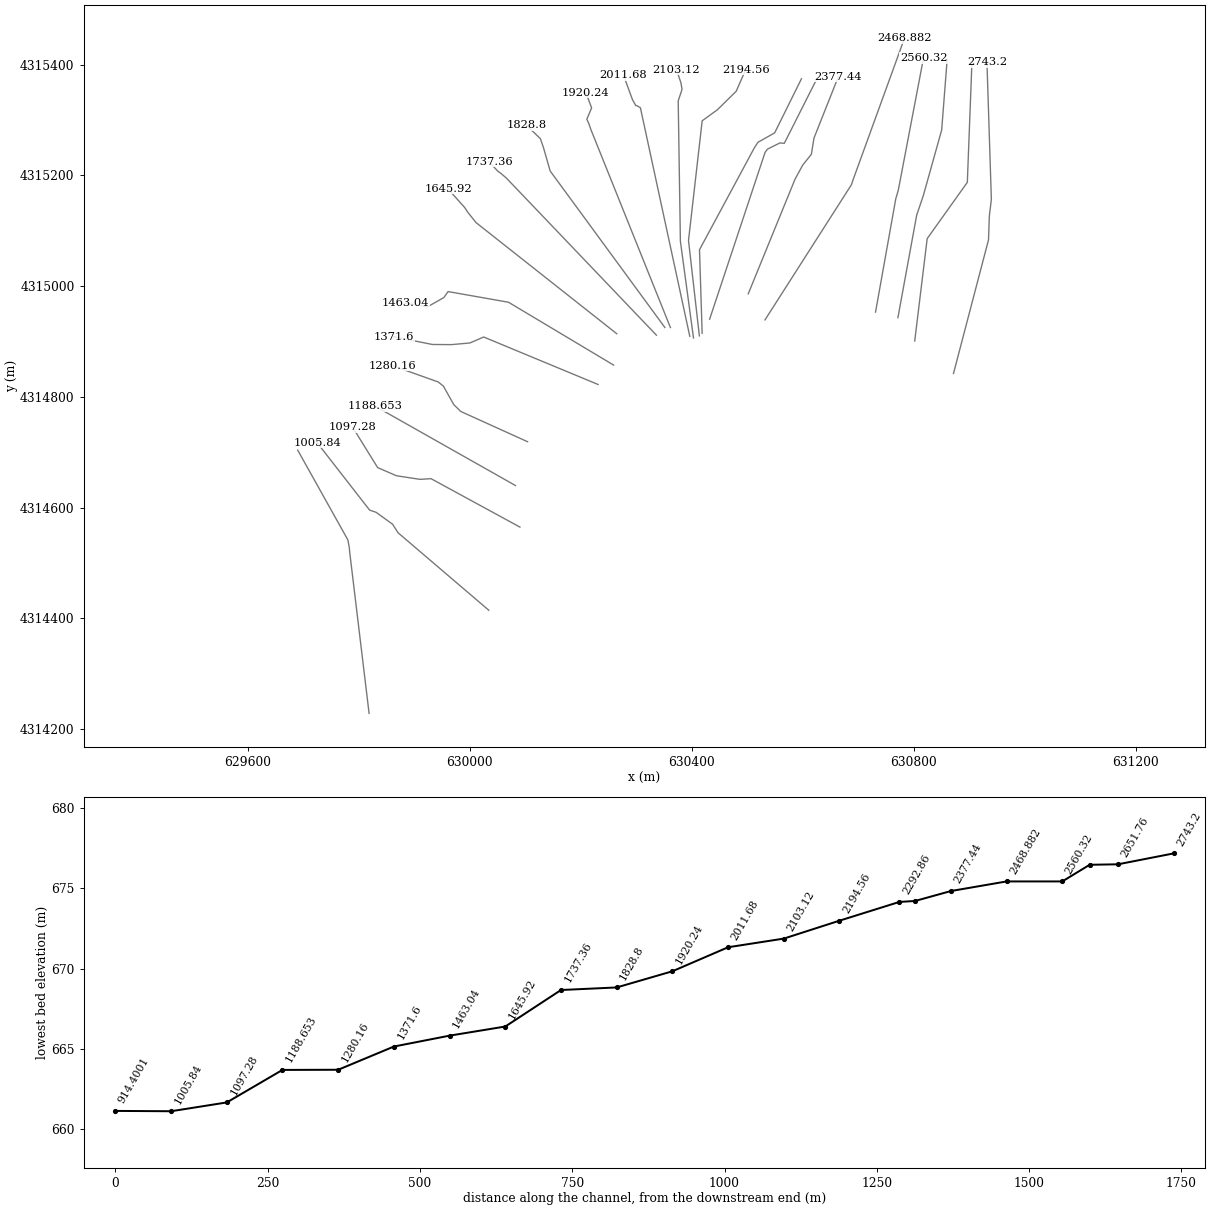
HEC-RAS study RedCreek.prj: RedCreek

--- RedCreek.g01 (geometry) --- (continued)

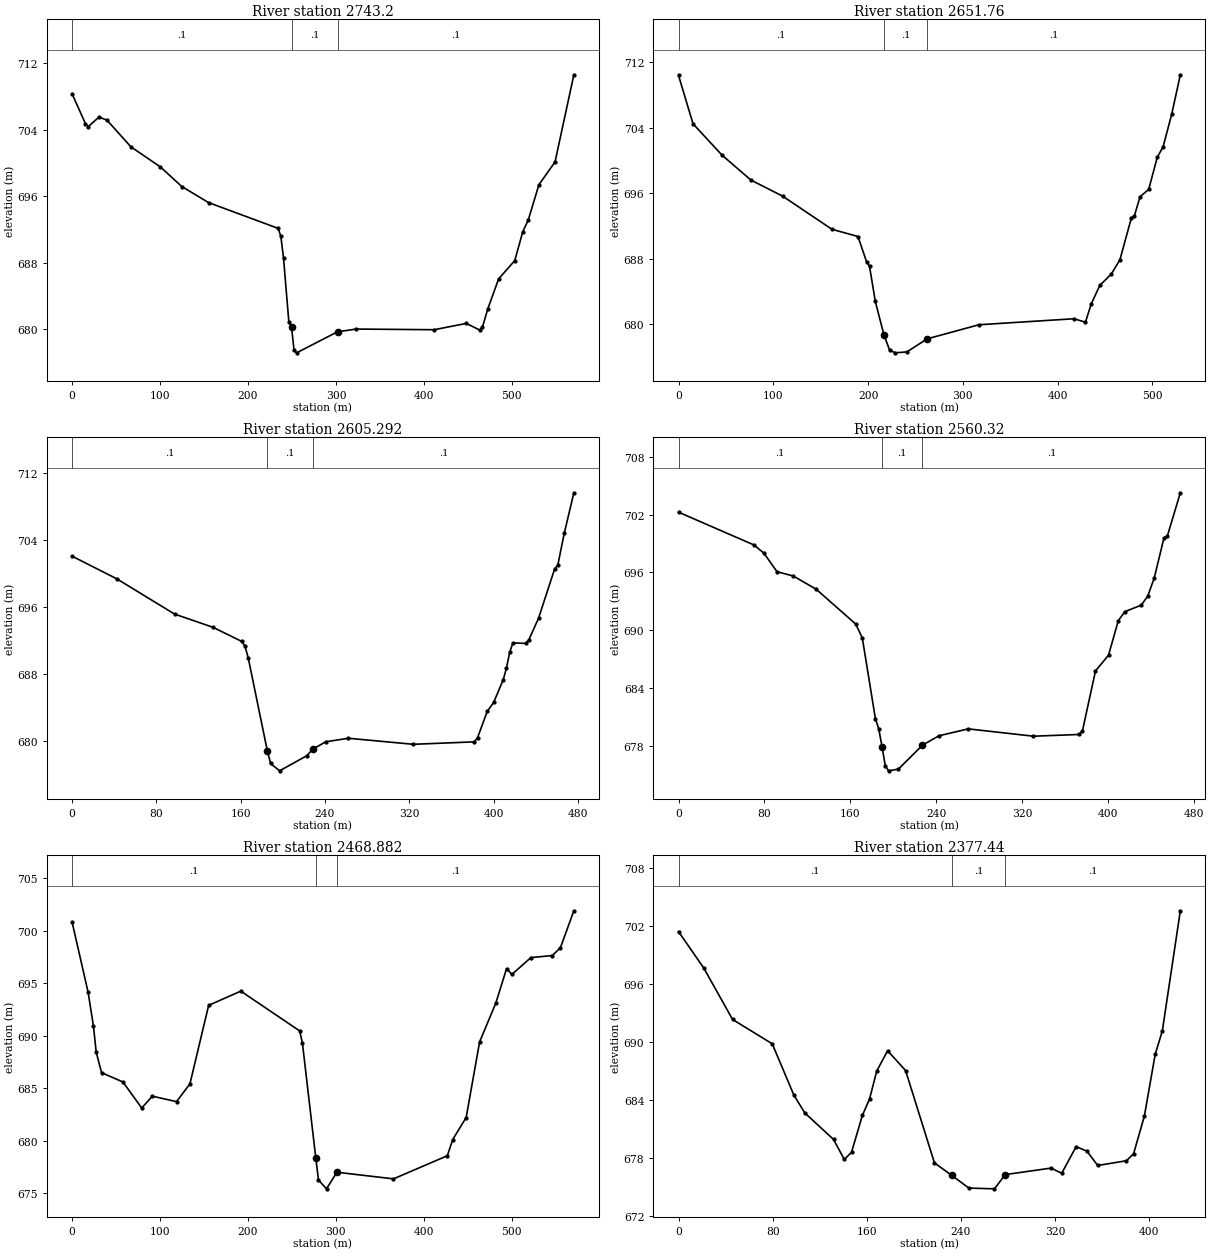
Type RM Length L Ch R = 1 ,2743.2  ,97.71,91.44,62.43
XS GIS Cut Line= 5
     630871.7921    4314842.0068     630934.9252    4315083.3802
     630936.4543    4315126.5001     630940.0866    4315156.6652
     630932.1172    4315403.9829
#Sta/Elev= 30
       0  708.35   15.21  704.75   18.26  704.38   30.43  705.53   39.55  705.19
   66.94  701.96  100.41  699.55  124.75  697.19  155.17  695.26  234.28  692.16
  237.32  691.22  240.37  688.61  246.45  680.89  249.49  680.29  252.37  677.49
  255.25  677.19  301.76  679.72  323.02  680.05  411.61  679.97  448.27  680.73
  463.55  679.92   466.6  680.31  472.71   682.5  484.93  686.08  503.26  688.28
  512.43  691.77  518.54  693.14  530.75  697.41  549.08  700.15  570.47  710.63
#Mann= 3 , 0 , 0
       0      .1       0  249.49      .1       0  301.76      .1       0
Bank Sta=249.49,301.76
XS Rating Curve= 0 ,0
Exp/Cntr=0.3,0.1

Type RM Length L Ch R = 1 ,2651.76 ,43.42,46.47,61.86
XS GIS Cut Line= 4
      630801.942    4314900.7444       630824.42     4315085.676
     630896.7583    4315187.3011     630905.1297    4315405.5704
#Sta/Elev= 30
       0  710.37   15.27  704.47   45.81  700.65   76.35   697.6  109.94  695.63
  161.86  691.59  189.34  690.71  198.46   687.6  201.51  687.08  207.59   682.8
  216.72   678.7   222.8  676.82  228.89  676.51  241.06  676.63  262.35  678.22
   317.1  679.94  417.22  680.67  429.35  680.25  435.42  682.47  444.52  684.74
  456.65  686.13  465.76  687.88  477.89  693.01  480.92  693.21  486.99  695.57
  496.09  696.46  505.19   700.4  511.26  701.65  520.36  705.63  529.46  710.45
#Mann= 3 , 0 , 0
       0      .1       0  216.72      .1       0  262.35      .1       0
Bank Sta=216.72,262.35
XS Rating Curve= 0 ,0
Exp/Cntr=0.3,0.1

Type RM Length L Ch R = 1 ,2605.292,43.46,44.97,48.56
XS GIS Cut Line= 5
     630771.6508    4314942.8873     630805.5175    4315128.2283
     630817.4238    4315163.2856     630850.4968    4315281.6869
     630860.4187    4315409.1833
#Sta/Elev= 30
       0  702.11   42.54   699.4   97.24   695.2  133.71  693.62  161.06  691.93
   164.1  691.37  167.14     690  185.37  678.84  188.41  677.36  196.95  676.48
  222.59  678.27  228.51  679.07   240.8  679.95  262.31  680.37  323.78  679.65
  381.86  679.94   384.9  680.46  394.04  683.58  400.13  684.64  409.26  687.38
  412.31  688.77  415.35  690.63   418.4  691.77  430.58  691.69  433.62  692.15
  442.76  694.71  457.98  700.58  461.02  701.04  467.11  704.83  476.25  709.68
#Mann= 3 , 0 , 0
       0      .1       0  185.37      .1       0  228.51      .1       0
Bank Sta=185.37,228.51
XS Rating Curve= 0 ,0
Exp/Cntr=0.3,0.1

Type RM Length L Ch R = 1 ,2560.32 ,97.25,91.44,78.83
XS GIS Cut Line= 4
     630731.3332    4314952.9843     630767.7798    4315157.4924
     630772.3559    4315173.1642      630817.817    4315411.9204
#Sta/Elev= 30
       0  702.25   70.26  698.85   79.43  698.01   91.65  696.08  106.92  695.63
   128.3  694.25  164.96  690.65  171.07  689.22  183.29  680.82  186.35  679.81
   189.4  677.96  192.46  675.97  195.51  675.44  204.68  675.62  227.09   678.1
  242.29  679.07  269.63  679.79  330.39  679.03  372.92  679.21  375.96  679.57
  388.11  685.79  400.26  687.43  409.38  691.01  415.45  691.94  430.65  692.61
  436.72  693.53   442.8  695.42  451.91   699.6  454.95  699.75   467.1  704.26
#Mann= 3 , 0 , 0
       0      .1       0   189.4      .1       0  227.09      .1       0
Bank Sta=189.4,227.09
XS Rating Curve= 0 ,0
Exp/Cntr=0.3,0.1

Type RM Length L Ch R = 1 ,2468.882,93.97,91.44,89.24
XS GIS Cut Line= 4
     630532.0664    4314938.8445     630687.7582    4315182.8011
     630690.5686    4315191.1436     630783.4211    4315447.3747
#Sta/Elev= 30
       0  700.84   18.28  694.14   24.37   690.9   27.42  688.47   33.51   686.5
   57.88  685.61   79.21  683.14   91.39  684.26  118.81  683.74  134.04  685.43
  155.36  692.91  191.92  694.26  258.94  690.47  261.99  689.32  277.22  678.37
  280.27  676.28   289.4  675.44  301.27  677.02  365.58  676.39  426.82  678.59
  432.94  680.13  448.25  682.23  463.57  689.44  481.94  693.11  494.19   696.4
  500.31  695.85  521.75  697.45  546.25  697.65  555.43  698.39  570.74  701.91
#Mann= 3 , 0 , 0
       0      .1       0  277.22      .1       0  301.27      .1       0
Bank Sta=277.22,301.27
XS Rating Curve= 0 ,0
Exp/Cntr=0.3,0.1

Type RM Length L Ch R = 1 ,2377.44 ,72.7,58.79,50.3
XS GIS Cut Line= 6
     630501.9039    4314985.9404     630586.2696    4315193.0552
     630600.1068     4315218.495     630615.6384    4315237.9021
     630620.4009     4315267.271     630664.2506    4315377.9969
#Sta/Elev= 30
       0  701.39   21.44  697.63   45.95  692.32   79.65  689.81   98.03  684.52
  107.22  682.69  131.73  679.94  140.92  677.87  147.05  678.62  156.24  682.41
  162.37  684.12  168.49     687  177.69   689.1     193  687.05  217.51  677.52
  232.33  676.22  246.81  674.92  268.57  674.84  277.68  676.31  316.59  676.98
  325.75  676.45  337.97   679.2  347.13  678.73  356.29  677.25  380.72  677.74
  386.83  678.47  395.99  682.36  405.15  688.71  411.26  691.16  426.53  703.54
#Mann= 3 , 0 , 0
       0      .1       0  232.33      .1       0  277.68      .1       0
Bank Sta=232.33,277.68
XS Rating Curve= 0 ,0
Exp/Cntr=0.3,0.1

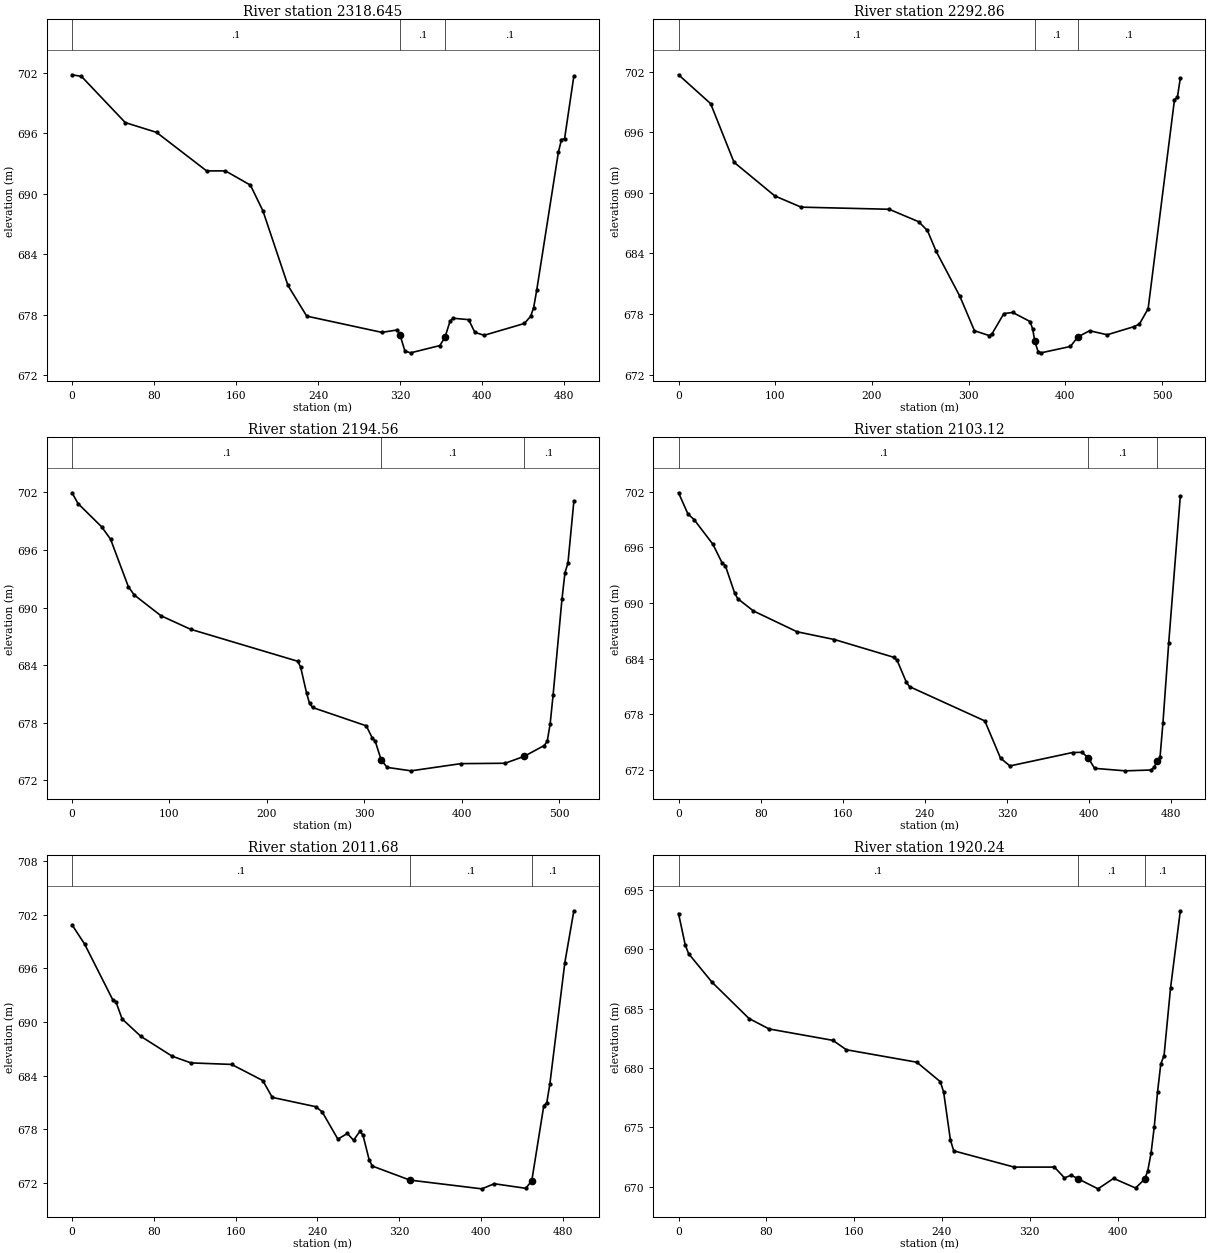
Type RM Length L Ch R = 1 ,2318.645,20.83,25.78,24.24
XS GIS Cut Line= 6
     630432.3183    4314940.1674     630532.1882    4315241.2758
     630536.4215    4315247.2025     630558.8582    4315258.4208
     630566.9016    4315257.7858     630625.6321    4315374.4337
#Sta/Elev= 30
       0  701.79    9.15  701.63   51.86  697.05   82.36  696.08  131.17  692.26
  149.47  692.26  173.87  690.85  186.07   688.3  210.48   680.9  228.78  677.86
  301.99  676.25  317.24  676.49  319.67  676.01  324.52   674.4  330.06  674.22
  358.55  674.94  363.55  675.76  368.56  677.37  371.58  677.65  386.66  677.51
  392.69  676.25  401.74  675.96  440.96  677.13  446.99  677.83  450.01  678.69
  453.03  680.44  474.14  694.11  477.16  695.37  480.18  695.45  489.23  701.67
#Mann= 3 , 0 , 0
       0      .1       0  319.67      .1       0  363.55      .1       0
Bank Sta=319.67,363.55
XS Rating Curve= 0 ,0
Exp/Cntr=0.3,0.1

Type RM Length L Ch R = 1 ,2292.86 ,103.11,98.3,103.69
XS GIS Cut Line= 6
     630418.8245    4314914.7674      630414.062    4315065.5802
      630513.371    4315250.4665     630519.4812    4315259.6218
      630549.514    4315276.6418     630597.7854     4315374.299
#Sta/Elev= 30
       0   701.7    33.2  698.84   57.34  693.04   99.59   689.7  126.75  688.59
   217.8  688.38  248.22  687.15  257.34  686.28  266.47   684.2   290.8  679.78
  306.01  676.35  321.22  675.87  324.26  676.06  336.42  678.05  345.55  678.16
  363.51  677.26  366.26   676.5  368.34  675.32  371.76  674.29  374.78  674.16
  405.23  674.79  412.97  675.74  425.07  676.35  443.23  675.95  470.46  676.74
  476.51     677  485.59  678.53  512.83  699.23  515.85  699.47  518.88  701.37
#Mann= 3 , 0 , 0
       0      .1       0  368.34      .1       0  412.97      .1       0
Bank Sta=368.34,412.97
XS Rating Curve= 0 ,0
Exp/Cntr=0.3,0.1

Type RM Length L Ch R = 1 ,2194.56 ,73.6,91.44,103.07
XS GIS Cut Line= 6
     630413.7974    4314910.0049     630394.2301    4315082.2544
     630418.8674    4315298.4125      630446.299    4315318.3914
     630480.2509    4315351.8584     630497.2871    4315390.8544
#Sta/Elev= 30
       0  701.96    6.08  700.84   30.41  698.41   39.54  697.12   57.79  692.17
   63.87  691.31   91.24  689.15  121.65  687.74  231.58  684.41  234.64  683.81
  240.77  681.09  243.83  680.01   246.9  679.59  302.05  677.68  308.18  676.42
  311.25  676.08  317.37  674.12   323.5  673.35  348.02  672.99  399.13  673.74
  444.55  673.78   464.2   674.5  484.79  675.63  487.83  676.06  490.87  677.89
  493.91  680.93  503.03  690.92  506.07  693.65  509.11  694.62  515.19  701.08
#Mann= 3 , 0 , 0
       0      .1       0  317.37      .1       0   464.2      .1       0
Bank Sta=317.37,464.2
XS Rating Curve= 0 ,0
Exp/Cntr=0.3,0.1

Type RM Length L Ch R = 1 ,2103.12 ,83.53,91.44,94.45
XS GIS Cut Line= 6
     630403.2141    4314906.3007     630379.5993    4315080.9506
     630375.6807    4315334.4819     630382.5555    4315355.2072
     630380.6469    4315366.8829     630372.5362    4315390.9941
#Sta/Elev= 30
       0   701.9    9.12  699.62   15.19     699   33.42  696.35   42.54  694.31
   45.58  694.04   54.69  691.06   57.73  690.46   72.93  689.14  115.47  686.89
  151.93  686.05  209.84  684.13   212.9  683.82  222.06  681.42  225.12  680.96
  298.44  677.26  313.71  673.24  322.88   672.4  383.98  673.85  393.14  673.87
  399.25  673.26  405.36  672.14  435.26  671.87  460.51  671.96  463.47  672.27
  466.29  672.97  469.12  673.32  471.95  677.01   477.6   685.7  488.91  701.56
#Mann= 3 , 0 , 0
       0      .1       0  399.25      .1       0  466.29      .1       0
Bank Sta=399.25,466.29
XS Rating Curve= 0 ,0
Exp/Cntr=0.3,0.1

Type RM Length L Ch R = 1 ,2011.68 ,101.1,91.44,89.77
XS GIS Cut Line= 6
     630396.5554    4314909.1891     630307.5327    4315322.0354
     630301.0769    4315325.8454     630299.1684     4315325.938
     630293.2569    4315336.6205     630277.0432    4315380.8117
#Sta/Elev= 30
       0  700.88   12.24  698.74   39.79   692.5   42.85  692.29   48.97  690.35
   67.33   688.4   97.93  686.18   116.3  685.43  156.08  685.26  186.68  683.45
  195.87  681.57  238.71  680.52  244.83  679.93  260.13  676.89  269.32  677.53
  275.44  676.77  281.56  677.76  284.62  677.36  290.74  674.57   293.8  673.88
  330.52  672.31  400.91  671.33  413.15   671.9  443.95  671.39  449.84  672.23
   461.6  680.64  464.55  680.99  467.49  683.03   482.2  696.66  491.02  702.46
#Mann= 3 , 0 , 0
       0      .1       0  330.52      .1       0  449.84      .1       0
Bank Sta=330.52,449.84
XS Rating Curve= 0 ,0
Exp/Cntr=0.3,0.1

Type RM Length L Ch R = 1 ,1920.24 ,96.23,91.44,113.59
XS GIS Cut Line= 6
     630361.6303    4314925.0641     630218.2943    4315282.6476
     630214.7114    4315293.1158     630210.9927    4315301.2259
     630219.5917    4315321.7311     630209.2289    4315349.5332
#Sta/Elev= 30
       0  693.01    6.11  690.36    9.17  689.63   30.57  687.22   64.21  684.17
   82.55  683.29  140.64  682.33  152.87  681.54  217.08  680.49  238.48  678.85
  241.54  677.96  247.66  673.95  250.71  673.03  305.75  671.66  342.44  671.66
  351.61  670.75  357.72  670.98  363.84  670.68  382.18  669.83  396.31  670.71
  416.35   669.9  424.68  670.65  427.46  671.34  430.43  672.81   433.4  675.06
  436.36  677.97  439.33  680.34   442.3  681.05  448.23  686.75  457.13  693.24
#Mann= 3 , 0 , 0
       0      .1       0  363.84      .1       0  424.68      .1       0
Bank Sta=363.84,424.68
XS Rating Curve= 0 ,0
Exp/Cntr=0.3,0.1

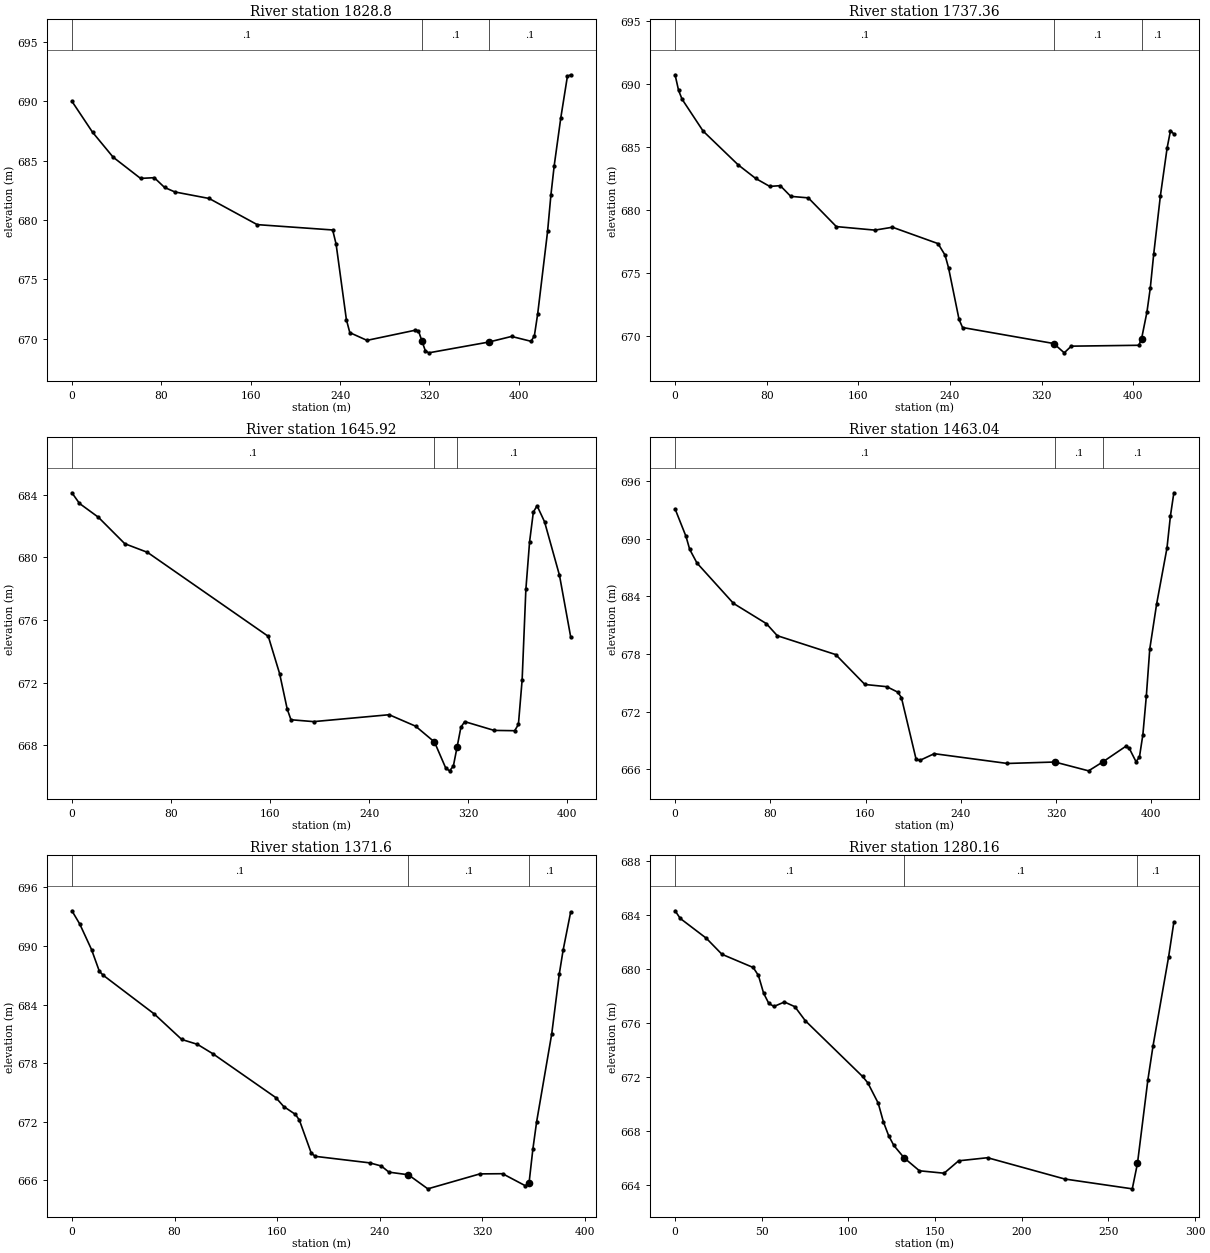
Type RM Length L Ch R = 1 ,1828.8  ,85.46,91.44,96.27
XS GIS Cut Line= 5
     630351.6071    4314925.1819     630144.9377     4315207.749
     630132.9884    4315249.5105     630127.3324    4315266.0355
     630101.9189    4315290.7644
#Sta/Elev= 30
       0  689.99   18.43  687.39   36.85  685.29   61.42   683.5    73.7  683.56
   82.91  682.74   92.13  682.36  122.84  681.81  165.83  679.61  233.39  679.16
  236.46  677.97  245.67  671.61  248.74  670.52   264.1  669.87  307.09  670.72
  310.16  670.67  313.23  669.83   316.3     669  319.37  668.82  373.25  669.73
  393.52   670.2  410.98  669.79  413.94  670.26  416.89   672.1  425.76  679.05
  428.71  682.09  431.67  684.57  437.58   688.6  443.49  692.09  446.44  692.22
#Mann= 3 , 0 , 0
       0      .1       0  313.23      .1       0  373.25      .1       0
Bank Sta=313.23,373.25
XS Rating Curve= 0 ,0
Exp/Cntr=0.3,0.1

Type RM Length L Ch R = 1 ,1737.36 ,93.58,91.44,89.84
XS GIS Cut Line= 5
     630336.3799    4314911.2936     630066.0889    4315194.8817
     630056.1598    4315203.4183     630050.4311    4315207.5753
     630034.4765    4315224.8176
#Sta/Elev= 30
       0  690.73    3.06  689.49    6.12  688.79   24.49  686.26   55.09  683.58
    70.4   682.5   82.64  681.87   91.82  681.93     101  681.08  116.31  680.96
  140.79  678.68  174.46   678.4  189.76  678.63  229.55  677.33  235.67  676.42
  238.73  675.41  247.91  671.31  250.97  670.67  330.55   669.4  339.73  668.66
  345.85  669.19  404.86  669.26  407.22  669.77  411.94   671.9  414.87  673.82
  417.81  676.47  423.68  681.13  429.56  684.93  432.49   686.3  435.43  686.03
#Mann= 3 , 0 , 0
       0      .1       0  330.55      .1       0  407.22      .1       0
Bank Sta=330.55,407.22
XS Rating Curve= 0 ,0
Exp/Cntr=0.3,0.1

Type RM Length L Ch R = 1 ,1645.92 ,93.08,91.44,95.47
XS GIS Cut Line= 5
     630264.9128    4314913.8878     630011.3543    4315114.5333
     629996.6686    4315132.9663     629990.7788    4315141.9102
     629960.6138    4315175.6515
#Sta/Elev= 30
       0  684.12     6.1  683.44   21.35  682.56   42.71  680.87   61.01  680.32
  158.62  674.96  167.77  672.58  173.87  670.33  176.92  669.64  195.23  669.52
  256.23  669.96  277.59  669.23  292.84  668.22  301.99  666.55  305.04  666.38
  308.09  666.68  311.14  667.91  314.19  669.16  317.24  669.52  341.02  668.96
  357.62  668.94  360.64  669.34  363.65  672.18  366.67  677.96  369.69  681.01
  372.71  682.89  375.72  683.29  381.76  682.27  393.83  678.85  402.88  674.92
#Mann= 3 , 0 , 0
       0      .1       0  292.84      .1       0  311.14      .1       0
Bank Sta=292.84,311.14
XS Rating Curve= 0 ,0
Exp/Cntr=0.3,0.1

Type RM Length L Ch R = 1 ,1463.04 ,104.27,91.44,76.53
XS GIS Cut Line= 6
     630259.2402    4314857.2628     630069.8055    4314970.7514
     629960.9291    4314990.0026     629953.4187    4314979.3109
     629923.8874    4314962.4859     629883.9352    4314969.1005
#Sta/Elev= 30
       0  693.14     9.2  690.26   12.27  688.92    18.4  687.49   49.07  683.28
   76.68  681.17   85.88  679.91  134.95  677.94  159.49  674.82  177.89  674.59
  187.09  674.02  190.16  673.46  202.43  667.06  205.49  666.89  217.76   667.6
  279.18  666.58  319.11  666.73  347.42  665.81  359.27  666.73  378.59  668.36
  381.49  668.19  387.27  666.77  390.16  667.24  393.06  669.59  395.95  673.59
  398.84  678.52  404.63  683.23   413.3  689.05   416.2   692.4  419.09  694.82
#Mann= 3 , 0 , 0
       0      .1       0  319.11      .1       0  359.27      .1       0
Bank Sta=319.11,359.27
XS Rating Curve= 0 ,0
Exp/Cntr=0.3,0.1

Type RM Length L Ch R = 1 ,1371.6  ,145.09,91.44,66.95
XS GIS Cut Line= 6
     630231.2324    4314822.2226     630025.0687    4314907.9618
     630000.3569    4314897.2171     629967.1132    4314894.1988
     629932.5966     4314894.468     629863.1433    4314908.3587
#Sta/Elev= 30
       0  693.61    6.12  692.25   15.29  689.64   21.41  687.41   24.47     687
   64.23  683.04   85.64  680.43   97.88  679.93  110.11  678.95  159.05  674.47
  165.17  673.56  174.34  672.75   177.4  672.16  186.58  668.81  189.64  668.46
  232.26  667.79  241.25  667.47  247.23  666.84  262.37  666.57  277.54  665.13
  318.13  666.66  335.83  666.68  353.54  665.45  356.49  665.74  359.44  669.18
  362.39     672   374.2  681.03   380.1  687.17  383.05  689.58  388.96   693.5
#Mann= 3 , 0 , 0
       0      .1       0  262.37      .1       0  356.49      .1       0
Bank Sta=262.37,356.49
XS Rating Curve= 0 ,0
Exp/Cntr=0.3,0.1

Type RM Length L Ch R = 1 ,1280.16 ,76.06,91.51,95.07
XS GIS Cut Line= 6
     630104.1597    4314718.8521     629983.7703    4314773.5001
     629971.2594    4314785.7645     629952.3923    4314819.3603
     629943.0905    4314826.7476     629861.0977    4314856.0594
#Sta/Elev= 30
       0  684.32       3  683.75   18.03  682.28   27.04  681.09   45.07  680.11
   48.08  679.52   51.08   678.2   54.09  677.44   57.09  677.22    63.1  677.55
   69.11   677.2   75.12  676.16  108.17  672.02  111.18  671.55  117.19  670.04
  120.19  668.65   123.2  667.63   126.2   666.9  132.21  665.97  140.97  665.02
  155.21  664.84  163.58  665.76  180.27  665.99  224.78  664.41  263.76  663.68
  266.76  665.57  272.76  671.77  275.76  674.31  284.75  680.92  287.75  683.48
#Mann= 3 , 0 , 0
       0      .1       0  132.21      .1       0  266.76      .1       0
Bank Sta=132.21,266.76
XS Rating Curve= 0 ,0
Exp/Cntr=0.3,0.1

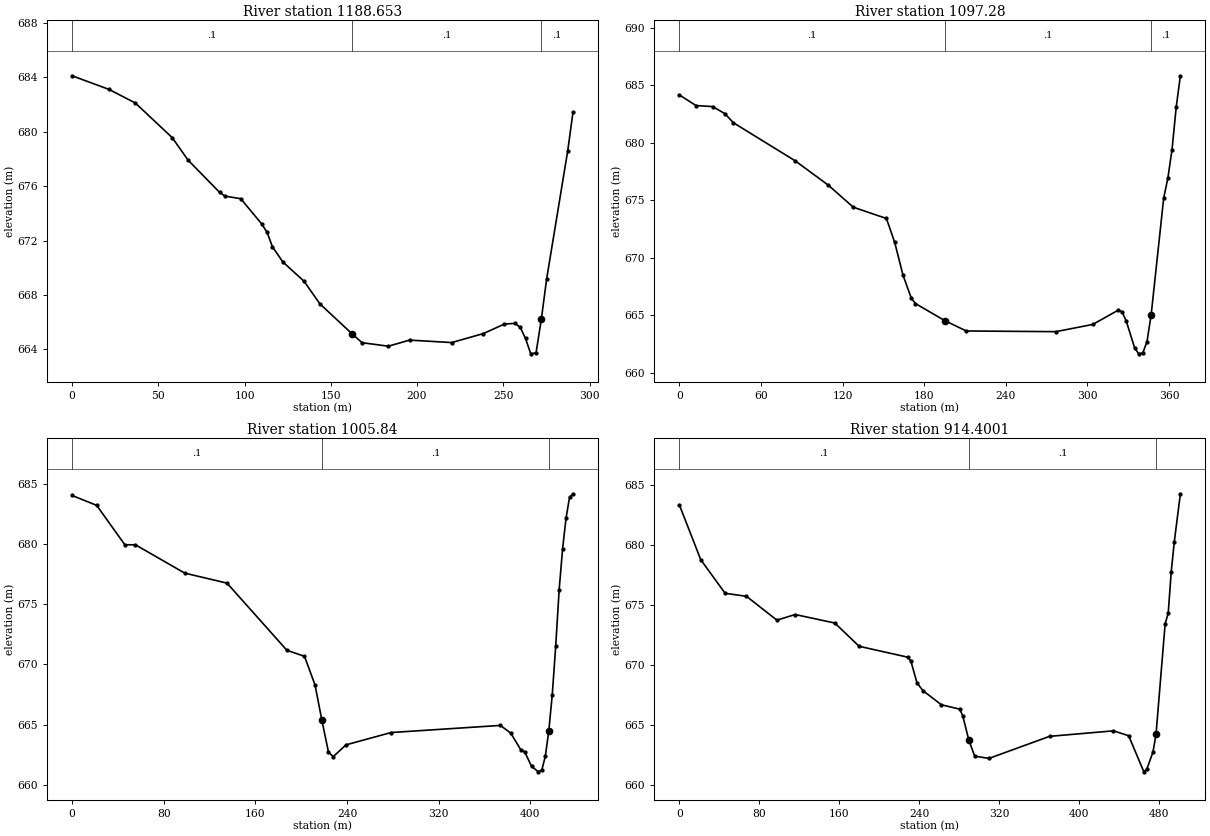
Type RM Length L Ch R = 1 ,1188.653,79.42,91.37,95.08
XS GIS Cut Line= 2
     630082.3999    4314639.6892     629829.7554    4314782.8412
#Sta/Elev= 30
       0  684.12    21.4  683.12   36.68  682.12   58.08  679.57   67.25  677.92
   85.59  675.54   88.64  675.27   97.81  675.08  110.04  673.21   113.1   672.6
  116.15  671.55  122.27  670.42  134.49  669.01  143.66  667.35  162.18  665.16
  168.12  664.49   183.4  664.23  195.63  664.68  220.08   664.5  238.42  665.16
  250.65  665.86  256.76  665.91  259.82  665.62  262.87   664.8  265.93  663.67
  268.99  663.75  272.04  666.21   275.1  669.16  287.33  678.59  290.38  681.43
#Mann= 3 , 0 , 0
       0      .1       0  162.18      .1       0  272.04      .1       0
Bank Sta=162.18,272.04
XS Rating Curve= 0 ,0
Exp/Cntr=0.3,0.1

Type RM Length L Ch R = 1 ,1097.28 ,127.67,91.44,75.79
XS GIS Cut Line= 6
     630090.4297     4314564.657     629930.1292    4314652.1434
      629910.523    4314650.8705      629867.842    4314657.3742
     629834.0008    4314672.1061     629788.8375    4314745.1103
#Sta/Elev= 30
       0  684.17   12.17  683.25   24.35  683.16   33.48  682.54   39.57  681.76
   85.22  678.43  109.57  676.31  127.83   674.4  152.18  673.42  158.27  671.34
  164.36  668.49  170.45  666.49  173.49  666.02  194.94  664.54   210.9  663.63
  276.74  663.57  303.91   664.2   322.3  665.42  325.37   665.3  328.43  664.52
  334.57  662.19  337.63  661.64   340.7  661.72  343.76  662.71  346.83  665.05
  356.03   675.2  359.09  676.93  362.16  679.42  365.22   683.1  368.29  685.84
#Mann= 3 , 0 , 0
       0      .1       0  194.94      .1       0  346.83      .1       0
Bank Sta=194.94,346.83
XS Rating Curve= 0 ,0
Exp/Cntr=0.3,0.1

Type RM Length L Ch R = 1 ,1005.84 ,101.85,91.44,66.53
XS GIS Cut Line= 6
     630034.3463     4314414.464     629870.8108    4314554.3433
     629860.9205    4314569.8634     629831.1232     4314591.385
     629819.4815    4314595.3538     629725.1378    4314716.8086
#Sta/Elev= 30
       0  684.01   21.52  683.19   46.11  679.92   55.34  679.92   98.38  677.57
  135.27  676.74  187.53  671.17   202.9  670.67  212.12  668.29  218.08  665.36
  223.85  662.72  227.98  662.35  239.15  663.33  278.51  664.35   373.9  664.94
  382.94   664.3  391.99  662.87  395.01  662.77  401.04  661.55  407.07  661.09
  410.08  661.25   413.1  662.39  416.11  664.48  419.13  667.46  422.14  671.49
  425.16  676.18  428.18   679.6  431.19  682.14  434.21  683.85  437.22  684.15
#Mann= 3 , 0 , 0
       0      .1       0  218.08      .1       0  416.11      .1       0
Bank Sta=218.08,416.11
XS Rating Curve= 0 ,0
Exp/Cntr=0.3,0.1

Type RM Length L Ch R = 1 ,914.4001,68.95,67.67,67.64
XS GIS Cut Line= 5
     629818.5523    4314228.2149     629783.6831    4314518.7524
     629782.9641    4314527.0933     629780.3576    4314541.4474
     629689.9154    4314703.5951
#Sta/Elev= 30
       0  683.36   21.34   678.8   45.72     676   67.06  675.75   97.54  673.76
  115.83  674.23  155.46  673.52  179.84  671.58  228.61  670.67  231.66  670.33
  237.76  668.51  243.85  667.87  262.14   666.7  280.43  666.34  283.48  665.79
  289.57  663.76  295.41  662.42  309.75  662.23  370.37  664.07  434.29  664.53
  449.51  664.12  464.72  661.11  467.77  661.35  473.86  662.77   476.9  664.25
  486.03  673.47  489.07  674.33  492.12  677.81  495.16  680.29  501.25   684.3
#Mann= 3 , 0 , 0
       0      .1       0  289.57      .1       0   476.9      .1       0
Bank Sta=289.57,476.9
XS Rating Curve= 0 ,0
Exp/Cntr=0.3,0.1