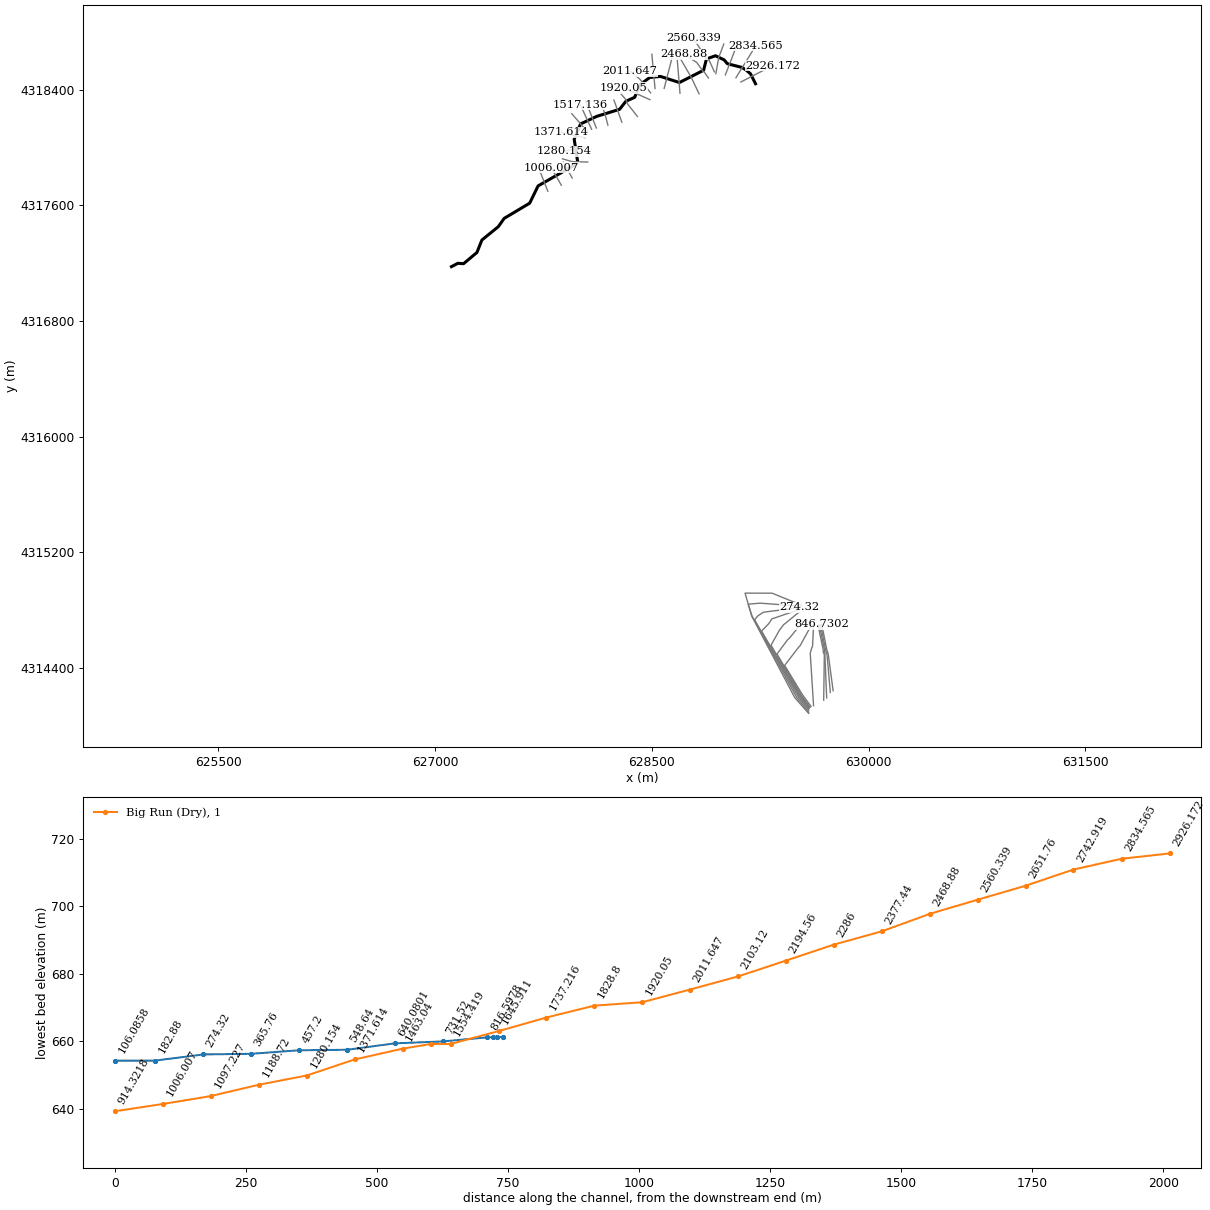
HEC-RAS study RedCreek.prj: RedCreek

--- RedCreek.g01 (geometry) --- (continued)

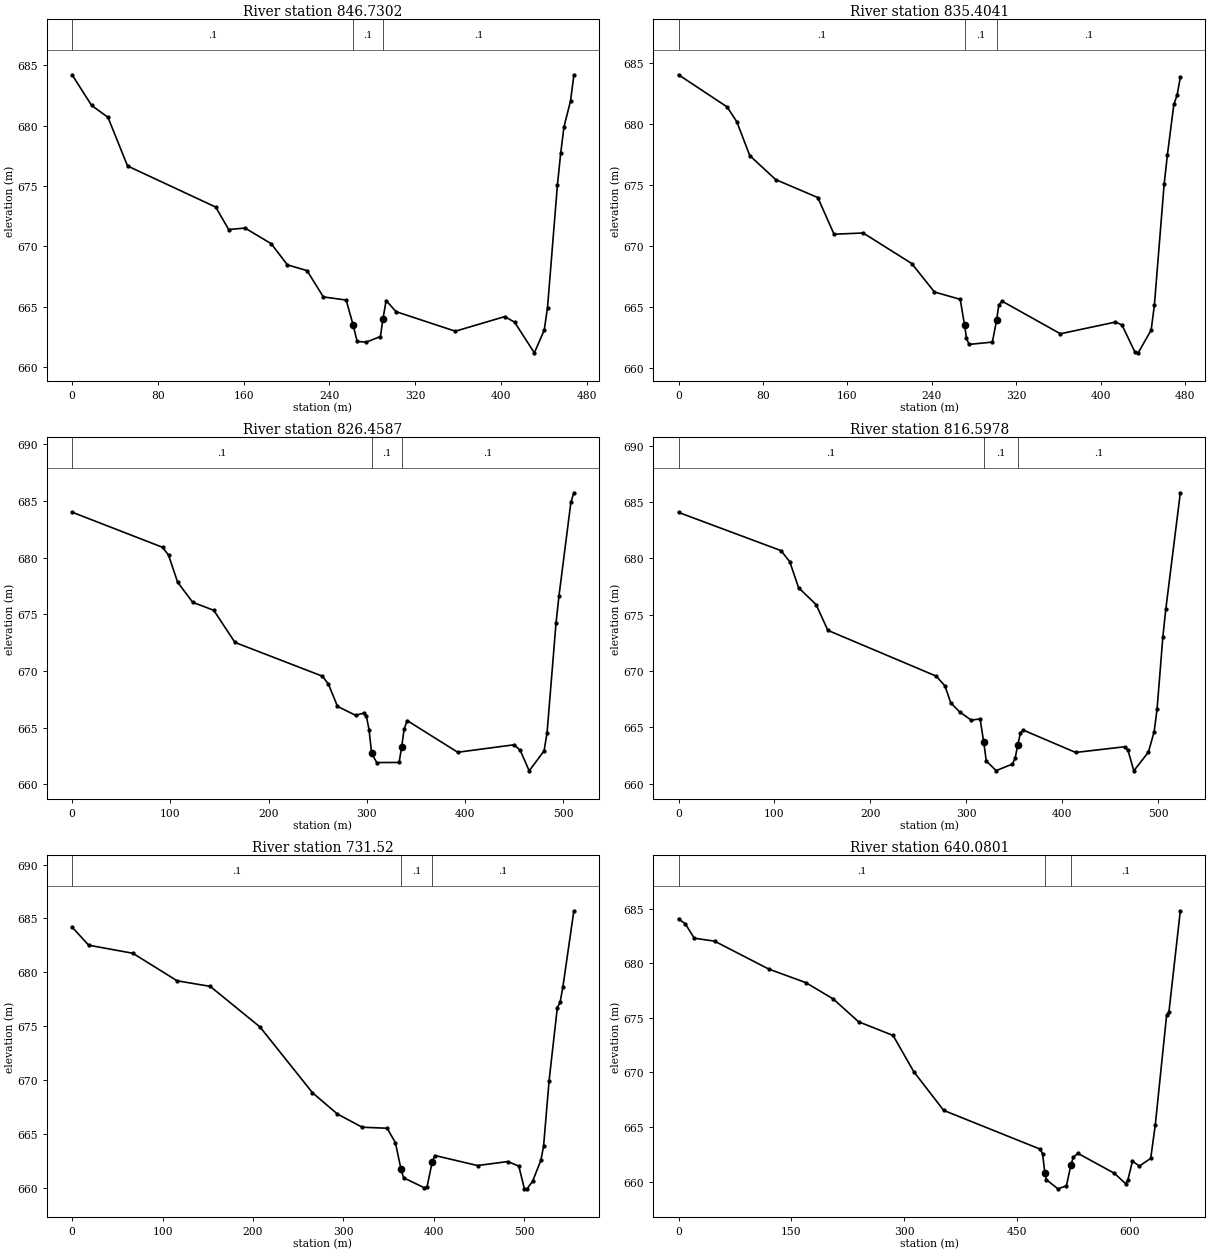
Type RM Length L Ch R = 1 ,846.7302,9.08,11.33,9.74
XS GIS Cut Line= 6
     629755.0748     4314240.735     629721.0666    4314494.1615
     629717.4683    4314503.6865     629716.1665    4314513.7248
     629712.1978    4314519.2811     629676.1825    4314700.6003
#Sta/Elev= 30
       0  684.21   18.26  681.67   33.48  680.69   51.75  676.66  133.94  673.26
  146.11   671.4  161.33  671.52  185.69  670.23  200.91  668.47  219.17     668
  234.39  665.82   255.7  665.56  262.13  663.51  265.91  662.14  274.24  662.07
  287.66  662.54  289.92  663.97  292.99  665.52   302.2   664.6   357.5  662.98
  403.57  664.19  412.79  663.73  431.22  661.19  440.44  663.07  443.51  664.94
  452.72  675.07   455.8  677.71  458.87   679.9  465.01  682.06  468.08  684.18
#Mann= 3 , 0 , 0
       0      .1       0  262.13      .1       0  289.92      .1       0
Bank Sta=262.13,289.92
XS Rating Curve= 0 ,0
Exp/Cntr=0.3,0.1

Type RM Length L Ch R = 1 ,835.4041,17.06,8.95,7.14
XS GIS Cut Line= 6
     629735.6313    4314229.2849     629712.6829    4314492.1172
     629705.5391    4314513.0193     629701.3058    4314521.2214
     629701.8349    4314529.1589     629667.6819    4314697.6358
#Sta/Elev= 30
       0  684.02   46.02  681.39   55.22  680.17   67.49   677.4   92.03  675.44
  131.92  673.97  147.26  670.97  174.87  671.07  220.88  668.57  242.36  666.24
   266.8  665.64  270.85  663.54  272.73  662.46  275.16  661.95  297.25  662.14
  301.22  663.92  303.34  665.18  306.41  665.49  361.67  662.82  413.85  663.78
  419.99  663.54  432.27  661.32  435.34  661.26  447.62  663.12  450.69  665.17
   459.9  675.04  462.97  677.44  469.11  681.59  472.18  682.35  475.25  683.81
#Mann= 3 , 0 , 0
       0      .1       0  270.85      .1       0  301.22      .1       0
Bank Sta=270.85,301.22
XS Rating Curve= 0 ,0
Exp/Cntr=0.3,0.1

Type RM Length L Ch R = 1 ,826.4587,4.71,9.86,9.24
XS GIS Cut Line= 6
     629710.5404    4314191.4007     629698.0761    4314485.8412
     629699.7694    4314493.2496     629696.5944    4314508.4896
     629694.4777    4314528.3863     629659.3642    4314697.5515
#Sta/Elev= 30
       0  684.01    92.1  680.91   98.23  680.21  107.44  677.83  122.79  676.06
  144.28  675.35  165.77  672.52   254.8  669.54  260.94  668.84  270.15  666.88
  288.56  666.09  297.09  666.29  299.48  666.05   302.3  664.81   304.9  662.72
  310.09  661.92  332.88  661.93  335.42  663.28  337.97  664.85     341  665.63
  392.52  662.83  450.12  663.49  456.18  662.99  465.27  661.19  480.43  662.95
  483.46  664.54  492.55  674.19  495.58  676.62  507.71  684.88  510.74  685.72
#Mann= 3 , 0 , 0
       0      .1       0   304.9      .1       0  335.42      .1       0
Bank Sta=304.9,335.42
XS Rating Curve= 0 ,0
Exp/Cntr=0.3,0.1

Type RM Length L Ch R = 1 ,816.5978,104.65,85.08,78.7
XS GIS Cut Line= 6
     629689.7487     4314175.634     629694.0676    4314490.0644
     629686.7342    4314507.8546     629686.7342    4314517.3796
     629685.1467    4314530.4765     629650.4811    4314693.5927
#Sta/Elev= 30
       0  684.07  106.86  680.68  116.01  679.69  125.17  677.39  143.49  675.89
   155.7  673.61  268.67  669.55  277.82  668.68  283.93  667.17  293.09  666.38
   305.3  665.64  314.46  665.76   318.3  663.67  320.87  662.03  331.15  661.17
  348.15  661.75  350.93  662.25  353.71  663.43  356.49  664.51  359.53  664.76
   414.1  662.78  465.65  663.29  468.68  662.98  474.74  661.15   489.9   662.8
  495.97  664.62     499  666.63  505.06  673.05  508.09  675.48  523.25  685.81
#Mann= 3 , 0 , 0
       0      .1       0   318.3      .1       0  353.71      .1       0
Bank Sta=318.3,353.71
XS Rating Curve= 0 ,0
Exp/Cntr=0.3,0.1

Type RM Length L Ch R = 1 ,731.52  ,99.18,91.44,81.05
XS GIS Cut Line= 5
     629619.5828    4314137.4729     629596.6336    4314500.3046
     629606.7506    4314536.4924     629612.6816    4314548.7491
     629619.4282    4314688.5737
#Sta/Elev= 30
       0   684.2   18.33  682.52   67.21  681.77  116.09  679.22  152.75   678.7
  207.75  674.94  265.79  668.84  293.29  666.87  320.79  665.64  348.28  665.55
  357.45  664.21  363.56  661.78  366.45  660.96  389.57  660.02  392.46  660.13
  398.24  662.46  401.13  663.02  448.22  662.09   481.7  662.46  493.87  662.04
  499.96  659.96     503  659.93  509.09  660.63  518.22  662.56  521.26  663.88
  527.35  669.96  536.48  676.74  539.52  677.22  542.56  678.62  554.74  685.71
#Mann= 3 , 0 , 0
       0      .1       0  363.56      .1       0  398.24      .1       0
Bank Sta=363.56,398.24
XS Rating Curve= 0 ,0
Exp/Cntr=0.3,0.1

Type RM Length L Ch R = 1 ,640.0801,91.92,91.44,88.46
XS GIS Cut Line= 6
     629602.1203    4314132.7104     629543.3827    4314212.0855
     629419.6002    4314416.1019     629510.8187    4314534.9784
     629527.5761     4314554.428     629601.7993    4314689.9484
#Sta/Elev= 30
       0  684.06    8.98  683.61   20.95  682.29   47.88  682.02  120.16  679.46
  169.11  678.23  205.82  676.73  239.48  674.64  285.37  673.39   312.9  670.07
  352.67  666.53   481.1  662.98  484.16  662.56  487.22  660.83  489.03   660.2
  504.64  659.35  515.95  659.63  522.01  661.57  525.04  662.23   531.1   662.6
  579.58  660.78  594.73  659.82  597.76  660.19  603.82  661.89   612.9  661.43
  628.05  662.14  634.11  665.19  649.26  675.28  652.29  675.55  667.44   684.8
#Mann= 3 , 0 , 0
       0      .1       0  487.22      .1       0  522.01      .1       0
Bank Sta=487.22,522.01
XS Rating Curve= 0 ,0
Exp/Cntr=0.3,0.1

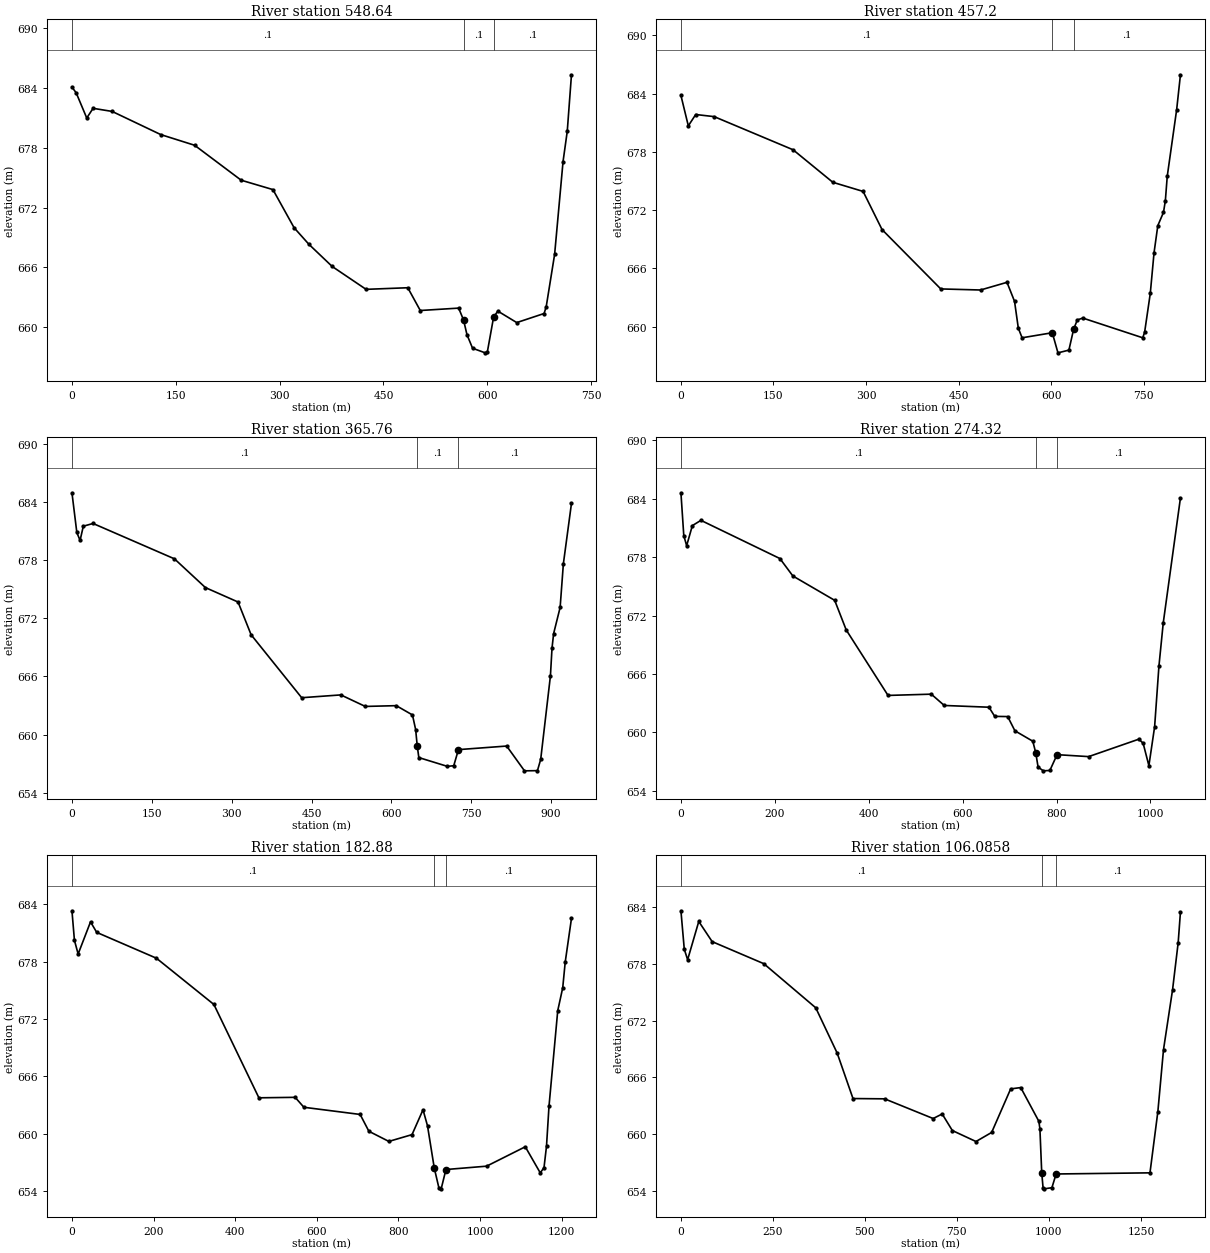
Type RM Length L Ch R = 1 ,548.64  ,92.04,91.44,92.11
XS GIS Cut Line= 6
      629595.347    4314126.3604     629536.0802    4314207.8522
     629366.5784    4314494.7857     629438.2004    4314591.3793
     629455.7772    4314608.1839       629545.59    4314719.2813
#Sta/Elev= 30
       0  684.07    6.11  683.49   21.37  680.97   30.53  681.94   58.02  681.63
  128.28  679.31   177.2  678.24  244.46  674.74  290.32   673.8   320.9  669.98
   342.3  668.32  375.93   666.1  424.85  663.81  485.13  663.97  503.17  661.69
  558.62  661.93   565.7  660.74  570.62  659.27  578.71  657.91  596.95  657.45
  599.99  657.51  609.11  661.03  615.19  661.63  642.55  660.48  682.06  661.39
   685.1  662.07  697.26  667.32  709.42  676.61   715.5  679.64  721.58   685.3
#Mann= 3 , 0 , 0
       0      .1       0   565.7      .1       0  609.11      .1       0
Bank Sta=565.7,609.11
XS Rating Curve= 0 ,0
Exp/Cntr=0.3,0.1

Type RM Length L Ch R = 1 ,457.2   ,104.06,91.44,92.01
XS GIS Cut Line= 6
     629590.0553    4314124.2437     629529.7302    4314202.5605
     629325.4714    4314556.0446     629383.7415    4314660.1592
     629411.3464    4314696.5306      629517.803    4314783.6058
#Sta/Elev= 30
       0   683.8   11.98  680.67   23.97  681.84   53.92  681.62  181.74  678.21
   246.2  674.86  295.31  673.92  326.01  669.99  421.16  663.88  485.63  663.77
  528.53  664.56  540.76   662.6  546.88  659.84     553  658.85  601.95  659.37
  611.13   657.3  628.87  657.58  636.58  659.74  642.51  660.69   651.4  660.88
  748.55  658.85  751.61  659.42  760.77  663.41  766.89  667.61     773   670.4
  782.17  671.76  785.22  672.96  788.28  675.48  803.56  682.35  809.67  685.93
#Mann= 3 , 0 , 0
       0      .1       0  601.95      .1       0  636.58      .1       0
Bank Sta=601.95,636.58
XS Rating Curve= 0 ,0
Exp/Cntr=0.3,0.1

Type RM Length L Ch R = 1 ,365.76  ,92.51,91.44,74.75
XS GIS Cut Line= 6
      629587.868    4314115.9181     629521.1866    4314203.1427
     629259.9228    4314653.7887     629309.7841    4314705.2585
     629330.3716    4314737.4773     629514.4901    4314800.9434
#Sta/Elev= 30
       0  684.96    9.15  680.86   15.25  680.04   21.35  681.51   39.65  681.79
  192.52  678.14  250.74  675.17  312.03  673.68  336.54   670.3  431.53   663.8
  505.07  664.09  551.03   662.9  609.25  662.98  639.65  662.02  645.63  660.51
  648.61  658.82   651.6  657.62  705.34  656.71  717.21  656.78     726  658.44
  816.62  658.81  850.09  656.25  874.43  656.27  880.52  657.43  898.78  666.04
  901.82  668.94  904.86  670.43  917.03  673.12  923.12  677.63  938.33  683.86
#Mann= 3 , 0 , 0
       0      .1       0  648.61      .1       0     726      .1       0
Bank Sta=648.61,726
XS Rating Curve= 0 ,0
Exp/Cntr=0.3,0.1

Type RM Length L Ch R = 1 ,274.32  ,104.7,91.44,71.01
XS GIS Cut Line= 6
     629585.7514    4314106.3931     629514.1861    4314197.1768
     629212.0204    4314731.7783     629230.9257    4314756.2678
     629271.5518    4314783.9013     629522.9568    4314816.8184
#Sta/Elev= 30
       0   684.6    6.08  680.21   12.17  679.17   24.34  681.23   42.59  681.77
  210.78  677.85  238.42  676.06  327.46  673.56  352.02  670.52  441.07   663.8
  533.18  663.93  560.81  662.77     656  662.59  668.28  661.65  695.91  661.63
  711.26  660.17  749.37   659.1  755.72   657.9  760.62  656.45  771.72  656.06
  785.74   656.1  801.06  657.72   868.3  657.52  975.21  659.31  984.38  658.89
   996.6  656.59 1008.82  660.59 1017.98   666.8 1027.15  671.23  1063.8  684.07
#Mann= 3 , 0 , 0
       0      .1       0  755.72      .1       0  801.06      .1       0
Bank Sta=755.72,801.06
XS Rating Curve= 0 ,0
Exp/Cntr=0.3,0.1

Type RM Length L Ch R = 1 ,182.88  ,80.44,76.79,71.14
XS GIS Cut Line= 6
     629585.7514    4314092.6347     629501.8985    4314196.4457
     629193.9934    4314757.4517     629166.7413    4314839.7373
     629248.7623    4314846.8811     629529.3068    4314826.3434
#Sta/Elev= 30
       0  683.32    6.07  680.23   15.16   678.8   45.49  682.16   60.66  681.06
  206.93  678.36  347.78  673.52  458.01  663.76  546.81  663.81  568.24  662.77
  706.03  662.02  727.46  660.26  776.38   659.2  833.17  659.91  860.08  662.51
  871.08  660.83  887.64  656.42  898.87  654.36  904.59  654.24  916.24  656.26
 1015.85  656.61 1110.63  658.64 1147.32  655.91  1156.5  656.46 1162.61   658.7
 1168.73  662.88 1190.13  672.87 1202.36  675.27 1208.48  677.96 1223.77  682.52
#Mann= 3 , 0 , 0
       0      .1       0  887.64      .1       0  916.24      .1       0
Bank Sta=887.64,916.24
XS Rating Curve= 0 ,0
Exp/Cntr=0.3,0.1

Type RM Length L Ch R = 1 ,106.0858,82.42,106.09,96.4
XS GIS Cut Line= 6
     629585.7514    4314084.1681     629489.4429    4314193.1766
     629191.6523    4314757.5384     629145.6147    4314916.2887
     629332.5432    4314915.8918      629537.112    4314832.8302
#Sta/Elev= 30
       0   683.6    9.09  679.54   18.18  678.43   48.49  682.47   84.85  680.34
  225.22  678.01  366.34  673.35  424.63  668.56  467.58  663.76  553.48  663.73
   685.4  661.65  709.94  662.13  737.55  660.38  801.81  659.22  844.38  660.18
  896.06  664.78  923.42  664.92   972.6  661.36  975.51  660.57  980.46  655.91
  984.24  654.27  987.16  654.22 1008.11  654.34 1019.57  655.79 1274.61  655.91
 1296.07  662.39  1311.4  668.94 1335.94  675.24 1351.27  680.24  1357.4  683.47
#Mann= 3 , 0 , 0
       0      .1       0  980.46      .1       0 1019.57      .1       0
Bank Sta=980.46,1019.57
XS Rating Curve= 0 ,0
Exp/Cntr=0.3,0.1

River Reach=Big Run (Dry)   ,1
Reach XY= 30
     629218.0614    4318440.9902     629183.4009     4318509.782
     629152.4446    4318536.2403     629123.8695    4318553.9675
     629023.0631    4318579.8967     629001.1026    4318606.0905
     628941.0879     4318634.872     628878.6003    4318612.9697
      628858.527    4318534.3685     628691.0103    4318449.4568
     628559.8967     4318491.859     628486.2224    4318484.3819
     628416.8983    4318433.3571     628381.9764    4318347.3275
     628321.1221    4318320.0753     628277.5155    4318264.3525
     628119.1353    4318215.3525     628007.0611    4318162.9125
     627963.1401    4318057.3436     627986.6881    4317904.9433
     627981.1318     4317886.687      627713.373    4317734.2867
     627655.1645    4317614.6948     627478.9517     4317509.655
     627437.9412    4317451.9757     627324.4347    4317359.6359
     627290.3034    4317273.6462      627197.699    4317195.8585
     627158.5406    4317198.7689     627113.7622    4317175.3165

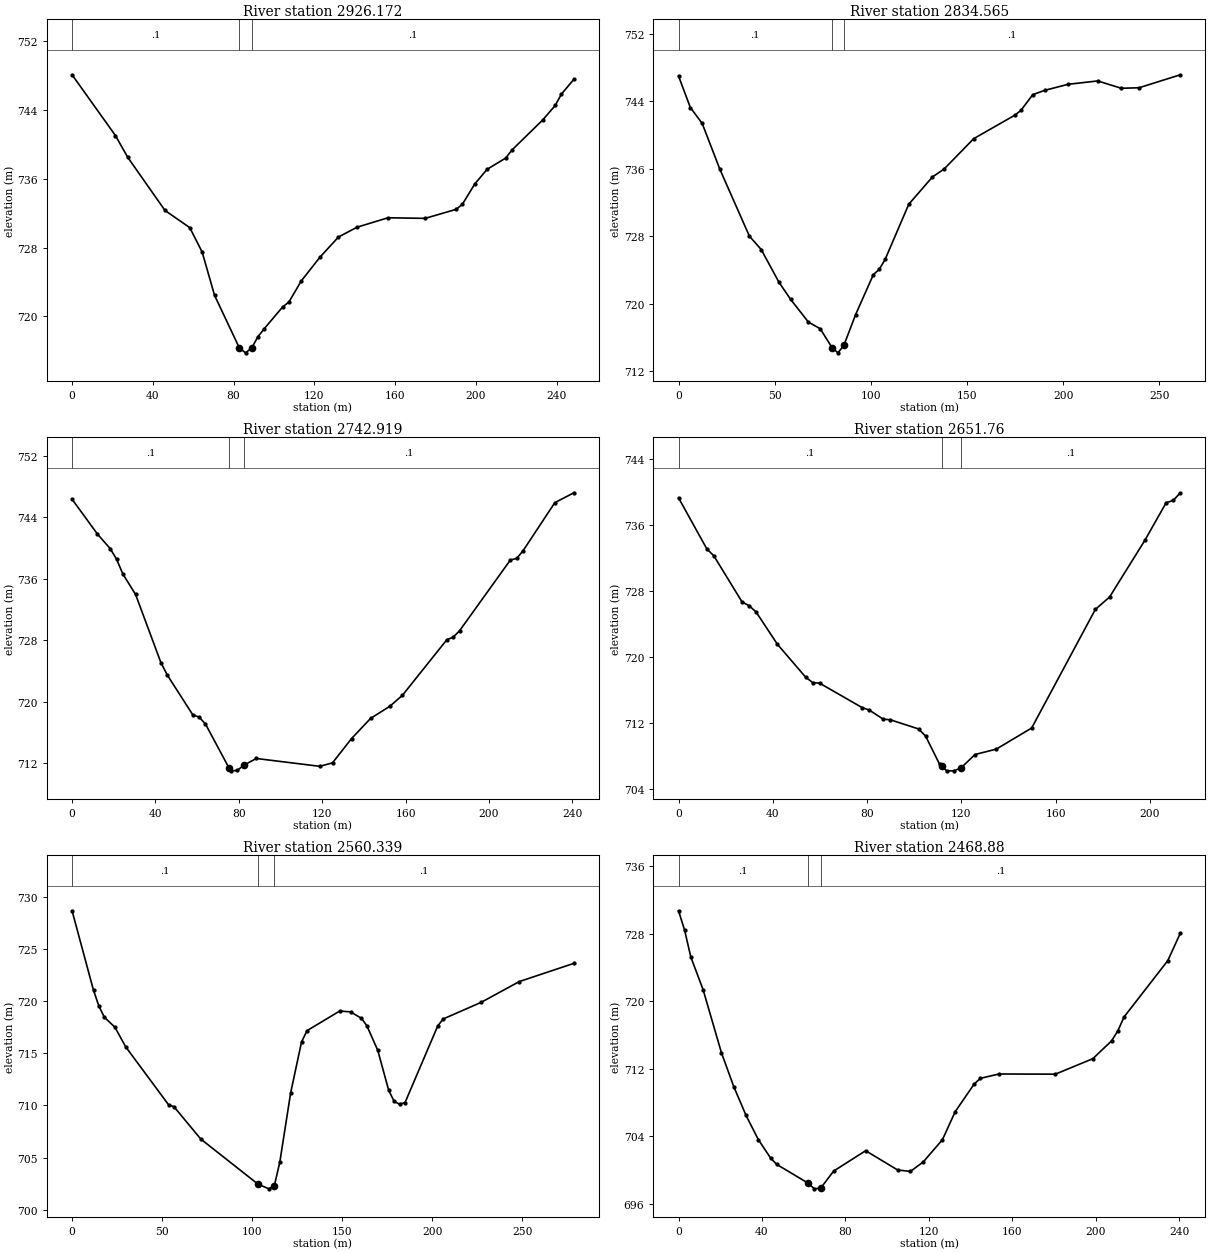
Type RM Length L Ch R = 1 ,2926.172,89.42,91.61,93.79
XS GIS Cut Line= 2
     629116.4207    4318453.2179       629337.36    4318566.9496
#Sta/Elev= 30
       0  748.11   21.47  741.04   27.61  738.49   46.02  732.32   58.29  730.32
   64.42  727.48   70.56  722.44   82.83  716.33    85.9  715.75   88.97  716.32
   92.03  717.62    95.1  718.54  104.31   721.1  107.37  721.66  113.51  724.12
  122.71  726.87  131.92  729.23  141.12  730.37  156.46  731.47  174.87   731.4
   190.2  732.45  193.27  733.03  199.41   735.4  205.54  737.11  214.75  738.42
  217.82  739.35  233.15  742.87  239.29  744.55  242.36  745.87  248.49  747.58
#Mann= 3 , 0 , 0
       0      .1       0   82.83      .1       0   88.97      .1       0
Bank Sta=82.83,88.97
XS Rating Curve= 0 ,0
Exp/Cntr=0.3,0.1

Type RM Length L Ch R = 1 ,2834.565,90.9,91.65,92.39
XS GIS Cut Line= 2
     629082.5843    4318482.7637     629219.8848    4318704.5332
#Sta/Elev= 30
       0  746.99    6.14  743.25   12.27  741.38   21.48  735.93   36.82     728
   42.96  726.41   52.17  722.54    58.3  720.48   67.51   717.8   73.65  717.01
   79.78  714.77   82.85  714.15   85.92  715.03   92.06  718.69  101.26  723.43
  104.33  724.06   107.4  725.24  119.68  731.78  131.95  735.01  138.09  735.97
  153.43  739.56  174.91  742.36  177.98  742.92  184.12  744.78  190.25  745.29
  202.53  746.01  217.87  746.41  230.15  745.54  239.35   745.6  260.83  747.14
#Mann= 3 , 0 , 0
       0      .1       0   79.78      .1       0   85.92      .1       0
Bank Sta=79.78,85.92
XS Rating Curve= 0 ,0
Exp/Cntr=0.3,0.1

Type RM Length L Ch R = 1 ,2742.919,89.94,91.16,91.15
XS GIS Cut Line= 2
     629009.2461    4318502.2222     629096.0596    4318726.7583
#Sta/Elev= 30
       0  746.38   12.19  741.83   18.28  739.94   21.33  738.57   24.38  736.62
   30.47  733.96   42.66  725.04   45.71  723.44    57.9  718.27   60.95  717.97
   63.99  717.07   75.38  711.29   76.18  710.96   79.23  711.01   82.28  711.67
   88.37  712.57  118.84  711.55  124.94     712  134.08  715.17  143.22   717.8
  152.36  719.36  158.46   720.8  179.79  728.06  182.84  728.39  185.88  729.22
  210.26  738.45  213.31  738.66  216.36  739.66  231.59  745.93  240.73  747.22
#Mann= 3 , 0 , 0
       0      .1       0   75.38      .1       0   82.28      .1       0
Bank Sta=75.38,82.28
XS Rating Curve= 0 ,0
Exp/Cntr=0.3,0.1

Type RM Length L Ch R = 1 ,2651.76 ,85.95,91.42,95.19
XS GIS Cut Line= 3
     628943.6593    4318510.8578      628963.247    4318622.9758
     628998.4635    4318715.6387
#Sta/Elev= 30
       0  739.25   11.98  733.07   14.98  732.22   26.96  726.63   29.95  726.18
   32.95   725.4   41.93  721.51   53.91  717.52   56.91  716.86    59.9  716.78
   77.87  713.83   80.87  713.54   86.86  712.42   89.85  712.35  101.84  711.24
  104.83  710.38  110.82  706.94  111.66  706.72  113.82  706.16  116.82  706.16
  119.82   706.5  125.83  708.14  134.84  708.79  149.86  711.35   176.9  725.73
  182.91  727.22  197.93  734.11  206.94  738.66  209.94  738.93  212.95  739.86
#Mann= 3 , 0 , 0
       0      .1       0  111.66      .1       0  119.82      .1       0
Bank Sta=111.66,119.82
XS Rating Curve= 0 ,0
Exp/Cntr=0.3,0.1

Type RM Length L Ch R = 1 ,2560.339,89.9,91.46,94.05
XS GIS Cut Line= 5
     628933.5657    4318523.4366     628896.4137    4318604.6418
     628886.3186     4318607.309      628882.904    4318607.8843
     628788.0839    4318755.3333
#Sta/Elev= 30
       0  728.66   11.91  721.03   14.88  719.53   17.86  718.47   23.81  717.49
   29.77  715.62   53.58  710.06   56.56  709.88   71.44  706.78   103.2  702.46
  109.25  702.01  112.27  702.31  115.29  704.56  121.34  711.23  127.38   716.1
  130.41  717.17  148.54  719.05  154.59  718.97  160.63  718.35  163.65  717.63
   169.7  715.27  175.74  711.45  178.77  710.39  181.79  710.12  184.81  710.28
  202.95  717.62  205.97  718.29  227.13  719.89  248.29  721.88  278.51  723.62
#Mann= 3 , 0 , 0
       0      .1       0   103.2      .1       0  112.27      .1       0
Bank Sta=103.2,112.27
XS Rating Curve= 0 ,0
Exp/Cntr=0.3,0.1

Type RM Length L Ch R = 1 ,2468.88 ,94.38,91.44,91.1
XS GIS Cut Line= 5
     628891.9762    4318480.9324     628863.4113    4318521.9991
     628855.3106    4318525.9507     628811.1404    4318588.6603
     628722.3341    4318644.4276
#Sta/Elev= 30
       0  730.69    2.94  728.37    5.89  725.22   11.77  721.37    20.6  713.88
   26.48   709.9   32.37  706.49   38.25  703.64   44.14  701.45   47.08   700.7
   62.07  698.49   65.17  697.81   68.24  697.92   74.38  699.91   89.72  702.32
  105.06  700.04   111.2  699.87  117.33  700.99  126.54  703.62  132.67  706.94
  141.73  710.19  144.73  710.88  153.72  711.39  180.68  711.37  198.66   713.2
  207.65  715.31  210.64  716.49  213.64  718.14  234.61   724.8  240.61  728.04
#Mann= 3 , 0 , 0
       0      .1       0   62.07      .1       0   68.24      .1       0
Bank Sta=62.07,68.24
XS Rating Curve= 0 ,0
Exp/Cntr=0.3,0.1

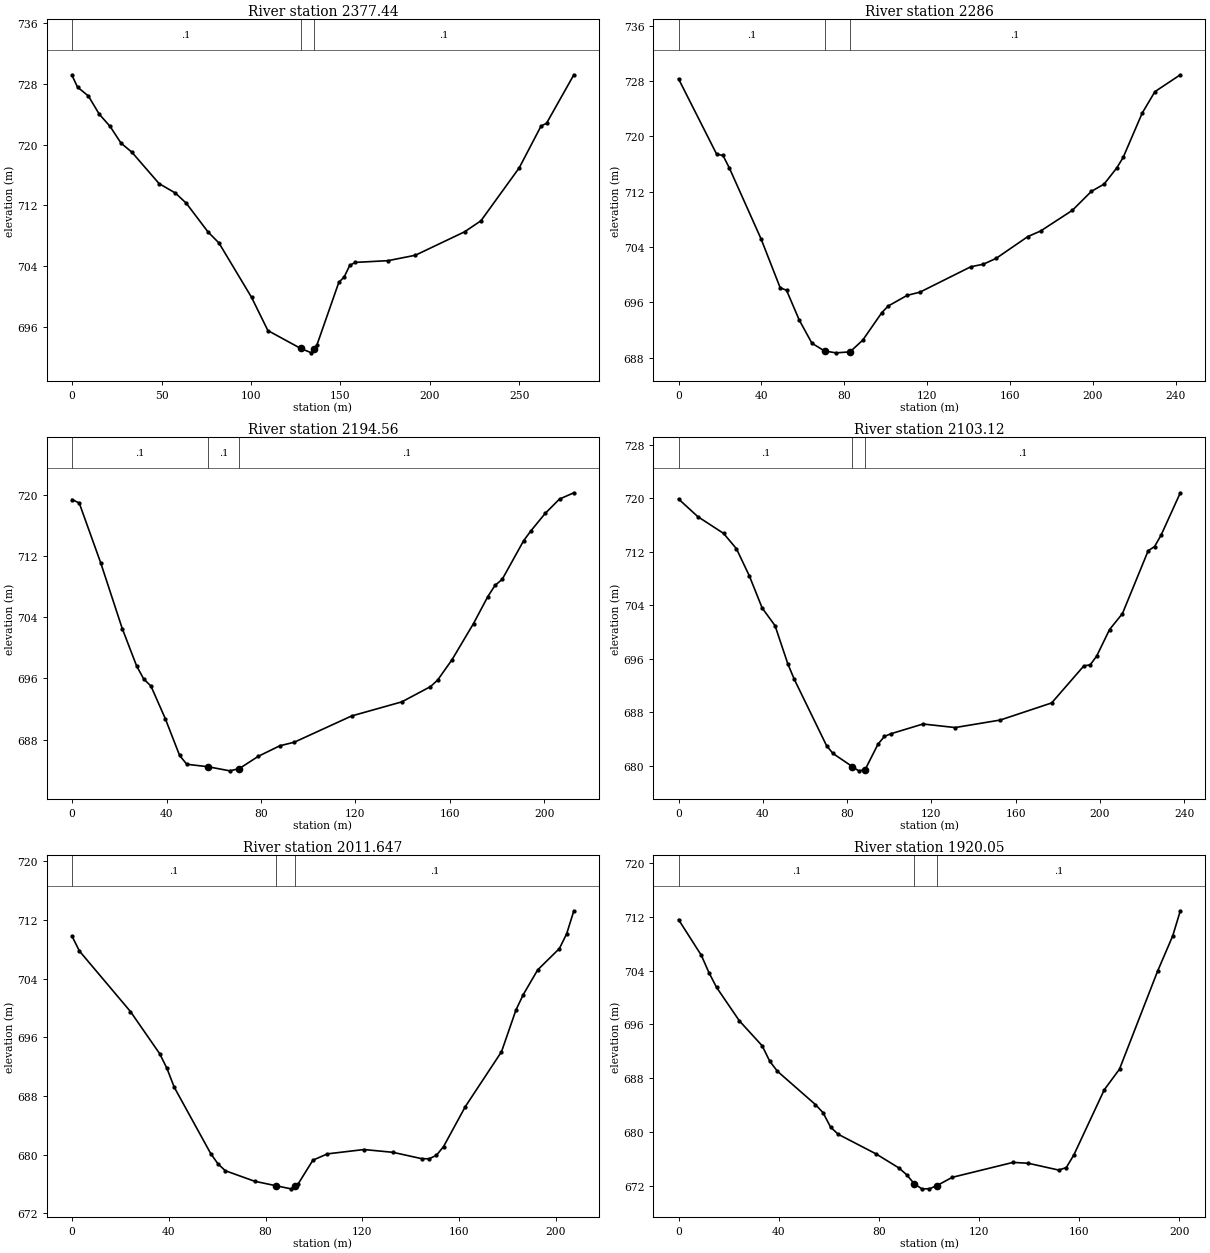
Type RM Length L Ch R = 1 ,2377.44 ,93.12,91.44,89.63
XS GIS Cut Line= 3
     628827.2424    4318371.3339     628772.6828    4318486.8054
     628695.5333    4318618.7063
#Sta/Elev= 30
       0  729.09    3.04  727.56    9.12  726.39    15.2     724   21.29  722.38
   27.37  720.19   33.45     719   48.65  714.87   57.77  713.63   63.86  712.29
   76.02  708.51    82.1  707.07  100.35  699.91  109.47  695.55  127.71  693.21
  133.82  692.62  135.26   693.1  136.88  693.65  149.11  701.88  152.16  702.61
  155.22  704.11  158.27  704.51  176.61  704.74  191.89  705.45   219.4  708.53
  228.56  709.98  249.96  716.94  262.18  722.44  265.24   722.8  280.52  729.18
#Mann= 3 , 0 , 0
       0      .1       0  127.71      .1       0  135.26      .1       0
Bank Sta=127.71,135.26
XS Rating Curve= 0 ,0
Exp/Cntr=0.3,0.1

Type RM Length L Ch R = 1 ,2286    ,93,91.44,90.44
XS GIS Cut Line= 2
     628695.3314     4318375.512     628675.6313    4318616.8458
#Sta/Elev= 30
       0  728.33   18.39  717.43   21.46  717.24   24.52  715.43   39.85  705.15
   49.04   698.1   52.11  697.74   58.24  693.43   64.37  690.07    70.5  688.94
   76.05  688.68   82.76  688.82   88.89  690.52   98.08  694.49  101.15  695.45
  110.34     697  116.47  697.46  140.99  701.13  147.12  701.51  153.25  702.35
  168.58  705.51  174.71  706.31  190.03   709.3  199.23  712.05  205.36   713.1
  211.49  715.45  214.55  716.96  223.75  723.38  229.88  726.48  242.14  728.92
#Mann= 3 , 0 , 0
       0      .1       0    70.5      .1       0   82.76      .1       0
Bank Sta=70.5,82.76
XS Rating Curve= 0 ,0
Exp/Cntr=0.3,0.1

Type RM Length L Ch R = 1 ,2194.56 ,89.88,91.44,92.52
XS GIS Cut Line= 2
     628585.9135    4318409.1687     628638.9302    4318615.0052
#Sta/Elev= 30
       0  719.37    3.04  718.91   12.15  711.08   21.26  702.51   27.33  697.64
   30.36  695.92    33.4  695.01   39.47  690.76   45.55  685.94   48.58  684.79
   57.69  684.46    66.8  683.93   70.77  684.21   78.95  685.84   88.06  687.21
   94.13  687.67  118.42   691.1  139.68  692.94  151.82  694.93  154.86  695.79
  160.93  698.44  170.04  703.17  176.12   706.7  179.15  708.15  182.19  708.94
   191.3     714  194.34  715.27  200.41  717.56  206.48  719.43  212.55  720.25
#Mann= 3 , 0 , 0
       0      .1       0   57.69      .1       0   70.77      .1       0
Bank Sta=57.69,70.77
XS Rating Curve= 0 ,0
Exp/Cntr=0.3,0.1

Type RM Length L Ch R = 1 ,2103.12 ,89.17,91.47,93.78
XS GIS Cut Line= 2
     628522.6931    4318408.1221     628500.6974    4318645.1928
#Sta/Elev= 30
       0  719.86    9.16  717.22   21.37  714.72   27.47  712.43   33.58  708.38
   39.68  703.57   45.79  700.93   51.89  695.19   54.94   692.9   70.21  683.01
   73.26  681.83   82.42  679.87   85.47  679.23   88.52   679.4   94.63  683.21
   97.68  684.37  100.73  684.77  115.99  686.23  131.25   685.7  152.62  686.82
  177.04  689.38   192.3  694.91  195.35  695.08  198.41  696.39  204.51  700.35
  210.62  702.73  222.83  712.12  225.88  712.76  228.93  714.44  238.09  720.79
#Mann= 3 , 0 , 0
       0      .1       0   82.42      .1       0   88.52      .1       0
Bank Sta=82.42,88.52
XS Rating Curve= 0 ,0
Exp/Cntr=0.3,0.1

Type RM Length L Ch R = 1 ,2011.647,89.61,91.6,94.14
XS GIS Cut Line= 3
     628492.1028    4318377.9485     628417.7645    4318473.0375
     628350.1274    4318527.4319
#Sta/Elev= 30
       0  709.79    3.02  707.78   24.14  699.52   36.21  693.78   39.23  691.77
   42.24   689.2   57.33  680.15   60.35  678.74   63.37  677.81   75.44  676.38
   84.49  675.75   90.52  675.34   92.24  675.74   93.54  676.04   99.58  679.25
  105.61  680.11   120.7   680.7  132.67  680.32  144.64  679.45  147.63  679.44
  150.63   679.9  153.62  681.11   162.6  686.55  177.56  694.03  183.55  699.73
  186.54  701.81  192.53   705.2  201.51  708.11   204.5  710.11  207.49  713.26
#Mann= 3 , 0 , 0
       0      .1       0   84.49      .1       0   92.24      .1       0
Bank Sta=84.49,92.24
XS Rating Curve= 0 ,0
Exp/Cntr=0.3,0.1

Type RM Length L Ch R = 1 ,1920.05 ,94.24,91.25,88.26
XS GIS Cut Line= 2
     628487.4726    4318330.9849      628304.165    4318412.1438
#Sta/Elev= 30
       0  711.57    9.11  706.26   12.15  703.69   15.19   701.5    24.3  696.53
   33.41  692.82   36.45  690.52   39.49  689.04   54.67  684.09   57.71  682.89
   60.75  680.73   63.79  679.67   78.97  676.74   88.09  674.65   91.12  673.66
   94.16  672.32    97.2  671.56  100.24  671.57  103.27  672.05  109.35  673.27
  133.65  675.49  139.72  675.36  151.87  674.35  154.91  674.72  157.95  676.61
   170.1  686.29  176.17  689.35  191.36  703.88  197.43  709.15  200.47  712.88
#Mann= 3 , 0 , 0
       0      .1       0   94.16      .1       0  103.27      .1       0
Bank Sta=94.16,103.27
XS Rating Curve= 0 ,0
Exp/Cntr=0.3,0.1

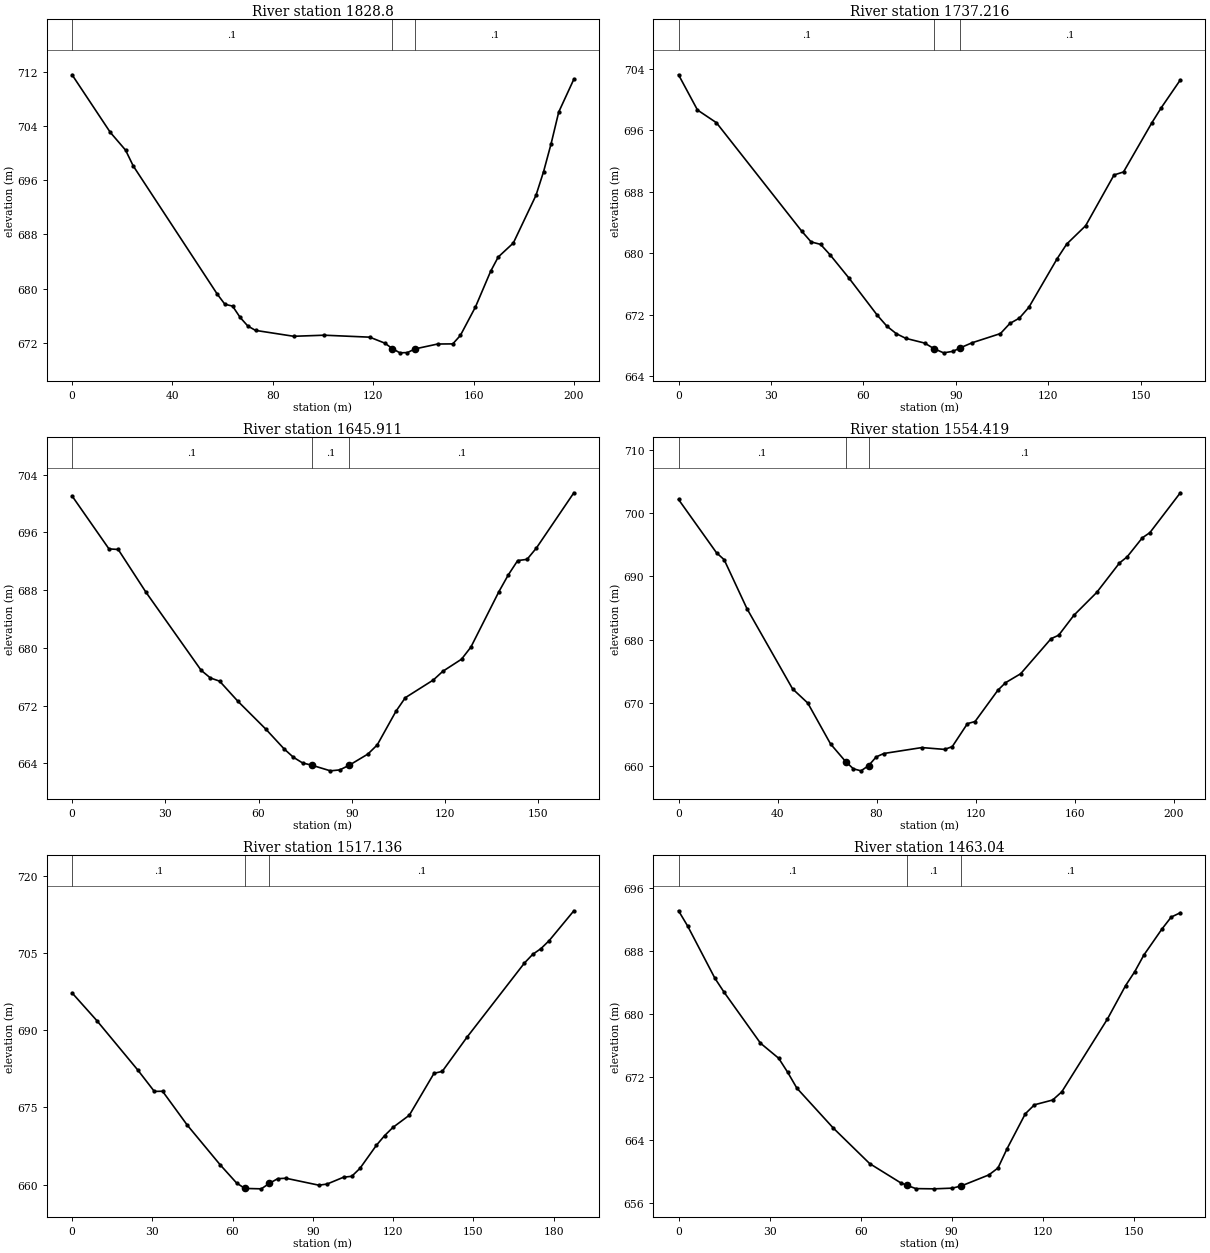
Type RM Length L Ch R = 1 ,1828.8  ,91.83,91.58,91.33
XS GIS Cut Line= 4
     628400.8214     4318214.568     628334.9089    4318298.3258
     628319.1525    4318334.0969     628283.0816    4318374.6412
#Sta/Elev= 30
       0  711.54   15.23  703.05   21.32  700.43   24.36  698.11   57.86   679.2
    60.9  677.71   63.95  677.44   66.99  675.76   70.04   674.5   73.09  673.86
   88.31  672.99  100.49  673.15  118.61  672.86  124.62  671.98  127.63  671.17
  130.64  670.55  133.64  670.59  136.65  671.13  145.67  671.85   151.7  671.87
  154.71  673.11  160.74  677.32  166.77  682.56  169.79  684.67  175.82  686.74
  184.86  693.78  187.88  697.27  190.89   701.4  193.91  706.05  199.94  710.89
#Mann= 3 , 0 , 0
       0      .1       0  127.63      .1       0  136.65      .1       0
Bank Sta=127.63,136.65
XS Rating Curve= 0 ,0
Exp/Cntr=0.3,0.1

Type RM Length L Ch R = 1 ,1737.216,91.39,91.3,91.3
XS GIS Cut Line= 2
     628292.8932    4318175.0458     628238.1443    4318328.4142
#Sta/Elev= 30
       0  703.24    6.15  698.65   12.29     697   39.94  682.89   43.02  681.47
   46.09  681.15   49.16   679.8   55.31  676.76   64.52  671.91    67.6   670.5
   70.67  669.52   73.74  668.91   79.89  668.29   82.96  667.55   86.03  667.02
   89.11  667.22   91.25  667.64   95.25  668.33  104.47  669.53  107.54  670.85
  110.61  671.54  113.69  672.95   122.9   679.3  125.98  681.19  132.12  683.58
  141.34  690.19  144.41  690.58  153.63     697   156.7  698.97  162.85  702.57
#Mann= 3 , 0 , 0
       0      .1       0   82.96      .1       0   91.25      .1       0
Bank Sta=82.96,91.25
XS Rating Curve= 0 ,0
Exp/Cntr=0.3,0.1

Type RM Length L Ch R = 1 ,1645.911,91.16,91.49,91.65
XS GIS Cut Line= 3
     628196.3201     4318155.202     628175.8762    4318232.6608
      628148.695    4318309.3221
#Sta/Elev= 30
       0  701.05   11.87  693.72   14.84  693.64   23.74  687.74   41.54   676.9
   44.51  675.84   47.47   675.4   53.41  672.59   62.31  668.77   68.24  666.01
   71.21  664.86   74.18  664.07   77.14  663.76   83.12  662.98   86.14  663.11
   89.15  663.75   95.17   665.3   98.19  666.57  104.21  671.23  107.22  673.11
  116.26  675.57  119.27  676.76   125.3  678.44  128.31  680.11  137.35  687.81
  140.36  690.12  143.37   692.1  146.39  692.27   149.4  693.84  161.45  701.49
#Mann= 3 , 0 , 0
       0      .1       0   77.14      .1       0   89.15      .1       0
Bank Sta=77.14,89.15
XS Rating Curve= 0 ,0
Exp/Cntr=0.3,0.1

Type RM Length L Ch R = 1 ,1554.419,37.08,37.28,37.56
XS GIS Cut Line= 2
     628116.5177    4318134.9257     628041.5385    4318323.2127
#Sta/Elev= 30
       0  702.21   15.35  693.75   18.42  692.66   27.64  684.89   46.06  672.17
    52.2  669.92   61.41  663.43   67.56  660.61   70.63  659.49    73.7  659.17
   76.77     660   79.84  661.38   82.91  661.92   98.26  662.86  107.47  662.57
  110.55  663.01  116.69  666.66  119.76  666.99  128.97  671.95  132.04  673.14
  138.18  674.57  150.46  680.13  153.54  680.68  159.68  683.84  168.89  687.46
   178.1  692.14  181.17   693.1  187.31  696.12  190.38  696.95  202.67  703.27
#Mann= 3 , 0 , 0
       0      .1       0   67.56      .1       0   76.77      .1       0
Bank Sta=67.56,76.77
XS Rating Curve= 0 ,0
Exp/Cntr=0.3,0.1

Type RM Length L Ch R = 1 ,1517.136,53.39,54.1,55.22
XS GIS Cut Line= 2
     628083.5449    4318126.4816     628005.2281    4318296.8736
#Sta/Elev= 30
       0  697.28    9.22  691.91   24.59  682.26   30.74  678.12   33.82  678.15
   43.04  671.57   55.34  663.85   61.48  660.31   64.56  659.25   70.71  659.17
   73.78  660.25   76.86  661.15   79.93  661.23   92.23  659.88    95.3   660.1
  101.45  661.43  104.52  661.61   107.6  663.16  113.75  667.65  116.82  669.53
   119.9  671.11  126.04  673.49  135.27  681.64  138.34  682.01  147.56  688.64
  169.08   703.1  172.16  704.78  175.23  705.89  178.31  707.45  187.53  713.25
#Mann= 3 , 0 , 0
       0      .1       0   64.56      .1       0   73.78      .1       0
Bank Sta=64.56,73.78
XS Rating Curve= 0 ,0
Exp/Cntr=0.3,0.1

Type RM Length L Ch R = 1 ,1463.04 ,88.52,91.43,94.18
XS GIS Cut Line= 4
     628054.8451    4318108.5468     628009.3166    4318160.3551
     628005.8828    4318165.5407     627946.7138    4318233.5088
#Sta/Elev= 30
       0  693.15       3  691.21   11.99  684.56   14.99   682.8   26.99  676.31
   32.99  674.39   35.98  672.59   38.98  670.59   50.98  665.51   62.97  660.99
   73.12  658.56   75.19  658.23   78.19  657.81    84.2  657.78   90.21  657.87
   93.21  658.16  102.22  659.55  105.23  660.43  108.23  662.89  114.24  667.33
  117.24  668.47  123.25  669.08  126.25  670.12  141.27  679.37  147.28  683.64
  150.29  685.41  153.29  687.52   159.3  690.86   162.3  692.35   165.3   692.9
#Mann= 3 , 0 , 0
       0      .1       0   75.19      .1       0   93.21      .1       0
Bank Sta=75.19,93.21
XS Rating Curve= 0 ,0
Exp/Cntr=0.3,0.1

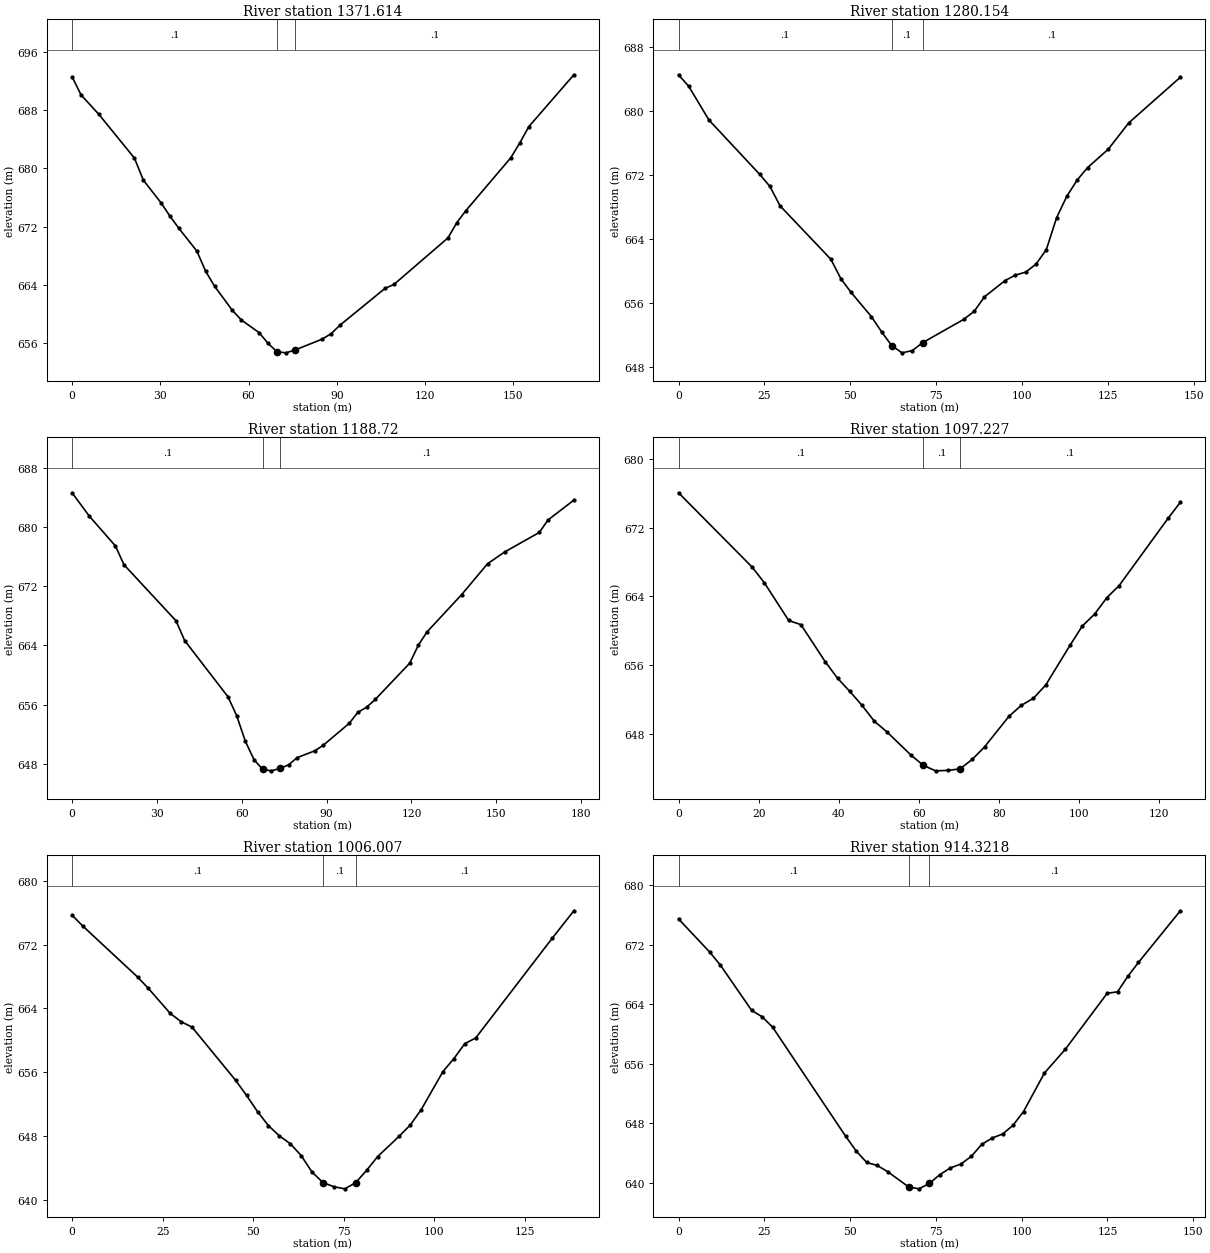
Type RM Length L Ch R = 1 ,1371.614,88.64,91.46,93.33
XS GIS Cut Line= 3
     628040.8771    4318067.8893     627972.2973    4318080.0842
     627874.8507     4318106.254
#Sta/Elev= 30
       0  692.65    3.03  690.16    9.09  687.47    21.2  681.43   24.23  678.39
   30.29  675.24   33.31   673.4   36.34  671.73    42.4  668.62   45.43  665.81
   48.46  663.75   54.51  660.42   57.54  659.11    63.6  657.36   66.63  655.88
   69.66  654.73   72.71  654.58   75.77  654.97   84.94  656.46      88   657.2
   91.06  658.39  106.35  663.46   109.4  664.01  127.75  670.42  130.81  672.55
  133.86  674.19  149.15  681.49  152.21  683.54  155.27  685.78  170.56  692.92
#Mann= 3 , 0 , 0
       0      .1       0   69.66      .1       0   75.77      .1       0
Bank Sta=69.66,75.77
XS Rating Curve= 0 ,0
Exp/Cntr=0.3,0.1

Type RM Length L Ch R = 1 ,1280.154,92.24,91.43,90.5
XS GIS Cut Line= 3
     628033.4798    4318001.2263     627972.2317    4317991.3802
     627889.9981    4317974.4251
#Sta/Elev= 30
       0   684.5    2.95  683.07    8.86  678.85   23.63  672.07   26.59  670.57
   29.54  668.15   44.31  661.49   47.26  659.04   50.22  657.34   56.13  654.32
   59.08  652.43   62.03  650.71   65.03  649.81   68.03  650.09   71.03  651.08
   83.03     654   86.02  654.99   89.02   656.8   95.02  658.83   98.02  659.51
  101.02  659.88  104.02  660.88  107.01  662.68  110.01  666.68  113.01  669.37
  116.01  671.38  119.01  672.92  125.01   675.2     131   678.5     146  684.19
#Mann= 3 , 0 , 0
       0      .1       0   62.03      .1       0   71.03      .1       0
Bank Sta=62.03,71.03
XS Rating Curve= 0 ,0
Exp/Cntr=0.3,0.1

Type RM Length L Ch R = 1 ,1188.72 ,96.43,91.49,87.28
XS GIS Cut Line= 3
     628056.7095    4317899.2054     627949.5806    4317902.1813
     627882.0606    4317921.5083
#Sta/Elev= 30
       0  684.59    6.12  681.43   15.31  677.42   18.37  674.87   36.74  667.32
   39.81  664.65   55.12  657.06   58.18  654.53   61.24  651.08    64.3  648.59
   67.36  647.28   70.43  647.07   73.49  647.39   76.55  647.88   79.61  648.86
   85.74  649.76    88.8  650.52   97.98  653.48  101.05  654.97  104.11  655.65
  107.17   656.7  119.38   661.6  122.44  664.04  125.49  665.82  137.71  670.84
  146.87  675.01  152.97  676.61  165.19  679.24  168.24  680.91   177.4   683.6
#Mann= 3 , 0 , 0
       0      .1       0   67.36      .1       0   73.49      .1       0
Bank Sta=67.36,73.49
XS Rating Curve= 0 ,0
Exp/Cntr=0.3,0.1

Type RM Length L Ch R = 1 ,1097.227,91.16,91.22,91.28
XS GIS Cut Line= 2
     627949.4054    4317788.7818     627888.6752    4317898.3572
#Sta/Elev= 29
       0  676.05   18.33  667.43   21.39  665.61    27.5   661.2   30.56  660.71
   36.67  656.37   39.72  654.47   42.78  652.94   45.83  651.31   48.89  649.48
   51.95  648.27   58.06  645.53   61.11  644.35   64.17  643.71   67.22  643.76
   70.28  643.94   73.33  645.04   76.39  646.49    82.5  650.05   85.56  651.32
   88.61  652.15   91.67  653.69   97.78  658.34  100.83  660.57  103.89  661.94
  106.95  663.86     110  665.25  122.22  673.08  125.28  674.94
#Mann= 3 , 0 , 0
       0      .1       0   61.11      .1       0   70.28      .1       0
Bank Sta=61.11,70.28
XS Rating Curve= 0 ,0
Exp/Cntr=0.3,0.1

Type RM Length L Ch R = 1 ,1006.007,92.27,91.69,91.11
XS GIS Cut Line= 2
     627874.0956    4317738.8593     627805.1329    4317858.9563
#Sta/Elev= 30
       0  675.69    3.01   674.3   18.06  667.94   21.07   666.5    27.1  663.36
   30.11  662.33   33.12  661.64   45.16  654.96   48.17  653.07   51.18  651.05
   54.19  649.29    57.2  648.01   60.21  647.03   63.22  645.54   66.23  643.46
   69.24  642.15   72.25  641.63   75.27  641.36   78.28  642.13   81.29  643.68
    84.3  645.39   90.32  647.98   93.33  649.36   96.34  651.28  102.36  656.07
  105.37  657.69  108.38  659.57  111.39  660.28  132.47  672.77  138.49  676.24
#Mann= 3 , 0 , 0
       0      .1       0   69.24      .1       0   78.28      .1       0
Bank Sta=69.24,78.28
XS Rating Curve= 0 ,0
Exp/Cntr=0.3,0.1

Type RM Length L Ch R = 1 ,914.3218,40.94,30.98,31.45
XS GIS Cut Line= 2
     627781.0932    4317697.0377     627727.3452     4317833.027
#Sta/Elev= 30
       0  675.43    9.14  670.96   12.19  669.24   21.32  663.15   24.37   662.3
   27.42   660.9   48.74  646.23   51.79  644.27   54.83  642.74   57.88  642.34
   60.93  641.51   67.02  639.47   70.07   639.2   73.11  639.93   76.16  641.11
   79.21  642.01   82.25  642.52    85.3  643.55   88.34  645.16   91.39  646.02
   94.44  646.56   97.48  647.73  100.53  649.57  106.62  654.74  112.72  657.94
   124.9  665.44  127.95  665.66  130.99  667.77  134.04   669.6  146.23  676.53
#Mann= 3 , 0 , 0
       0      .1       0   67.02      .1       0   73.11      .1       0
Bank Sta=67.02,73.11
XS Rating Curve= 0 ,0
Exp/Cntr=0.3,0.1