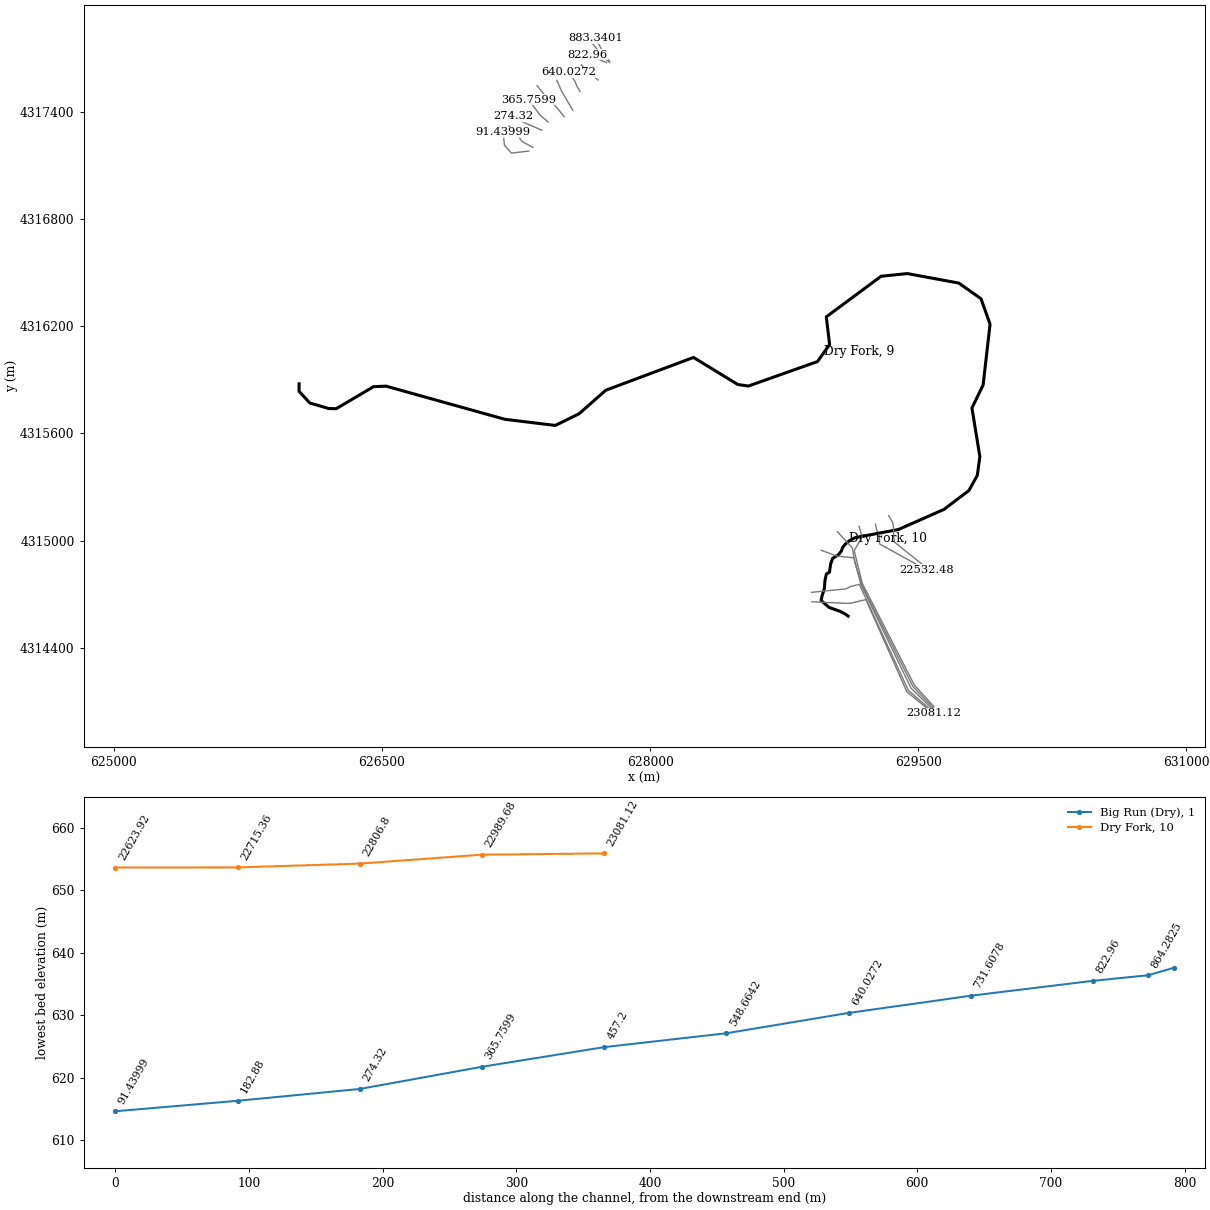
HEC-RAS study RedCreek.prj: RedCreek

--- RedCreek.g01 (geometry) --- (continued)

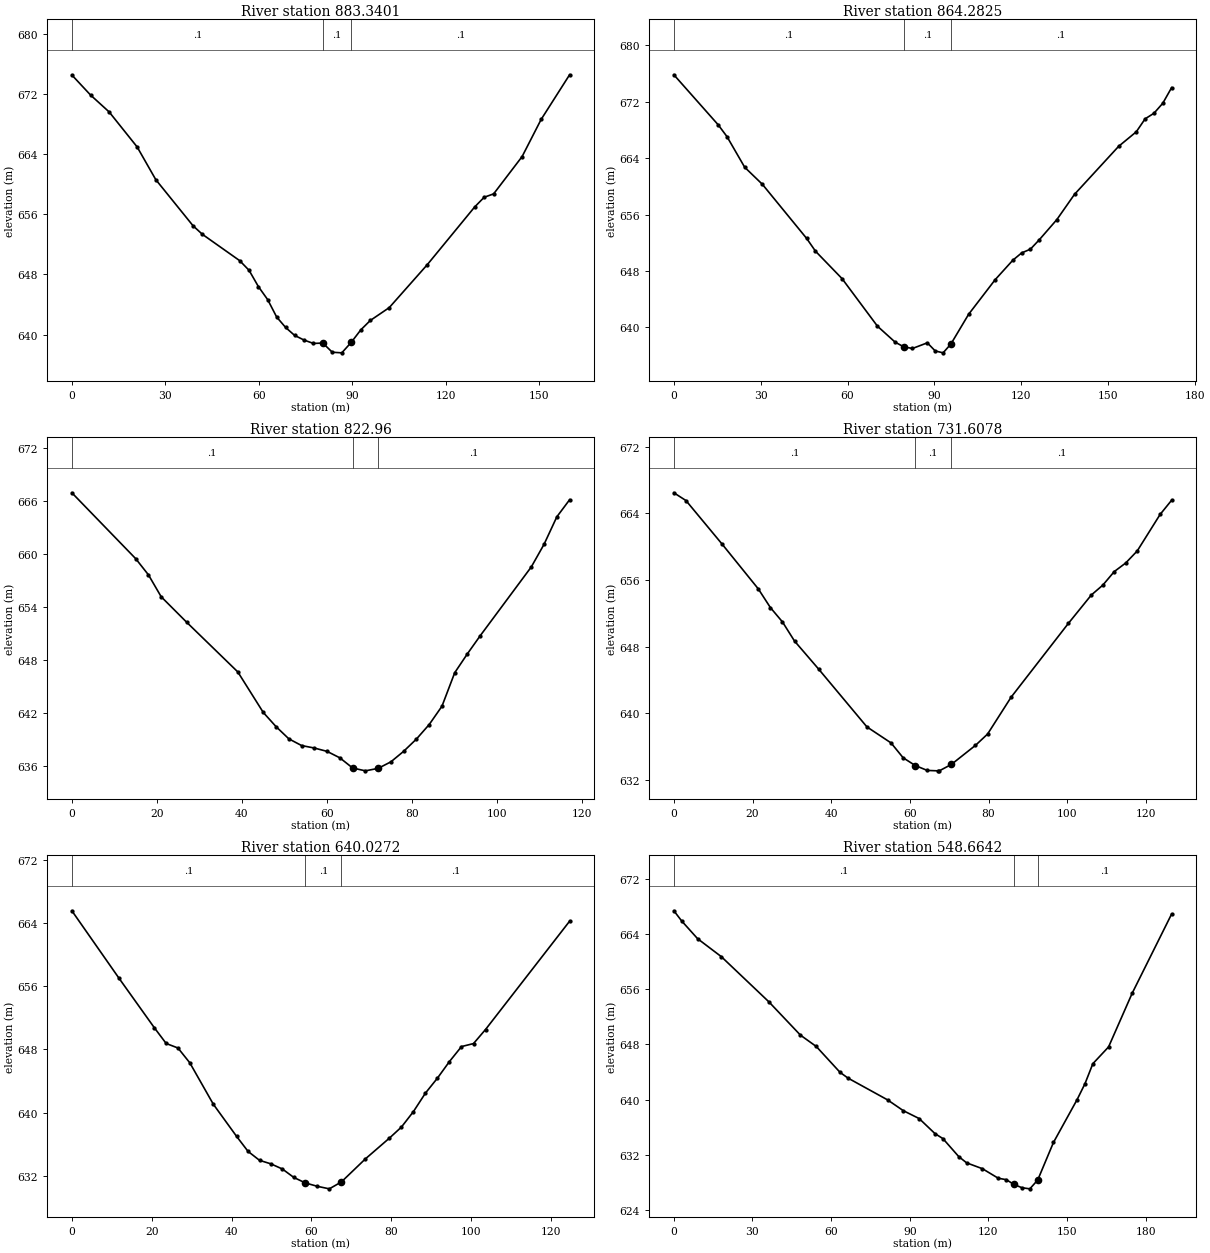
Type RM Length L Ch R = 1 ,883.3401,15.89,19.06,18.85
XS GIS Cut Line= 5
     627773.6524    4317682.3125     627729.4668    4317727.0272
     627725.4981    4317734.7001     627732.6419    4317740.2564
     627695.5951    4317810.2728
#Sta/Elev= 30
       0   674.5    5.99  671.84   11.97  669.59   20.95  664.94   26.94  660.59
   38.92  654.45   41.91  653.32   53.88  649.82   56.88  648.54   59.87  646.38
   62.86  644.64   65.74  642.33   68.62  640.94    71.5  639.89   74.52  639.27
   77.54  638.82   80.55  638.87    83.6  637.65   86.65  637.57   89.69  638.97
   92.74  640.62   95.79  641.87  101.88  643.58  114.07  649.28   129.3  656.96
  132.35  658.25  135.39   658.7  144.53  663.66  150.63  668.59  159.77  674.53
#Mann= 3 , 0 , 0
       0      .1       0   80.55      .1       0   89.69      .1       0
Bank Sta=80.55,89.69
XS Rating Curve= 0 ,0
Exp/Cntr=0.3,0.1

Type RM Length L Ch R = 1 ,864.2825,31.93,41.32,44.38
XS GIS Cut Line= 6
      627773.912    4317675.3351     627713.5918    4317722.2647
     627712.2689    4317728.0855     627715.1793    4317732.3189
     627711.7397    4317739.7272     627662.7867     4317798.102
#Sta/Elev= 30
       0  675.83   15.29  668.74   18.34  667.06   24.46  662.71   30.57  660.29
   45.86  652.61   48.91   650.8   58.08  646.91   70.31  640.16   76.43  637.89
   79.41  637.23    82.4     637   87.53   637.8   90.25  636.65   92.98  636.38
    95.7  637.65  101.79  641.85  110.94  646.75  117.03  649.51  120.08  650.55
  123.13  651.09  126.17  652.41  132.27  655.29  138.36  658.87   153.6  665.68
  159.69  667.74  162.74  669.58  165.79  670.37  168.84  671.79  171.88     674
#Mann= 3 , 0 , 0
       0      .1       0   79.41      .1       0    95.7      .1       0
Bank Sta=79.41,95.7
XS Rating Curve= 0 ,0
Exp/Cntr=0.3,0.1

Type RM Length L Ch R = 1 ,822.96  ,93.12,91.35,90.23
XS GIS Cut Line= 2
     627756.1116    4317674.6223     627647.4856    4317718.3088
#Sta/Elev= 28
       0  666.94   15.01  659.49   18.01  657.66   21.01  655.18   27.02  652.29
   39.03  646.68   45.03  642.09   48.03  640.49   51.04  639.11   54.04  638.35
   57.04  638.07   60.04  637.69   63.04  636.96   66.05  635.81   69.05  635.49
   72.05  635.77   75.05  636.51   78.05   637.7   81.06  639.09   84.06  640.73
   87.06   642.8   90.06  646.59   93.06  648.74   96.07  650.78  108.08  658.56
  111.08  661.12  114.08  664.22  117.08  666.15
#Mann= 3 , 0 , 0
       0      .1       0   66.05      .1       0   72.05      .1       0
Bank Sta=66.05,72.05
XS Rating Curve= 0 ,0
Exp/Cntr=0.3,0.1

Type RM Length L Ch R = 1 ,731.6078,98.06,91.58,90.24
XS GIS Cut Line= 3
     627708.5774    4317577.3685     627643.1449    4317628.1337
     627614.9147    4317661.5061
#Sta/Elev= 27
       0  666.46    3.07  665.53   12.27   660.3   21.47  654.93   24.54  652.69
   27.61  650.97   30.67  648.68   36.81  645.31   49.08  638.38   55.21  636.46
   58.28  634.68   61.35  633.75   64.41  633.16   67.07  633.11   67.48  633.11
   70.55  633.88   76.68  636.17   79.75  637.52   85.73  641.94   100.3   650.8
  106.13   654.2  109.04  655.38  111.96  657.01  114.87  658.04  117.79  659.48
  123.61  663.86  126.53  665.56
#Mann= 3 , 0 , 0
       0      .1       0   61.35      .1       0   70.55      .1       0
Bank Sta=61.35,70.55
XS Rating Curve= 0 ,0
Exp/Cntr=0.3,0.1

Type RM Length L Ch R = 1 ,640.0272,90.33,91.36,90.69
XS GIS Cut Line= 4
     627607.7018    4317513.1412     627588.1094    4317546.1653
     627582.0424    4317565.3109     627545.7849    4317620.7108
#Sta/Elev= 28
       0  665.55   11.81  657.01   20.68  650.73   23.63  648.75   26.58  648.18
   29.54  646.31   35.44  641.06   41.27  636.99   44.14  635.09   47.01  633.96
   49.88  633.51   52.74  632.86   55.61  631.79   58.48   631.1   61.49  630.67
    64.5  630.35   67.51  631.22   73.53  634.14   79.55  636.77   82.56  638.17
   85.57  640.13   88.58  642.47   91.59  644.37    94.6  646.47   97.61  648.36
  100.62  648.74  103.63  650.52  124.69  664.23
#Mann= 3 , 0 , 0
       0      .1       0   58.48      .1       0   67.51      .1       0
Bank Sta=58.48,67.51
XS Rating Curve= 0 ,0
Exp/Cntr=0.3,0.1

Type RM Length L Ch R = 1 ,548.6642,87.64,91.46,94.65
XS GIS Cut Line= 3
      627567.025    4317407.7702     627503.3672     4317517.432
     627478.1248    4317575.2518
#Sta/Elev= 30
       0  667.35    3.02  665.86    9.06  663.31   18.11  660.71   36.23  654.18
    48.3  649.35   54.34  647.71    63.4  643.97   66.42  643.14   81.51  639.99
   87.55  638.42   93.59  637.28   99.63   635.1  102.65  634.38  108.68  631.78
   111.7  630.87  117.74  630.02  123.78  628.64   126.8  628.44   129.8  627.74
  132.81  627.27  135.81  627.11  138.82  628.39  144.82  633.82  153.84  640.02
  156.84  642.32  159.85  645.22  165.85  647.65  174.87  655.43  189.89  666.87
#Mann= 3 , 0 , 0
       0      .1       0   129.8      .1       0  138.82      .1       0
Bank Sta=129.8,138.82
XS Rating Curve= 0 ,0
Exp/Cntr=0.3,0.1

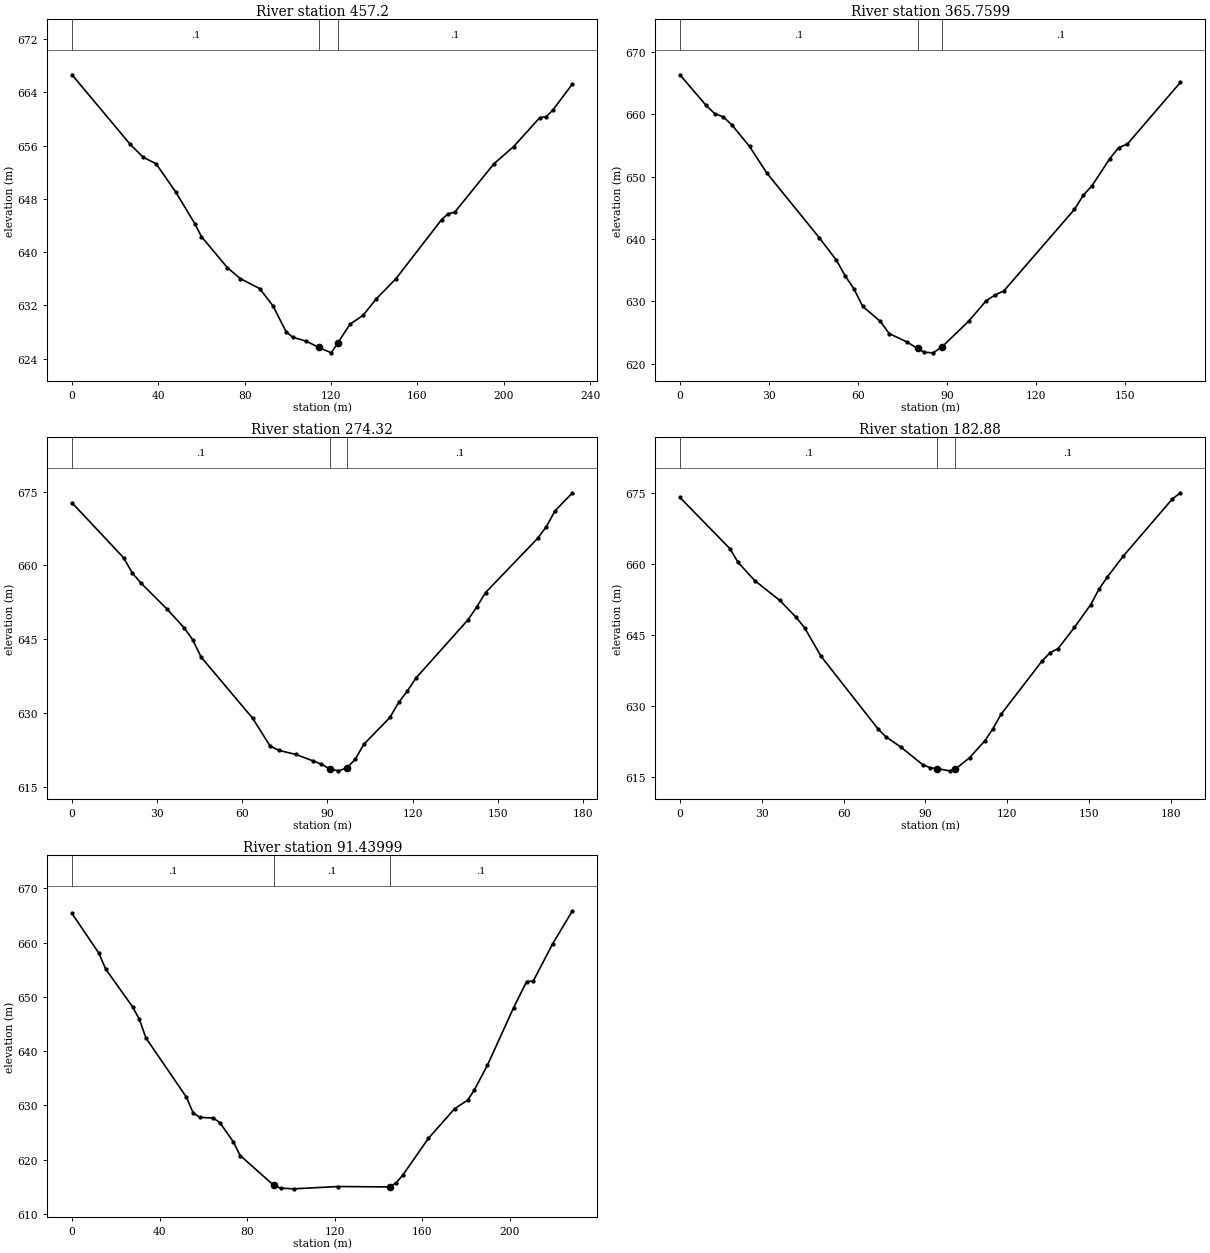
Type RM Length L Ch R = 1 ,457.2   ,94.44,91.44,88.85
XS GIS Cut Line= 5
     627520.3222    4317371.4942     627464.5128    4317438.1284
     627444.8993    4317452.7928     627432.5168    4317464.9654
     627367.7934    4317545.0892
#Sta/Elev= 30
       0  666.65   26.97   656.2   32.97  654.27   38.96  653.28   47.95  649.09
   56.95  644.25   59.94  642.35   71.93  637.69   77.93  636.04   86.92  634.54
   93.04  631.96   99.16  628.06  102.22  627.23  108.35  626.66   114.3  625.71
  120.09  624.89  122.98  626.34  128.77  629.19  134.83  630.53  140.89  632.99
  149.98  636.01  171.18   644.9  174.21  645.78  177.24  646.01  195.42  653.29
  204.51  655.86  216.62  660.21  219.65  660.37  222.68  661.35  231.77  665.28
#Mann= 3 , 0 , 0
       0      .1       0   114.3      .1       0  122.98      .1       0
Bank Sta=114.3,122.98
XS Rating Curve= 0 ,0
Exp/Cntr=0.3,0.1

Type RM Length L Ch R = 1 ,365.7599,85.97,91.44,99.61
XS GIS Cut Line= 4
     627430.3395    4317341.8552     627385.2886    4317379.4029
     627351.6495    4317424.7953     627318.2975    4317466.7507
#Sta/Elev= 30
       0  666.35     8.8  661.45   11.73  660.12   14.66  659.59   17.59  658.27
   23.46  654.86   29.32  650.57   46.92  640.25   52.78  636.59   55.71   634.1
   58.65  632.03   61.62   629.2   67.57  626.79   70.54  624.85   76.49   623.5
   80.11  622.46   82.44  621.84   85.41  621.75   88.38  622.72    97.3   626.8
  103.25   630.1  106.22  631.03   109.2  631.67  133.01  644.76  135.99  647.01
  138.97  648.58  144.92  652.89   147.9  654.65  150.88  655.25  168.74  665.13
#Mann= 3 , 0 , 0
       0      .1       0   80.11      .1       0   88.38      .1       0
Bank Sta=80.11,88.38
XS Rating Curve= 0 ,0
Exp/Cntr=0.3,0.1

Type RM Length L Ch R = 1 ,274.32  ,95.05,91.44,82.07
XS GIS Cut Line= 4
     627394.3653    4317296.4248     627319.0353    4317328.6146
      627299.866    4317336.9742     627236.4275    4317374.1152
#Sta/Elev= 30
       0  672.71    18.2  661.53   21.24  658.43   24.27  656.41   33.37  651.16
   39.44  647.34   42.48   644.9   45.51  641.32   63.72  628.85   69.78  623.26
   72.82  622.37   78.89  621.53   84.83  620.25   87.89  619.55   90.88  618.56
   93.87   618.2   96.86  618.78   99.84  620.59  102.83   623.6  112.02  629.05
  115.08   632.1  118.15  634.42  121.21  637.08  139.59  648.95  142.65  651.54
  145.71  654.45  164.09  665.49  167.15  667.88  170.22  671.08  176.34  674.75
#Mann= 3 , 0 , 0
       0      .1       0   90.88      .1       0   96.86      .1       0
Bank Sta=90.88,96.86
XS Rating Curve= 0 ,0
Exp/Cntr=0.3,0.1

Type RM Length L Ch R = 1 ,182.88  ,91.63,91.44,90.82
XS GIS Cut Line= 6
     627344.3777    4317199.4898     627283.3166    4317233.8064
     627270.4654    4317251.2127     627268.3283    4317255.6956
     627265.7518    4317259.1945     627210.2337      4317320.14
#Sta/Elev= 30
       0  674.04   18.27  663.26   21.32  660.33   27.41  656.49   36.54  652.33
   42.64  648.71   45.68  646.53   51.77  640.47   72.75  625.06   75.45  623.52
   80.86  621.38   88.98  617.62   91.68  616.97   94.16   616.8   98.82  616.31
  100.99  616.66  106.17   619.1  111.74  622.63  114.73  625.21  117.72  628.26
  132.65  639.45  135.64  641.25  138.63  642.14   144.6   646.6  150.58  651.43
  153.56  654.64  156.55  657.16  162.53  661.68  180.45   673.7  183.44  675.03
#Mann= 3 , 0 , 0
       0      .1       0   94.16      .1       0  100.99      .1       0
Bank Sta=94.16,100.99
XS Rating Curve= 0 ,0
Exp/Cntr=0.3,0.1

Type RM Length L Ch R = 1 ,91.43999,34.31,91.44,41.69
XS GIS Cut Line= 4
     627321.3589     4317179.646     627223.7357    4317168.4227
     627185.0209    4317212.2993     627177.6899    4317283.6275
#Sta/Elev= 30
       0  665.38   12.28  658.05   15.35  655.15   27.64  648.18   30.71  645.91
   33.78  642.42    52.2  631.56   55.27  628.65   58.35  627.81   64.49  627.69
   67.56  626.82    73.7  623.28   76.77  620.78   92.12  615.29    95.2  614.77
  101.19  614.64  121.67  615.07  145.08  614.99     148  615.76  150.93  617.12
  162.76  623.96  174.71  629.41  180.68  630.99  183.67  632.84  189.65   637.4
   201.6     648  207.57  652.84  210.56   652.9  219.52  659.84  228.49  665.87
#Mann= 3 , 0 , 0
       0      .1       0   92.12      .1       0  145.08      .1       0
Bank Sta=92.12,145.08
XS Rating Curve= 0 ,0
Exp/Cntr=0.3,0.1

River Reach=Dry Fork        ,10
Reach XY= 30
629107.7663977044314578.05615132629090.4433006764314590.41265395
629062.9698756944314604.93291053629000.9423132394314626.82452829
628956.4097349834314665.48759473 628961.378632354314690.23488224
 628974.709590894314732.41067238628977.9340698234314777.29874673
628985.8267540224314813.88372566629003.1682722994314824.16999731
629009.8231474024314870.17860263629021.3835138444314901.96507434
629051.9275105344314919.97074605     629069.5189    4314942.1287
     629074.6436    4314956.0032     629075.6686    4314958.7781
     629076.6935     4314961.553     629078.4416    4314963.8837
     629080.1896    4314966.2145     629081.9377    4314968.5452
     629083.6857     4314970.876     629085.4338    4314973.2067
     629090.6779    4314980.1989     629118.0029    4315002.8802
     629147.3717    4315017.1677     629171.1843    4315021.1365
      629176.556     4315022.332     629184.6135    4315024.1251
     629187.2993    4315024.7229      629192.671    4315025.9183

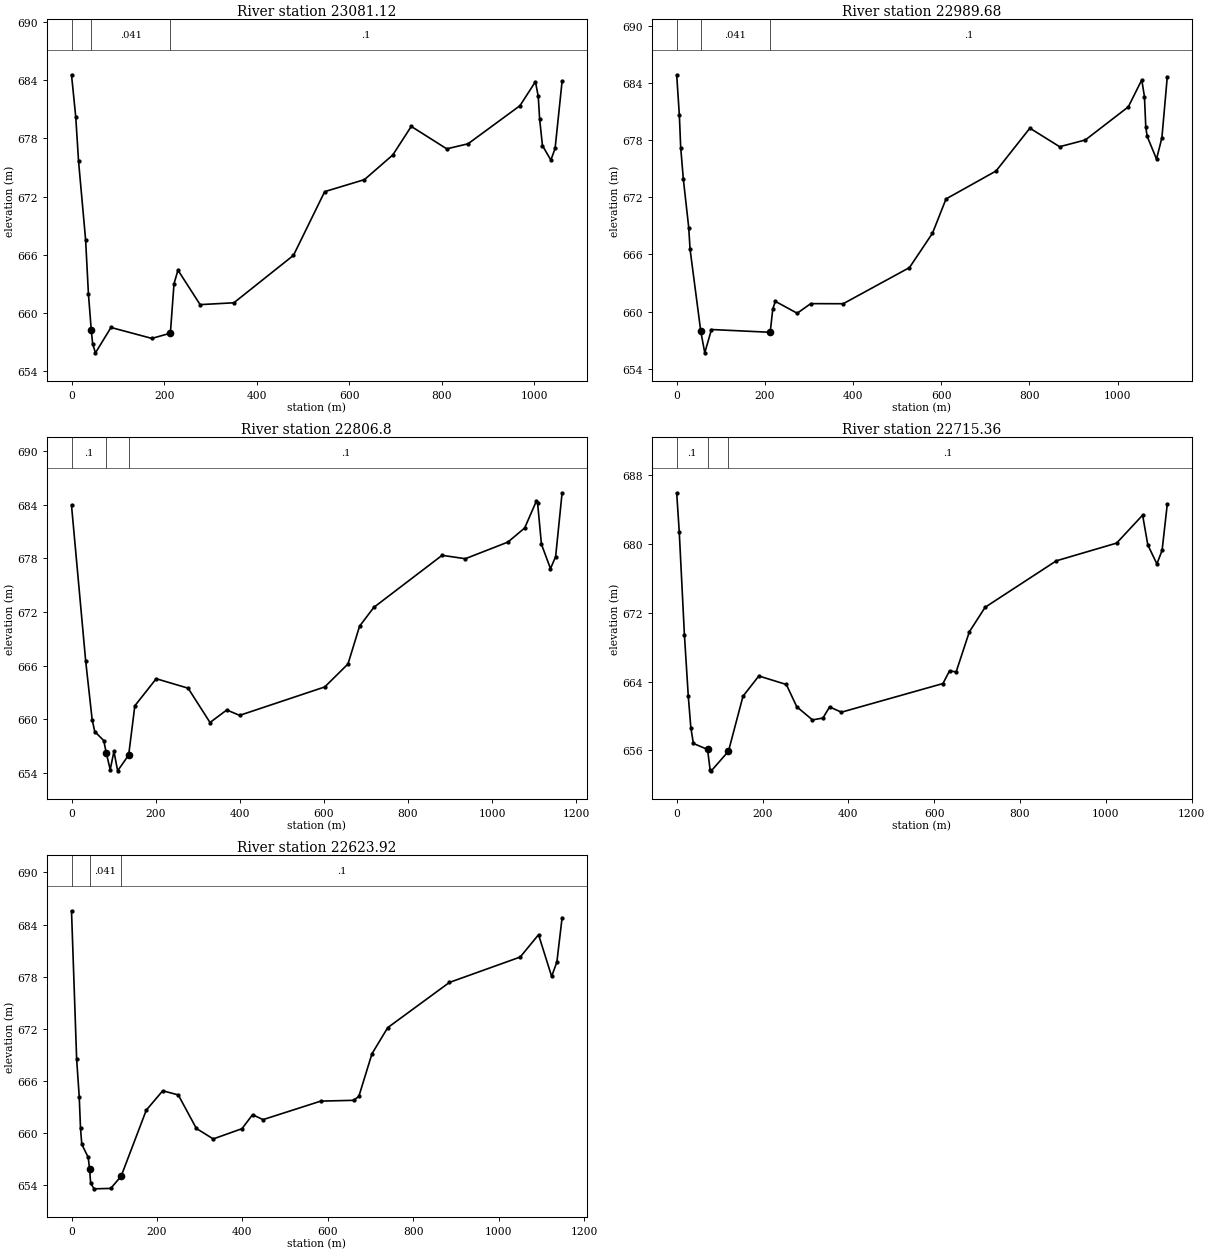
Type RM Length L Ch R = 1 ,23081.12,74.63,91.44,91.9
XS GIS Cut Line= 6
     628904.8743    4314658.3753     629096.1281    4314649.9015
     629120.8942    4314650.2525     629206.8363    4314670.6223
     629436.0189     4314155.202     629583.8111    4314034.2345
#Sta/Elev= 30
       0  684.58    9.14  680.24   15.23  675.64   30.45  667.54   36.54  661.96
   42.63  658.25   45.68  656.78   51.77  655.86   85.26  658.48  173.57  657.35
  213.59  657.89  221.44     663  229.97   664.4  277.84  660.84  350.75  661.03
  479.51  665.93  546.95  672.51  632.79  673.75  694.11   676.3  733.96  679.25
   810.6  676.93  856.58  677.45  968.89  681.39 1002.23  683.87  1008.3  682.34
 1011.33  679.99 1017.39  677.26 1035.58  675.77 1044.68  676.97 1059.83  683.92
#Mann= 3 , 0 , 0
       0      .1       0   42.63    .041       0  213.59      .1       0
Bank Sta=42.63,213.59
XS Rating Curve= 0 ,0
Exp/Cntr=0.3,0.1

Type RM Length L Ch R = 1 ,22989.68,87.26,91.44,107.03
XS GIS Cut Line= 6
     628903.0403    4314711.2804     629096.1327    4314730.6406
     629122.1732    4314744.1089     629170.2162    4314756.0406
      629444.325    4314162.8436     629584.4726    4314040.8491
#Sta/Elev= 30
       0  684.88    6.06  680.63     9.1  677.23   15.16  673.88   27.29  668.83
   30.32  666.55   54.58  657.93   63.68  655.66   78.84  658.11   212.1  657.82
  217.94  660.28  223.78  661.07  273.29  659.82  303.96  660.83  377.59  660.82
  527.92  664.62  580.08  668.23  610.76  671.83  724.27  674.77  800.97  679.27
  868.46  677.32  926.75  678.03 1024.22  681.51 1054.68  684.34 1060.78  682.59
 1063.82  679.38 1066.87  678.42 1088.19  676.02 1100.37  678.27 1112.56  684.67
#Mann= 3 , 0 , 0
       0      .1       0   54.58    .041       0   212.1      .1       0
Bank Sta=54.58,212.1
XS Rating Curve= 0 ,0
Exp/Cntr=0.3,0.1

Type RM Length L Ch R = 1 ,22806.8 ,100.94,91.44,67.83
XS GIS Cut Line= 6
     628956.6131    4314946.6088     629045.9342    4314913.9629
     629139.6175    4314904.2104     629179.2363    4314755.4243
     629459.2542     4314175.699     629586.3952     4314051.159
#Sta/Elev= 30
       0  683.94   33.75  666.49   49.08  659.97   55.22  658.63   76.69  657.61
   82.83  656.19   92.03  654.37  100.92  656.41  109.66  654.23  135.87  655.99
  150.56  661.51  201.39  664.54  277.22  663.48  329.29  659.64  369.13  661.04
  399.79  660.44  602.13  663.62  657.31  666.19   684.9  670.42  718.63  672.52
  881.11  678.35  936.29  677.97 1037.51  679.83  1077.4  681.41 1105.02   684.4
 1108.08  684.23 1117.29  679.59 1138.77  676.86 1151.04  678.21 1166.39  685.35
#Mann= 3 , 0 , 0
       0      .1       0   82.83    .041       0  135.87      .1       0
Bank Sta=82.83,135.87
XS Rating Curve= 0 ,0
Exp/Cntr=0.3,0.1

Type RM Length L Ch R = 1 ,22715.36,98.17,91.44,53.42
XS GIS Cut Line= 6
     629047.7934    4315050.3542     629131.2743    4314959.5217
     629143.1805    4314886.8934     629183.7942    4314752.6436
     629469.9783    4314184.7739     629586.3952    4314061.7424
#Sta/Elev= 30
       0  685.95    5.99  681.39   17.97  669.47   26.96  662.34   32.95  658.65
   38.94   656.8    71.9  656.11   77.89  653.74   80.71  653.62  120.65   655.9
  154.48  662.29  191.35  664.65  255.42  663.66  279.82  661.07  316.41  659.54
  340.82  659.76  356.18  661.05  383.83  660.44  620.38  663.77  635.74  665.25
   651.1  665.12  681.82  669.78  718.68  672.64  884.57  678.04 1025.07   680.1
 1085.57  683.35 1097.67  679.89 1118.84  677.68 1130.94  679.25 1143.04  684.62
#Mann= 3 , 0 , 0
       0      .1       0    71.9    .041       0  120.65      .1       0
Bank Sta=71.9,120.65
XS Rating Curve= 0 ,0
Exp/Cntr=0.3,0.1

Type RM Length L Ch R = 1 ,22623.92,90.43,91.44,75.52
XS GIS Cut Line= 6
     629169.2107    4315080.4848     629185.2379    4315021.2778
     629141.3516    4314944.2916     629186.8141    4314761.1496
     629478.3256    4314192.1326     629587.6211    4314072.0082
#Sta/Elev= 30
       0  685.58   12.05  668.49   18.07   664.2   21.08  660.55    24.1  658.72
   39.15  657.22   42.17  655.93    44.8  654.28    52.7   653.6    91.9  653.65
  116.27  655.06   175.1  662.65  213.62  664.88  250.01   664.4  292.46  660.54
  331.88  659.34   399.3  660.52  423.89  662.13  448.48  661.56  583.72  663.69
  660.57  663.78  672.86  664.24   703.6  669.14  740.48  672.14  884.95  677.34
 1050.73  680.26 1093.63  682.83 1124.28  678.03 1136.53  679.68 1148.79  684.79
#Mann= 3 , 0 , 0
       0      .1       0   42.17    .041       0  116.27      .1       0
Bank Sta=42.17,116.27
XS Rating Curve= 0 ,0
Exp/Cntr=0.3,0.1

River Reach=Dry Fork        ,9
Reach XY= 30
      629192.671    4315025.9183      629388.622     4315062.714
     629643.4665    4315175.1243629782.8694789324315280.47009278
629830.3528657654315366.12171053629844.3874473314315470.49094342
     629800.0797    4315742.4735     629862.5419    4315871.0063
      629901.507    4316211.0081     629850.6356    4316353.8454
     629726.8104     4316441.158     629438.6786    4316494.3394
     629291.8345    4316479.2581      628985.311    4316252.2113
     629004.0731     4316097.834     628936.2338    4316002.2134
     628549.0303    4315865.1935     628490.4642    4315873.8365
     628242.4949    4316025.2322     627751.9564    4315841.8756
     627603.5249    4315710.9066     627469.4494    4315644.8926
     627187.5991    4315679.1565     626522.6485    4315864.7388
     626452.5851    4315861.7194     626244.0373    4315738.5887
     626201.8093     4315739.578     626096.1906     4315770.438
     626035.8655    4315836.3193     626036.5238    4315877.6759

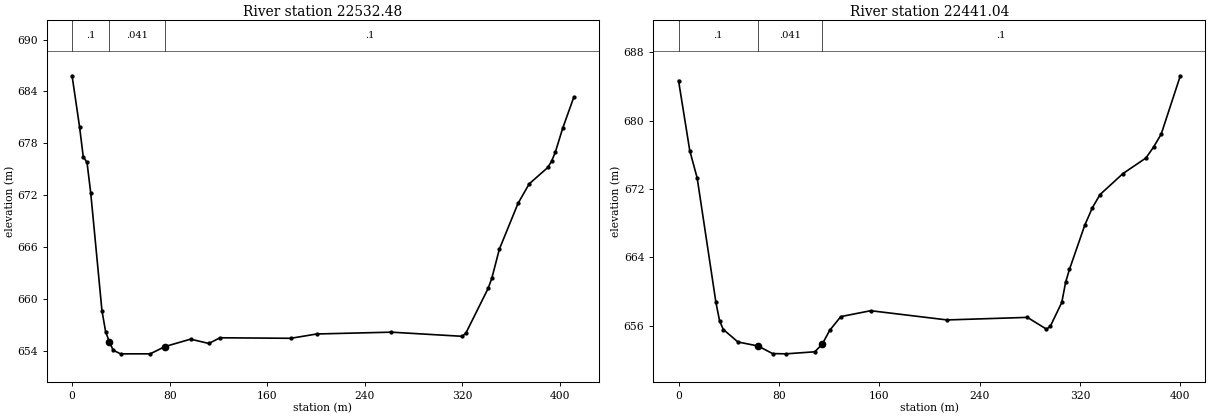
Type RM Length L Ch R = 1 ,22532.48,96.3,91.44,82.62
XS GIS Cut Line= 6
     629260.1986    4315092.3362     629267.7753    4315059.5001
     629275.2051    4315039.6871     629281.6968    4315029.2643
     629284.3426    4314981.3085     629543.8325    4314838.3357
#Sta/Elev= 30
       0  685.82    6.13  679.92    9.19  676.42   12.25  675.79   15.32  672.23
   24.51  658.61   27.57  656.14   30.64     655    33.7  654.04   39.74  653.62
   64.07  653.62   76.14  654.46   97.16  655.32  112.17  654.82  121.28  655.48
  179.31  655.42  200.69  655.92  261.78  656.13  319.81  655.65  322.86  656.01
  341.19  661.21  344.24  662.41  350.35  665.74  365.62  671.03  374.79   673.3
  390.06   675.2  393.11  675.91  396.17  676.94  402.27  679.74  411.44  683.36
#Mann= 3 , 0 , 0
       0      .1       0   30.64    .041       0   76.14      .1       0
Bank Sta=30.64,76.14
XS Rating Curve= 0 ,0
Exp/Cntr=0.3,0.1

Type RM Length L Ch R = 1 ,22441.04,77.96,91.46,113.72
XS GIS Cut Line= 6
     629334.2821    4315141.0196     629356.3591    4315102.2151
     629360.6586    4315084.0249     629362.6429    4315021.1863
     629367.2732    4314991.7513     629557.5908     4314839.394
#Sta/Elev= 30
       0  684.71    8.93  676.52   14.88  673.28   29.76  658.77   32.74  656.55
   35.72  655.56   47.32   654.1   63.34  653.63   74.96  652.74   85.59  652.71
  108.62  652.95  114.52  653.84  120.43  655.45  129.31  657.07  153.15  657.76
  214.03  656.68  278.02  656.98  293.26   655.6  296.31  655.94  305.45  658.73
   308.5  661.09  311.54  662.59  323.73  667.76  329.83  669.82  335.92  671.36
  354.21  673.82  372.49  675.64  378.59  676.92  384.68  678.44  399.92  685.27
#Mann= 3 , 0 , 0
       0      .1       0   63.34    .041       0  114.52      .1       0
Bank Sta=63.34,114.52
XS Rating Curve= 0 ,0
Exp/Cntr=0.3,0.1