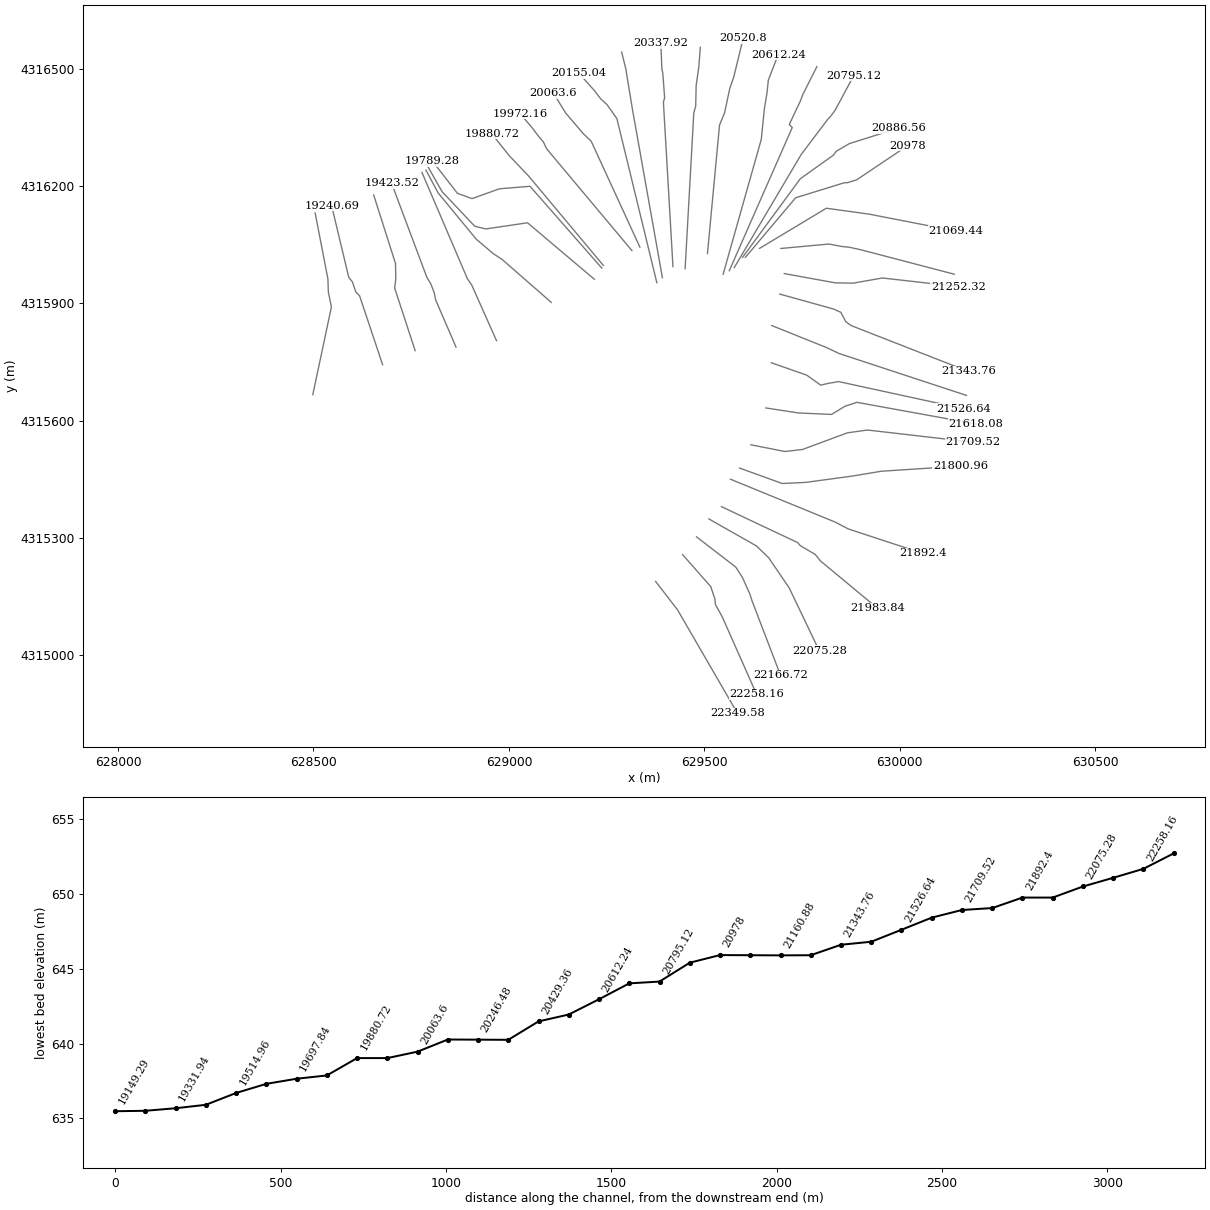
HEC-RAS study RedCreek.prj: RedCreek

--- RedCreek.g01 (geometry) --- (continued)

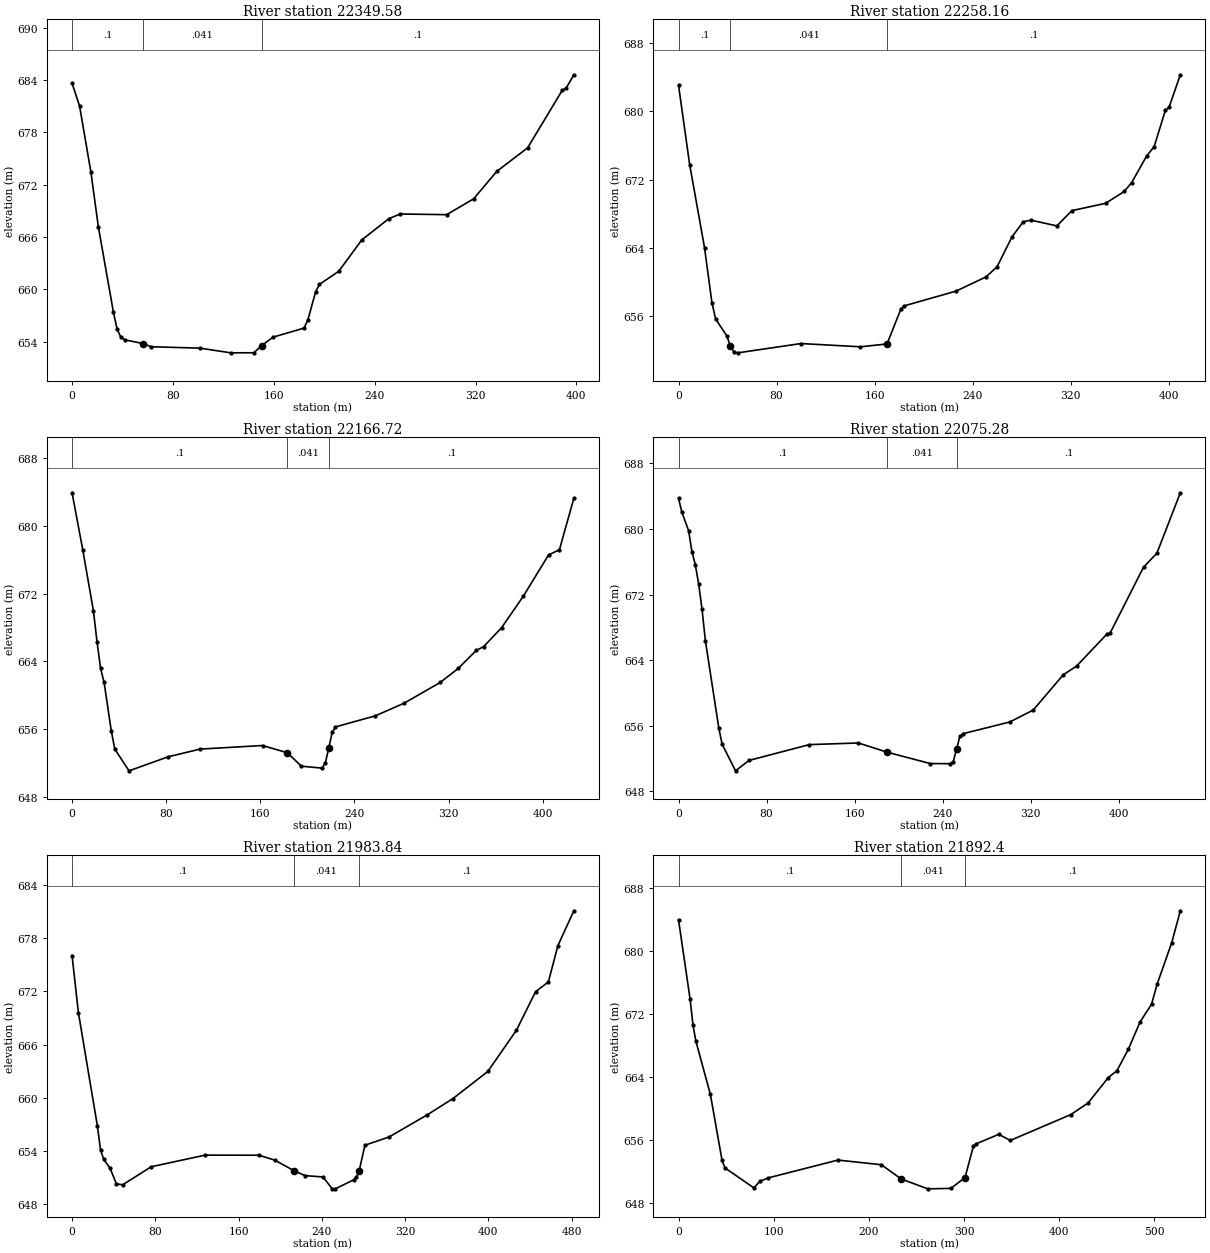
Type RM Length L Ch R = 1 ,22349.58,104.14,91.42,89.23
XS GIS Cut Line= 3
     629375.5571    4315188.6447     629431.8665     4315115.551
     629585.1076    4314851.0357
#Sta/Elev= 30
       0  683.65    5.95  681.03   14.88  673.51   20.83  667.18   32.74  657.41
   35.72  655.42   38.69  654.49   41.67   654.2   56.55  653.76    62.5   653.4
  101.44  653.24   125.9   652.7  144.24  652.71  150.35  653.53  159.52  654.51
  183.98  655.54  187.03  656.49  193.15   659.7  196.21  660.56  211.49  662.06
  229.83  665.67  251.23   668.1   260.4  668.64  297.09  668.56  318.48  670.38
  336.83  673.53  361.28  676.23  388.79  682.84  391.85  683.08  397.97  684.62
#Mann= 3 , 0 , 0
       0      .1       0   56.55    .041       0  150.35      .1       0
Bank Sta=56.55,150.35
XS Rating Curve= 0 ,0
Exp/Cntr=0.3,0.1

Type RM Length L Ch R = 1 ,22258.16,82.83,91.44,85.19
XS GIS Cut Line= 6
     629444.6173    4315257.1206     629516.6183     4315175.387
     629527.3339    4315143.2401     629528.5241    4315129.5273
     629545.9871    4315097.9963     629633.8396    4314899.9867
#Sta/Elev= 30
       0  683.07    9.08  673.76   21.18  664.03   27.23  657.56   30.26  655.64
   39.33  653.68   42.36  652.45   45.39  651.75   48.41  651.67   99.85  652.76
  148.32  652.38  170.07  652.71  181.38  656.82  184.21  657.19  226.26  658.91
  250.66  660.57  259.82  661.77  272.02  665.29  281.17  667.05  287.28  667.25
  308.63  666.57  320.84  668.36   348.3  669.22  363.55  670.61  369.65  671.66
  381.86  674.78  387.96  675.87  397.11  680.13  400.17  680.51  409.32  684.31
#Mann= 3 , 0 , 0
       0      .1       0   42.36    .041       0  170.07      .1       0
Bank Sta=42.36,170.07
XS Rating Curve= 0 ,0
Exp/Cntr=0.3,0.1

Type RM Length L Ch R = 1 ,22166.72,80.82,91.44,102.48
XS GIS Cut Line= 6
     629480.2442    4315302.6804     629580.8328    4315225.0494
     629597.9125    4315198.2463     629616.3738    4315157.1039
     629622.5047    4315138.1336     629695.0007    4314948.9562
#Sta/Elev= 30
       0  683.91    9.08  677.18   18.15  669.97   21.18  666.34    24.2  663.18
   27.23  661.51   33.28  655.83    36.3  653.64    48.4  651.07   81.68  652.73
  108.91  653.64  161.85  654.06  182.89  653.21  194.92  651.62  212.48  651.39
  215.33  652.05  218.18  653.77  221.03   655.6  223.87  656.26  257.64  657.56
   282.2  659.06  312.89  661.51  328.24  663.17  343.59   665.3  349.73  665.73
  365.08  667.98  383.49  671.69  404.98  676.57  414.19  677.18  426.47  683.27
#Mann= 3 , 0 , 0
       0      .1       0  182.89    .041       0  218.18      .1       0
Bank Sta=182.89,218.18
XS Rating Curve= 0 ,0
Exp/Cntr=0.3,0.1

Type RM Length L Ch R = 1 ,22075.28,63.09,91.44,118.08
XS GIS Cut Line= 5
     629511.8523     4315348.495     629633.7098    4315279.3685
     629664.9214     4315249.031     629717.2336    4315172.2502
     629794.5698    4315010.5798
#Sta/Elev= 30
       0  683.74    3.05  682.03    9.14   679.8   12.18  677.24   15.23  675.64
   18.27   673.3   21.32  670.22   24.37  666.38   36.55  655.73   39.59  653.74
   51.78  650.49   63.96  651.76  118.78  653.69  163.31  653.89  189.62  652.76
  228.58  651.38  246.56  651.36  249.56  651.62  252.56  653.19  255.55  654.69
  258.55  655.03  300.83  656.45   322.1   657.9  349.43  662.21  361.58  663.28
  388.92  667.16  391.96  667.29  422.33  675.34  434.48  677.05  455.75  684.42
#Mann= 3 , 0 , 0
       0      .1       0  189.62    .041       0  252.56      .1       0
Bank Sta=189.62,252.56
XS Rating Curve= 0 ,0
Exp/Cntr=0.3,0.1

Type RM Length L Ch R = 1 ,21983.84,82.33,91.44,117.17
XS GIS Cut Line= 6
     629543.8049    4315380.0683     629739.1553    4315287.9013
     629745.9284    4315280.0481     629783.9359    4315257.6659
     629797.6284    4315240.8054     629943.7951    4315119.5883
#Sta/Elev= 30
       0  676.04    6.08  669.62   24.34  656.83   27.38  654.13   30.42  653.07
   36.51  652.07   42.59  650.31   48.68  650.21   76.06  652.24  127.78  653.55
  179.49  653.54  194.71  652.99  212.96  651.81  223.78  651.24  241.07  651.09
   249.9  649.76  252.84  649.75  270.48  650.76   273.2  651.05  275.91  651.81
  281.34  654.67  304.45  655.59   341.2  658.09  365.71  659.91   399.4  662.98
  426.96  667.64  445.34  671.98  457.59  673.08  466.78  677.18  482.09   681.1
#Mann= 3 , 0 , 0
       0      .1       0  212.96    .041       0  275.91      .1       0
Bank Sta=212.96,275.91
XS Rating Curve= 0 ,0
Exp/Cntr=0.3,0.1

Type RM Length L Ch R = 1 ,21892.4 ,56.87,91.44,146.04
XS GIS Cut Line= 4
      629567.041    4315450.1333     629834.7873     4315340.601
     629868.6035    4315322.9416     630058.4657    4315260.5057
#Sta/Elev= 30
       0  683.99   12.18  673.86   15.23  670.57   18.27  668.52    33.5  661.76
   45.68  653.39   48.72  652.42   79.17  649.87   85.26  650.69    94.4  651.15
  167.48  653.41  213.16  652.82  233.86  651.01  261.88  649.75  286.24  649.81
  301.02  651.18  309.83  655.16  312.76  655.48  336.52  656.69  348.63  655.91
  412.23   659.2  430.39  660.68  451.59  663.91  460.68  664.79  472.79  667.54
   484.9  670.97  497.02  673.24  503.07  675.85  518.21  681.06   527.3  685.14
#Mann= 3 , 0 , 0
       0      .1       0  233.86    .041       0  301.02      .1       0
Bank Sta=233.86,301.02
XS Rating Curve= 0 ,0
Exp/Cntr=0.3,0.1

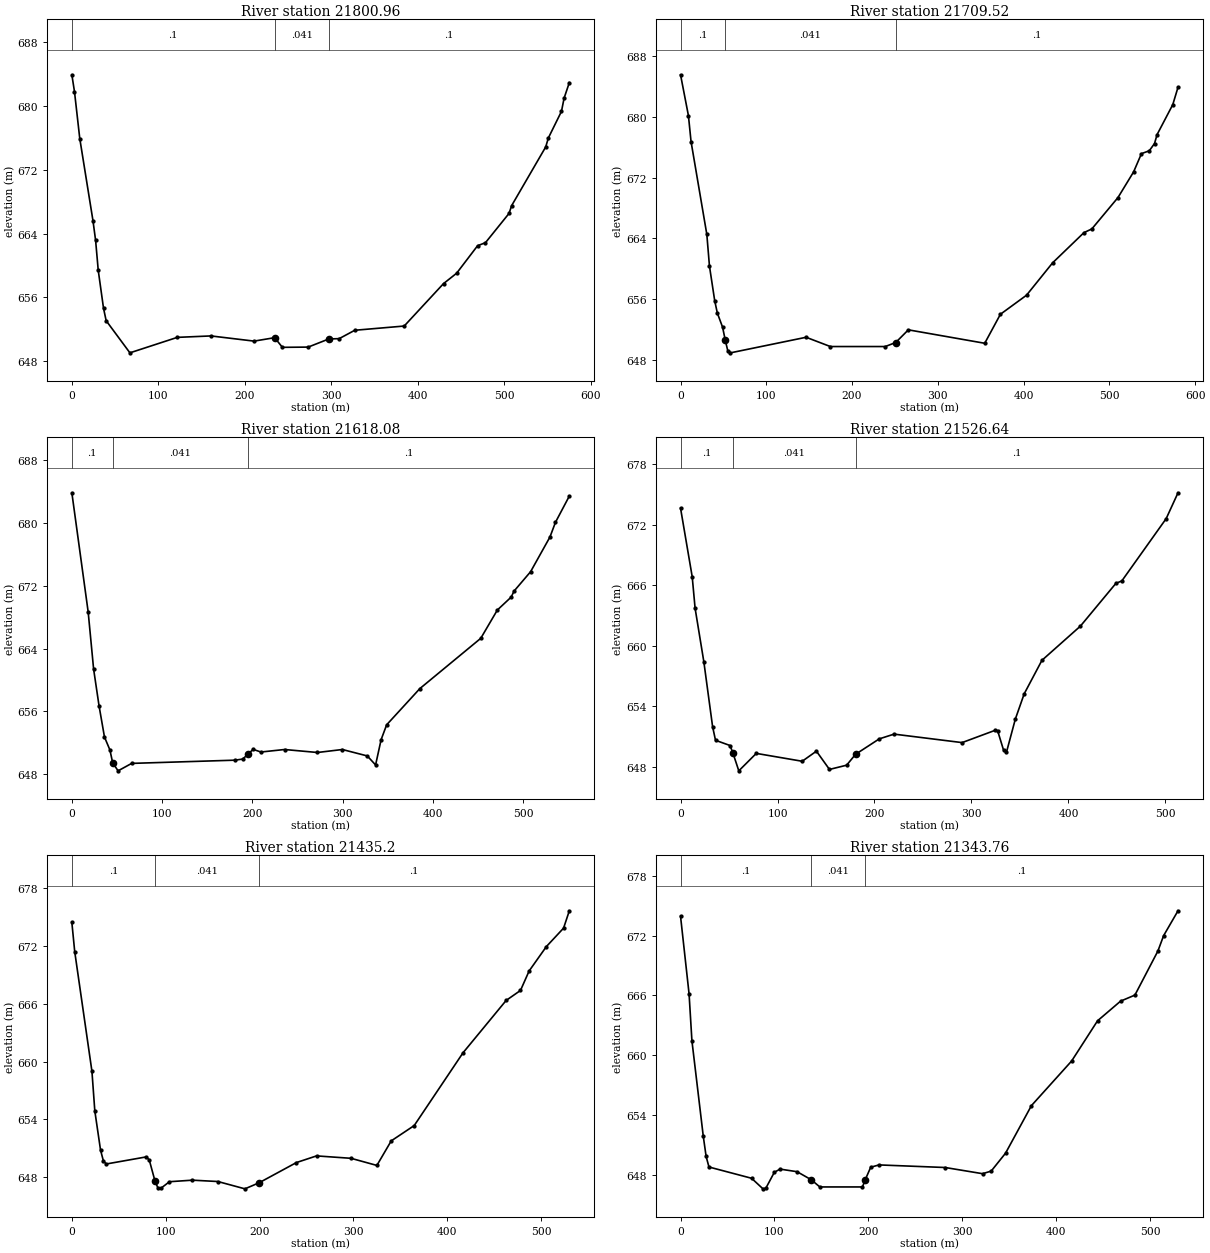
Type RM Length L Ch R = 1 ,21800.96,82.83,91.44,114.37
XS GIS Cut Line= 6
     629590.2881    4315478.7503     629699.2914    4315439.2477
     629758.9778    4315442.0154     629876.2504    4315457.8899
     629953.2519     4315470.597     630155.8326    4315483.8145
#Sta/Elev= 30
       0  683.91    3.05  681.79    9.15  675.92   24.41  665.62   27.46  663.15
   30.51  659.39   36.61  654.64   39.66  653.08   67.12  649.05  121.92  650.99
  160.75  651.17  210.62  650.52  234.46  650.95   243.4  649.74   273.2  649.77
  297.06  650.79  309.06  650.83  327.07  651.88  384.22  652.41  429.67  657.73
  444.82  659.03  469.06  662.48  478.15  662.86  505.42  666.53  508.45  667.51
  547.84  674.87  550.87  675.99  566.02  679.32  569.05  680.97  575.11  682.93
#Mann= 3 , 0 , 0
       0      .1       0  234.46    .041       0  297.06      .1       0
Bank Sta=234.46,297.06
XS Rating Curve= 0 ,0
Exp/Cntr=0.3,0.1

Type RM Length L Ch R = 1 ,21709.52,100.4,91.44,69.27
XS GIS Cut Line= 6
     629619.1766    4315538.2777       629706.38    4315521.0923
       629751.69     4315526.384     629866.3767    4315568.9371
     629917.6502    4315576.0596     630186.9476    4315544.9863
#Sta/Elev= 30
       0  685.55    9.19  680.17   12.26  676.74   30.65  664.52   33.71  660.35
   39.84  655.78   42.91  654.16   49.04  652.29    52.1  650.61   55.17  649.15
   58.23  648.92  146.41  650.97  174.68  649.75   238.7  649.75  250.89  650.28
  265.63  651.95   354.7  650.18  372.98     654  403.43  656.51  433.89  660.78
  470.44  664.76  479.58  665.24  510.04  669.37  528.32  672.76  537.45  675.16
  546.59  675.54  552.68  676.49  555.73  677.68     574  681.62   580.1  683.91
#Mann= 3 , 0 , 0
       0      .1       0    52.1    .041       0  250.89      .1       0
Bank Sta=52.1,250.89
XS Rating Curve= 0 ,0
Exp/Cntr=0.3,0.1

Type RM Length L Ch R = 1 ,21618.08,102.38,91.44,65.57
XS GIS Cut Line= 6
     629657.5723    4315632.5347     629740.9785    4315619.7225
     629825.6409    4315615.9598     629860.1562    4315636.9889
     629890.5833    4315646.9108     630195.4143     4315591.553
#Sta/Elev= 30
       0  683.87   18.08  668.68   24.11  661.39   30.14   656.7   36.16  652.72
   42.19  651.07   45.21  649.45   51.23  648.41    66.3  649.36  180.68  649.77
  189.34  649.91  195.11  650.52  200.89  651.15  209.55  650.81  235.73  651.13
  272.23  650.75  299.83  651.13  327.44  650.31  336.64  649.16  342.78  652.39
  348.91  654.28  385.72   658.9  453.21  665.31  471.61  668.92  486.95  670.57
  490.02  671.32  508.42   673.8   529.9  678.23  536.03  680.11  551.37  683.45
#Mann= 3 , 0 , 0
       0      .1       0   45.21    .041       0  195.11      .1       0
Bank Sta=45.21,195.11
XS Rating Curve= 0 ,0
Exp/Cntr=0.3,0.1

Type RM Length L Ch R = 1 ,21526.64,85.12,91.44,69
XS GIS Cut Line= 6
     629671.5383    4315748.1867      629762.258     4315716.413
     629798.0891    4315690.9061     629816.4337    4315695.2635
     629843.6858     4315700.026     630162.6059    4315630.7115
#Sta/Elev= 30
       0  673.64   12.02  666.85   15.02  663.71   24.03  658.41   33.04  651.99
   36.05  650.63   51.07  650.11   54.07  649.35   60.08   647.6    78.1  649.33
  125.44  648.55  140.11  649.55  153.57  647.74  171.26  648.16  180.48  649.24
  204.93  650.77  220.18  651.24  290.33   650.4  323.88   651.6  326.93  651.59
  333.03  649.67  336.08  649.44  345.23  652.73  354.38  655.24  372.68  658.56
  412.34  661.95  448.94  666.19  455.04  666.43  500.79  672.61  512.99  675.17
#Mann= 3 , 0 , 0
       0      .1       0   54.07    .041       0  180.48      .1       0
Bank Sta=54.07,180.48
XS Rating Curve= 0 ,0
Exp/Cntr=0.3,0.1

Type RM Length L Ch R = 1 ,21435.2 ,96.74,91.44,77.16
XS GIS Cut Line= 4
     629672.5966    4315843.4369     629811.6071    4315787.5861
      629845.488    4315771.6421     630171.0726    4315664.5782
#Sta/Elev= 30
       0  674.46    3.06  671.42    21.4     659   24.46  654.89   30.57  650.82
   33.63  649.69   36.69  649.38   79.49  650.12   82.55  649.77   88.66  647.58
   91.72  646.89   94.78  646.85  103.95  647.54  128.41   647.7  155.57  647.56
  184.38   646.8   199.5  647.43  239.28  649.53   260.7  650.22  297.42  649.97
  324.96  649.23  340.26  651.78  364.74  653.37  416.77  660.93  462.67  666.36
  477.97   667.4  487.15  669.42  505.51  671.95  523.87  673.87  529.99  675.67
#Mann= 3 , 0 , 0
       0      .1       0   88.66    .041       0   199.5      .1       0
Bank Sta=88.66,199.5
XS Rating Curve= 0 ,0
Exp/Cntr=0.3,0.1

Type RM Length L Ch R = 1 ,21343.76,65.45,91.44,124.05
XS GIS Cut Line= 6
     629693.0578    4315923.9365     629830.0597    4315885.8961
     629849.4363    4315877.3359     629862.1215    4315853.1187
     629876.4942    4315843.0336     630175.6587    4315726.0278
#Sta/Elev= 30
       0  673.94    9.08  666.16    12.1  661.46    24.2  651.87   27.23  649.85
   30.25  648.79   75.63  647.66   87.73   646.6   90.76  646.66   99.83  648.26
  105.88  648.58  124.03  648.32  139.16  647.51  148.24  646.79  193.63  646.79
  196.56  647.51  202.41  648.77  211.32     649  281.69  648.74  321.46  648.12
  330.64  648.38  345.94  650.18  373.47  654.95   416.3  659.43  443.84  663.46
  468.31  665.43  483.61  666.04  508.08  670.46   514.2  672.01   529.5   674.5
#Mann= 3 , 0 , 0
       0      .1       0  139.16    .041       0  196.56      .1       0
Bank Sta=139.16,196.56
XS Rating Curve= 0 ,0
Exp/Cntr=0.3,0.1

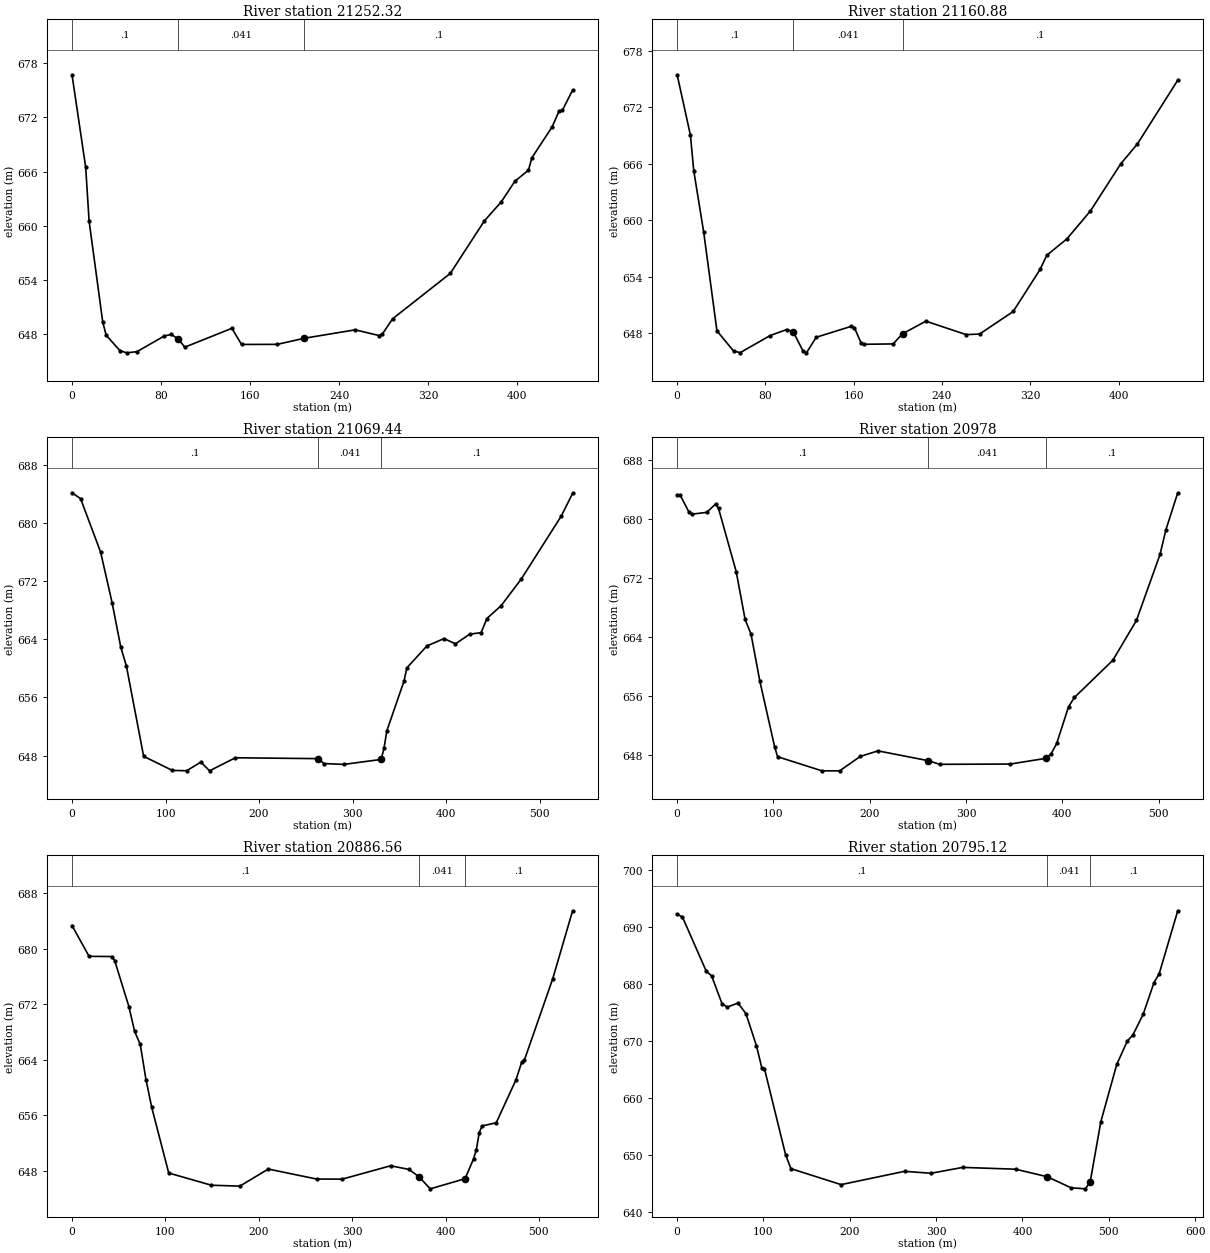
Type RM Length L Ch R = 1 ,21252.32,94.81,91.44,82.3
XS GIS Cut Line= 5
     629704.6995    4315976.3241     629834.6754    4315952.7408
     629880.9356    4315951.8591     629955.8911    4315965.0945
     630149.9941    4315942.9866
#Sta/Elev= 30
       0  676.73   12.29  666.47   15.36  660.51   27.65  649.28   30.72  647.85
   43.01  646.15   49.15   645.9   58.37  646.03   82.95  647.77   89.09  647.94
   95.23  647.46  101.38  646.53  143.67  648.62  152.34  646.83  184.46  646.84
  208.81  647.52  254.48  648.45  275.85  647.82   278.9  647.99  288.06  649.67
  339.95  654.71  370.48  660.52  385.74  662.64  397.95  664.92  410.16  666.15
  413.21  667.52  431.52  670.97  437.63   672.7  440.68   672.8  449.84  675.02
#Mann= 3 , 0 , 0
       0      .1       0   95.23    .041       0  208.81      .1       0
Bank Sta=95.23,208.81
XS Rating Curve= 0 ,0
Exp/Cntr=0.3,0.1

Type RM Length L Ch R = 1 ,21160.88,91.22,91.44,94.24
XS GIS Cut Line= 6
     629695.9682     4316040.618     629818.6385    4316051.9644
      629852.373    4316045.6144       629870.52    4316043.9302
     629901.1591    4316037.1463     630139.6753    4315974.7366
#Sta/Elev= 30
       0  675.48   12.02  669.05   15.02  665.28   24.04  658.74   36.06  648.23
   51.08  646.09   57.09  645.91   84.13  647.72   99.16  648.37  105.17  648.14
  114.18  646.05  117.18  645.89  126.05  647.55  157.52   648.7  160.56  648.58
  166.63  646.96  169.67   646.8  195.72  646.84  204.27  647.92  225.39  649.26
  261.92  647.83  274.09  647.89  304.53  650.29  328.88  654.76  334.97  656.27
  353.23  658.02  374.53  660.99  401.93  665.99  417.15  668.13  453.67   674.9
#Mann= 3 , 0 , 0
       0      .1       0  105.17    .041       0  204.27      .1       0
Bank Sta=105.17,204.27
XS Rating Curve= 0 ,0
Exp/Cntr=0.3,0.1

Type RM Length L Ch R = 1 ,21069.44,71.96,91.44,118.62
XS GIS Cut Line= 4
     629641.6756    4316040.9355      629812.359    4316143.5652
     629921.3379    4316128.5336     630143.3266    4316085.3856
#Sta/Elev= 30
       0  684.19    9.19  683.38   30.64     676    42.9  669.04   52.09  662.97
   58.22  660.29    76.6   647.9  107.24  645.96  122.56  645.91  137.88  647.11
  147.07   645.9  174.65   647.7  263.34  647.58  269.45   646.9  290.84  646.79
  330.56  647.47  333.62  648.99  336.68  651.42  355.01  658.25  358.07  660.08
  379.46  663.09   397.8  664.11  410.02  663.39   425.3  664.72  437.52  664.93
  443.64  666.87  458.92  668.65  480.31  672.29  523.09  680.96  535.32  684.11
#Mann= 3 , 0 , 0
       0      .1       0  263.34    .041       0  330.56      .1       0
Bank Sta=263.34,330.56
XS Rating Curve= 0 ,0
Exp/Cntr=0.3,0.1

Type RM Length L Ch R = 1 ,20978   ,83.37,91.44,84.28
XS GIS Cut Line= 6
      629605.163    4316017.9167     629733.7508     4316170.317
      629859.283    4316209.0517     629866.0299    4316208.7871
     629889.9257    4316216.2751     630020.2951    4316303.6673
#Sta/Elev= 30
       0  683.23    3.07  683.22   12.27   680.9   15.34  680.63   30.68  680.87
   39.88  681.99   42.95  681.41   61.35  672.84   70.56  666.39   76.69  664.42
    85.9  658.02  101.23  649.16   104.3  647.82  150.32  645.91  168.72  645.91
   190.2  647.86  208.57  648.61   260.5  647.29  272.72  646.79  345.94  646.83
  382.92   647.6  388.37  648.21  394.17  649.62  406.43  654.57  412.57  655.84
  452.43  660.86  476.95  666.25  501.48  675.19  507.62  678.54  519.88  683.52
#Mann= 3 , 0 , 0
       0      .1       0   260.5    .041       0  382.92      .1       0
Bank Sta=260.5,382.92
XS Rating Curve= 0 ,0
Exp/Cntr=0.3,0.1

Type RM Length L Ch R = 1 ,20886.56,84.3,91.44,103.36
XS GIS Cut Line= 6
     629598.0192    4316017.9167        629745.9    4316219.2117
     629830.3023    4316279.2723     629837.6307     4316289.276
      629871.033    4316308.8538     629996.3503    4316348.3819
#Sta/Elev= 30
       0  683.32   18.28  678.89   42.64  678.86   45.69  678.28   60.92  671.65
   67.01  668.09   73.11  666.19    79.2  661.14   85.29  657.18  103.57  647.68
  149.26  645.92  179.72  645.79  210.18  648.25  261.96  646.81  289.39   646.8
  341.18  648.72  360.81   648.2  371.72  647.13  383.64   645.4  420.94  646.86
  430.03  649.72  433.06  651.04  436.09  653.48  439.13  654.46  454.28  654.91
  475.49  661.11  481.56  663.64  484.59  663.99   514.9  675.69  536.11  685.45
#Mann= 3 , 0 , 0
       0      .1       0  371.72    .041       0  420.94      .1       0
Bank Sta=371.72,420.94
XS Rating Curve= 0 ,0
Exp/Cntr=0.3,0.1

Type RM Length L Ch R = 1 ,20795.12,104.82,91.44,93.61
XS GIS Cut Line= 6
     629576.6541    4315991.5796     629748.3213    4316281.5821
     629816.5963    4316371.9428     629822.7649    4316378.2297
     629834.5122    4316393.7281      629882.513    4316483.0551
#Sta/Elev= 30
       0  692.29    6.13  691.78    33.7  682.29   39.83  681.49   52.08  676.56
   58.21  676.01   70.46  676.71   79.66  674.85   91.91   669.2   98.04  665.35
   101.1  665.22  125.61  650.12  131.74  647.68  189.95  644.88  263.48  647.21
  294.11  646.87  330.88   647.9   392.1  647.58  428.83  646.26  456.13  644.33
  472.96  644.14  478.51  645.39   490.8   655.9  509.24  665.94  521.53  670.07
  527.68  671.04  539.97  674.77  552.26  680.24  558.41  681.84  579.92  692.88
#Mann= 3 , 0 , 0
       0      .1       0  428.83    .041       0  478.51      .1       0
Bank Sta=428.83,478.51
XS Rating Curve= 0 ,0
Exp/Cntr=0.3,0.1

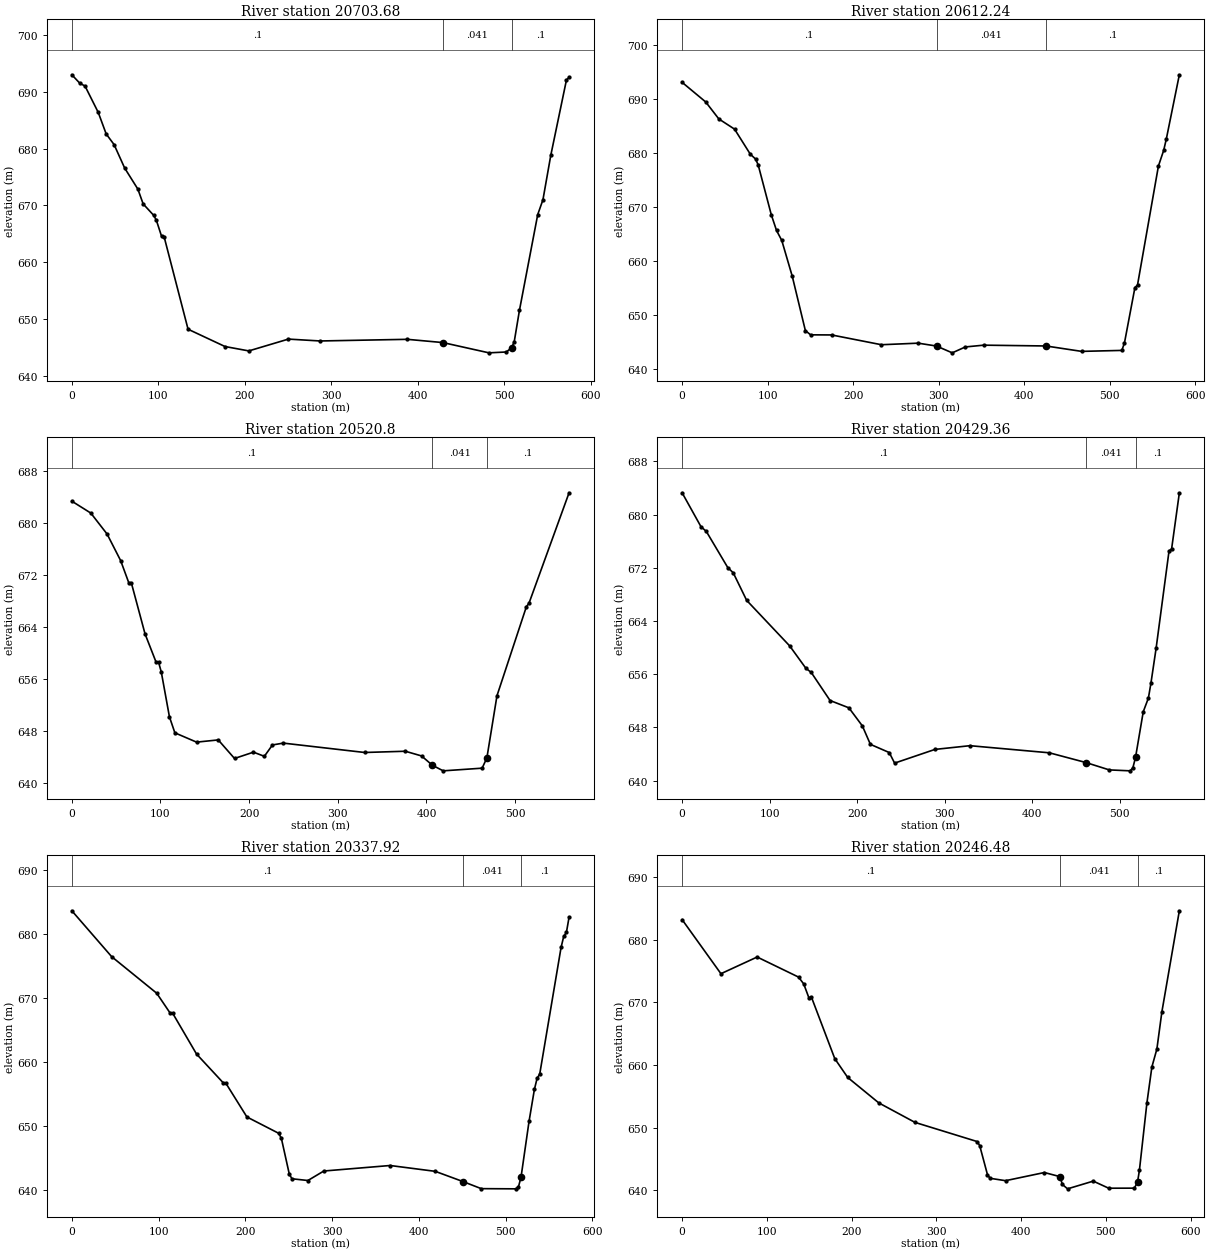
Type RM Length L Ch R = 1 ,20703.68,73.42,91.44,100.3
XS GIS Cut Line= 6
     629564.1194    4315983.8405     629725.1561    4316350.1102
     629717.5244    4316357.9389     629745.7407    4316417.6055
     629752.7089    4316435.6861      629788.103    4316505.7936
#Sta/Elev= 30
       0  692.99    9.16  691.51   15.27     691   30.54  686.36   39.71  682.57
   48.87  680.69   61.09  676.56   76.36  672.85   82.46  670.25   94.68  668.23
   97.74  667.37  103.84  664.51   106.9  664.35  134.39  648.18  177.15  645.13
  204.64  644.36  250.45  646.44   287.1  646.11  387.89   646.4  429.04  645.83
  482.37  644.02   502.5  644.17  508.54  644.94  511.56  645.95  517.61   651.5
  538.75  668.37  544.79  670.98  553.85   678.8  571.98  692.08     575  692.52
#Mann= 3 , 0 , 0
       0      .1       0  429.04    .041       0  508.54      .1       0
Bank Sta=429.04,508.54
XS Rating Curve= 0 ,0
Exp/Cntr=0.3,0.1

Type RM Length L Ch R = 1 ,20612.24,107.54,91.44,89.71
XS GIS Cut Line= 6
     629548.2444    4315974.5801     629645.8889    4316319.9403
     629653.8066    4316398.2644     629660.5727    4316439.2237
     629663.9177    4316471.1867     629689.1353    4316536.8208
#Sta/Elev= 30
       0     693   27.61  689.37   42.95  686.23   61.35  684.34   79.76  679.71
   85.89  678.82   88.96  677.74   104.3  668.51  110.43   665.6  116.57  663.75
  128.84  657.12  144.17  647.07  150.31  646.29  174.85  646.27  233.13  644.46
  276.08  644.75  297.55  644.22  315.95  642.96  331.29  644.05  352.76  644.38
  425.51  644.23  467.28  643.23  514.33  643.41  517.39  644.79  529.62  655.03
  532.67  655.52  557.13  677.53  563.24   680.4   566.3  682.48  581.59   694.4
#Mann= 3 , 0 , 0
       0      .1       0  297.55    .041       0  425.51      .1       0
Bank Sta=297.55,425.51
XS Rating Curve= 0 ,0
Exp/Cntr=0.3,0.1

Type RM Length L Ch R = 1 ,20520.8 ,74.06,91.44,94.92
XS GIS Cut Line= 6
       629508.16    4316027.6291     629539.0396     4316356.482
     629551.9381    4316387.5706     629565.2279    4316450.2605
     629575.0218    4316477.8341     629599.5807    4316578.3042
#Sta/Elev= 30
       0  683.37   21.41  681.54   39.76  678.32   55.05  674.24   64.22  670.84
   67.28  670.74   82.57  662.98   94.81  658.71   97.87  658.62  100.92  657.11
   110.1  650.23  116.22  647.78  140.68  646.35  165.15  646.69   183.5  643.84
  204.91  644.81  217.14  644.17  226.32  645.92  238.55   646.2   330.3  644.76
  376.16  644.95  394.47  644.23  406.68   642.8  418.89  641.94  462.79  642.35
  468.16  643.92  479.55  653.48  512.68  667.14  515.69   667.7  560.87  684.66
#Mann= 3 , 0 , 0
       0      .1       0  406.68    .041       0  468.16      .1       0
Bank Sta=406.68,468.16
XS Rating Curve= 0 ,0
Exp/Cntr=0.3,0.1

Type RM Length L Ch R = 1 ,20429.36,82.32,91.44,96.34
XS GIS Cut Line= 6
     629451.0098    4315988.9999     629473.2349    4316387.9924
     629477.9974    4316404.3966     629479.2856    4316458.3512
     629486.0477    4316505.3253     629489.8612    4316555.2701
#Sta/Elev= 30
       0  683.27   21.52  678.18   27.67  677.46   52.26  672.01    58.4  671.25
   73.77   667.1  122.96  660.25   141.4   656.9  147.55  656.27  169.07  652.05
  190.58  650.95  205.95  648.24  215.18  645.46  236.69  644.23  242.84  642.64
  288.95   644.7  328.91  645.26  419.69  644.19  461.67  642.72  488.18  641.62
  512.13  641.48  515.14  641.94  518.14  643.49  526.98  650.36  532.87  652.42
  535.82   654.7  541.71  659.93  556.44  674.52  559.39  674.83  568.23  683.25
#Mann= 3 , 0 , 0
       0      .1       0  461.67    .041       0  518.14      .1       0
Bank Sta=461.67,518.14
XS Rating Curve= 0 ,0
Exp/Cntr=0.3,0.1

Type RM Length L Ch R = 1 ,20337.92,84.27,91.44,93.81
XS GIS Cut Line= 6
     629419.8771    4315994.2034     629395.4143     4316415.351
     629398.5893    4316425.9344     629393.8893    4316488.6529
     629391.4793    4316501.1338     629388.8449    4316565.6258
#Sta/Elev= 30
       0  683.62   45.85  676.47   97.82  670.76  113.11   667.7  116.16  667.65
  143.68  661.28  174.25  656.82   177.3  656.77  201.76  651.46  238.44  648.91
   241.5  648.12  250.67  642.52  253.73  641.82  272.07  641.55  290.41  643.03
  366.83  643.89   418.8  642.98  450.88  641.38  471.86  640.28  511.59  640.25
  514.66  640.52  517.74  642.11  526.96   650.8  533.11  655.76  536.18  657.47
  539.25  658.16  563.84   677.9  566.91  679.63  569.99  680.24  573.06  682.62
#Mann= 3 , 0 , 0
       0      .1       0  450.88    .041       0  517.74      .1       0
Bank Sta=450.88,517.74
XS Rating Curve= 0 ,0
Exp/Cntr=0.3,0.1

Type RM Length L Ch R = 1 ,20246.48,53.92,91.44,99.54
XS GIS Cut Line= 5
     629392.8896    4315965.6283       629316.91    4316392.4732
      629301.058    4316488.2429     629300.0617    4316497.1386
     629288.6357      4316542.85
#Sta/Elev= 30
       0  683.17    45.8  674.55   88.54  677.21  137.39  674.01   143.5  672.92
  149.61   670.7  152.66  670.79  180.14  661.01   195.4  658.01  232.04  653.96
  274.79  650.85  348.06   647.8  351.12  647.16  360.28  642.53  363.33  641.94
  381.65  641.56  427.45  642.86  445.69  642.21  448.72  640.96  454.79  640.26
  485.12  641.49  503.33  640.36  533.61  640.37  537.36  641.33  539.58  643.21
  548.41  653.93   554.3  659.69  560.19  662.54  566.08  668.46   586.7  684.58
#Mann= 3 , 0 , 0
       0      .1       0  445.69    .041       0  537.36      .1       0
Bank Sta=445.69,537.36
XS Rating Curve= 0 ,0
Exp/Cntr=0.3,0.1

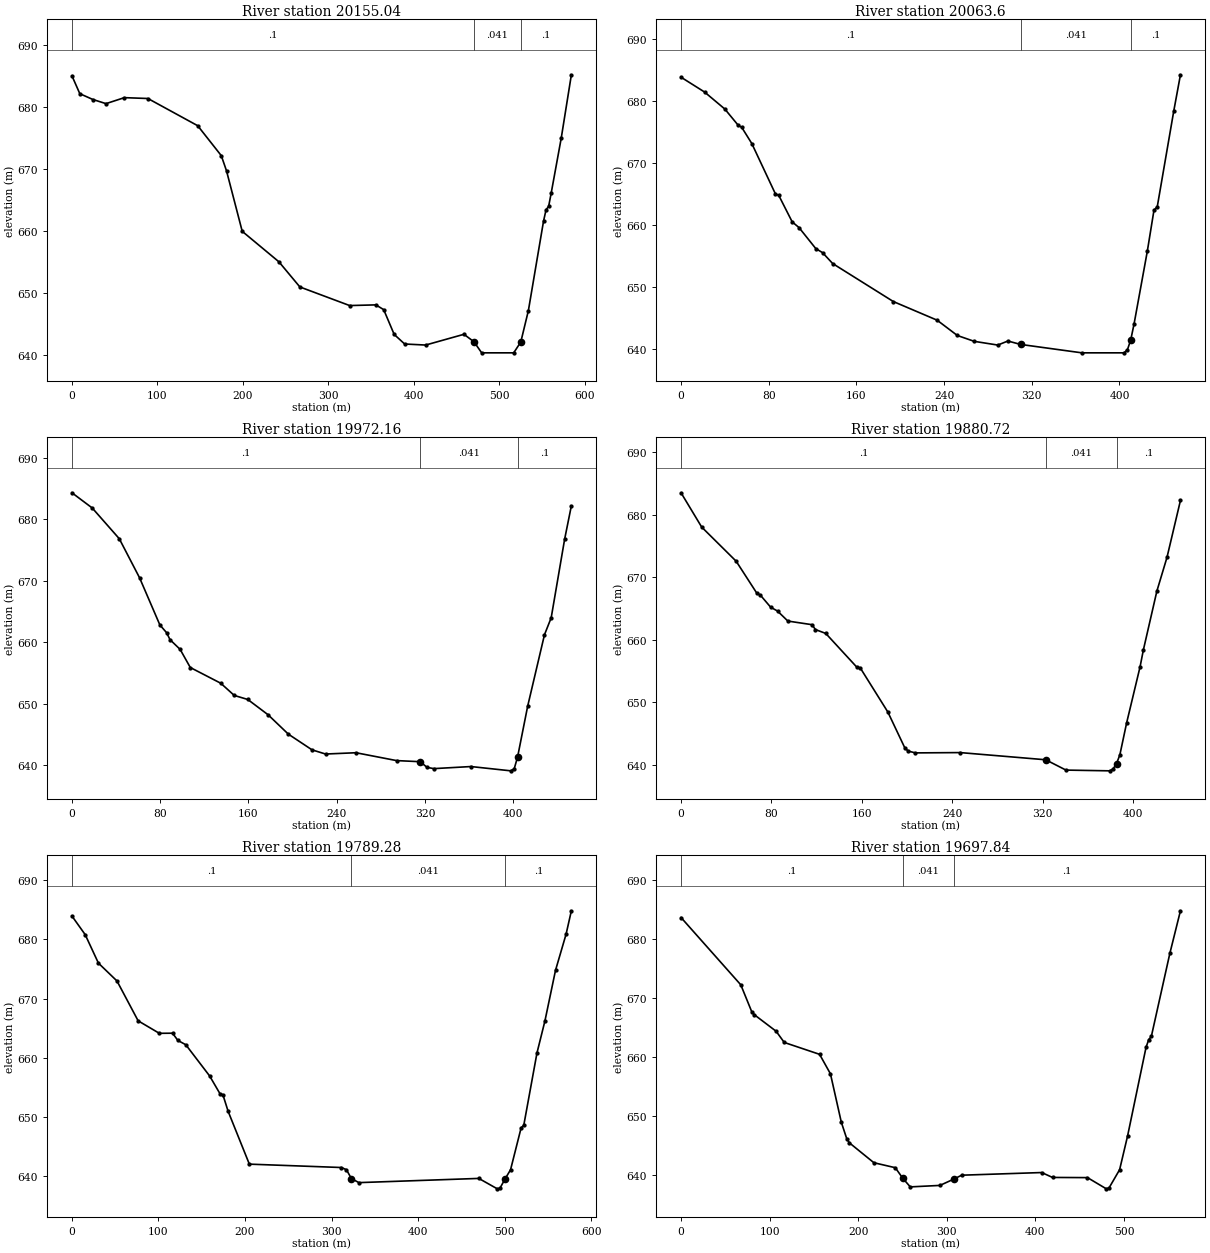
Type RM Length L Ch R = 1 ,20155.04,91.51,91.44,92.37
XS GIS Cut Line= 6
      629378.655    4315952.9812     629276.3872    4316372.9142
     629250.9211    4316408.9638     629235.0046    4316423.4053
     629218.5095    4316445.0133     629179.0932     4316489.139
#Sta/Elev= 30
       0  685.09     9.2   682.2   24.52  681.26   39.85  680.59   61.31  681.56
   88.89  681.42  147.13  677.02  174.72  672.18  180.85  669.72  199.24  659.93
  242.16     655  266.68  650.93  324.92  647.92  355.57  648.03  364.77  647.26
  377.03  643.25  389.29   641.7  413.81  641.53  458.69  643.27  470.46  642.05
  479.41  640.27   516.9  640.27  525.19  642.03  534.07  647.11  551.82   661.6
  554.78  663.44  557.74  663.95  560.69  666.07  572.53  675.03  584.36  685.26
#Mann= 3 , 0 , 0
       0      .1       0  470.46    .041       0  525.19      .1       0
Bank Sta=470.46,525.19
XS Rating Curve= 0 ,0
Exp/Cntr=0.3,0.1

Type RM Length L Ch R = 1 ,20063.6 ,97.68,91.44,93.3
XS GIS Cut Line= 5
     629335.2632    4316043.9981     629210.6823    4316314.9307
      629189.655    4316335.2355     629145.6471    4316386.7874
     629113.9388     4316438.228
#Sta/Elev= 30
       0  683.78   21.52  681.39   39.97  678.66   52.26  676.03   55.34  675.73
   64.56  673.12   86.08  665.03   89.15  664.78  101.45  660.51   107.6  659.61
  122.97  656.22  129.12  655.57  138.34  653.82  193.68  647.71  233.64  644.71
  252.09  642.25  267.46  641.31  288.98  640.71   298.2  641.36  309.89  640.81
  365.74  639.46  404.28  639.46   407.3  639.97  410.32  641.56  413.34  644.12
  425.43  655.81  431.47  662.38  434.49  662.95   449.6   678.4  455.64  684.17
#Mann= 3 , 0 , 0
       0      .1       0  309.89    .041       0  410.32      .1       0
Bank Sta=309.89,410.32
XS Rating Curve= 0 ,0
Exp/Cntr=0.3,0.1

Type RM Length L Ch R = 1 ,19972.16,80.25,91.44,91.11
XS GIS Cut Line= 6
     629314.8903     4316035.161     629096.4261    4316295.9688
     629088.6176    4316312.6617     629071.4204    4316333.4281
     629062.4972    4316345.8137     629029.1757    4316385.5002
#Sta/Elev= 30
       0  684.35   18.39  681.87   42.91  676.86    61.3  670.49   79.69  662.81
   85.82  661.54   88.89  660.41   98.08  658.82  107.28  655.87  134.86  653.31
  147.12  651.32  159.38  650.66  177.77  648.17  196.16  645.01  217.62  642.45
  229.88  641.77  257.46  641.98  294.24   640.7   315.7  640.52  321.83   639.6
  327.96  639.39  361.64  639.73  397.82  639.03  400.87  639.36  403.92  641.27
  413.07  649.56  428.31  661.21   434.4  663.98   446.6   676.8  452.69  682.23
#Mann= 3 , 0 , 0
       0      .1       0   315.7    .041       0  403.92      .1       0
Bank Sta=315.7,403.92
XS Rating Curve= 0 ,0
Exp/Cntr=0.3,0.1

Type RM Length L Ch R = 1 ,19880.72,22.17,91.44,154.34
XS GIS Cut Line= 4
     629241.8651    4315997.0609     629050.2215    4316226.2675
       629000.88    4316278.1163     628956.2645    4316333.9186
#Sta/Elev= 30
       0  683.51   18.29  678.02   48.78  672.56   67.07  667.44   70.12  667.15
   79.27  665.21   85.36  664.59   94.51  662.99  115.85  662.41   118.9  661.63
  128.04  661.01  155.48  655.62  158.53   655.5  182.92  648.45  198.16  642.63
  201.21  642.18  207.31   641.9  246.94  641.95  322.63   640.8  340.52  639.15
  379.27  639.03  382.25  639.34  385.23  640.18   388.2  641.59  394.16  646.68
  406.07  655.67  409.04  658.41  420.95  667.79  429.88  673.17  441.79  682.28
#Mann= 3 , 0 , 0
       0      .1       0  322.63    .041       0  385.23      .1       0
Bank Sta=322.63,385.23
XS Rating Curve= 0 ,0
Exp/Cntr=0.3,0.1

Type RM Length L Ch R = 1 ,19789.28,92.81,91.44,90.15
XS GIS Cut Line= 6
       629237.72    4315990.4463     629054.0929    4316199.6981
     628975.9446    4316193.3398     628905.7471    4316168.1947
     628868.3747    4316181.7546     628804.6483    4316263.8045
#Sta/Elev= 30
       0  683.93    15.3  680.79   30.59  675.98   52.01  672.97   76.48  666.24
  100.96  664.13  116.25  664.15  122.37  662.93  131.55   662.2  159.08  656.93
  171.32  653.86  174.38  653.77   180.5  650.94  204.97  642.04  311.39  641.47
  317.14   641.1  322.89  639.61  331.52  638.92  470.09  639.63  491.49  637.87
  494.54  637.98  500.65   639.6  506.76  641.09  518.99  648.17  522.04  648.59
  537.32  660.83  546.49  666.22  558.71  674.76  570.93  680.87  577.04  684.82
#Mann= 3 , 0 , 0
       0      .1       0  322.89    .041       0  500.65      .1       0
Bank Sta=322.89,500.65
XS Rating Curve= 0 ,0
Exp/Cntr=0.3,0.1

Type RM Length L Ch R = 1 ,19697.84,112.84,91.44,30.52
XS GIS Cut Line= 6
     629218.6699    4315961.8712     629047.7162     4316106.368
     628941.4382    4316090.6551     628912.7785    4316097.3722
     628829.3298    4316185.6936     628789.4305     4316255.739
#Sta/Elev= 30
       0   683.6   67.46   672.2   79.72  667.68   82.79  667.13  107.32  664.34
  116.52  662.44  156.38  660.43  168.65  657.13  180.91  648.94  187.04  646.14
  190.11  645.43  217.71  642.07  241.85  641.23  250.42  639.42  258.77  637.98
  292.24  638.23  307.59  639.28   316.8  639.96  407.15  640.41   419.3  639.58
  458.79  639.55  480.06  637.65  483.09   637.8  495.04  640.89  503.99  646.57
  524.89  661.62  527.88  662.91  530.86  663.46  551.76  677.53  563.71  684.74
#Mann= 3 , 0 , 0
       0      .1       0  250.42    .041       0  307.59      .1       0
Bank Sta=250.42,307.59
XS Rating Curve= 0 ,0
Exp/Cntr=0.3,0.1

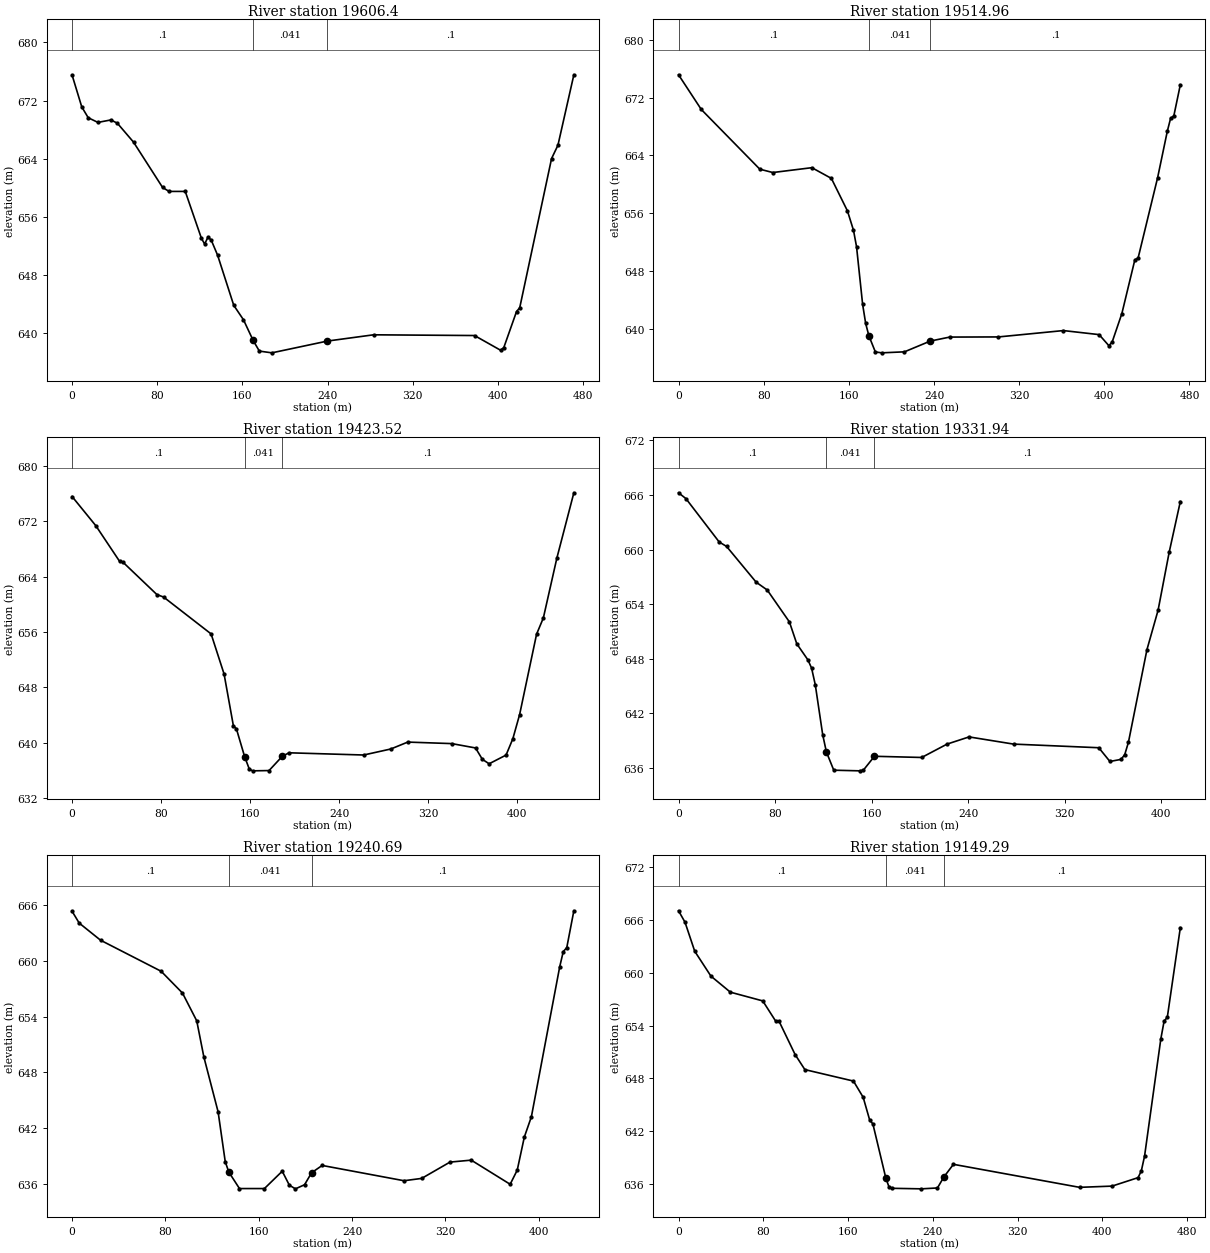
Type RM Length L Ch R = 1 ,19606.4 ,104.64,91.44,60.32
XS GIS Cut Line= 6
      629108.603    4315902.6044     628982.7647    4316012.5243
     628960.5289     4316026.958     628916.5322    4316064.3157
     628818.7465    4316183.0477     628787.8496    4316241.1634
#Sta/Elev= 30
       0  675.52    9.11  671.13   15.19  669.64    24.3     669   36.46  669.34
   42.53  668.89   57.72  666.29   85.06  660.05   91.14  659.51  106.33  659.51
  121.52  653.06  124.55  652.27  127.59   653.2  130.63  652.85  136.71  650.74
   151.9  643.84  161.01  641.86  170.03  639.04  175.92  637.55   187.7  637.31
  239.86  638.93  283.24  639.79  378.05  639.69  402.52  637.67  405.57  638.03
  417.54  642.99  420.53  643.51  450.45  664.03  456.43  665.86  471.39  675.55
#Mann= 3 , 0 , 0
       0      .1       0  170.03    .041       0  239.86      .1       0
Bank Sta=170.03,239.86
XS Rating Curve= 0 ,0
Exp/Cntr=0.3,0.1

Type RM Length L Ch R = 1 ,19514.96,95.6,91.44,92.21
XS GIS Cut Line= 5
     628968.3736    4315804.7084     628904.9567    4315947.0169
     628893.7027    4315963.5494     628863.8642    4316033.3503
      628777.506    4316235.3667
#Sta/Elev= 30
       0  675.16   21.38  670.36   76.37   662.1   88.59  661.64  125.25  662.31
  143.58  660.83  158.66  656.34  164.37  653.65  167.23  651.38  172.94  643.41
   175.8  640.77  178.84  639.05  184.91  636.82  190.98   636.7  212.24  636.84
  236.53  638.33  254.76  638.88  300.53   638.9  361.56  639.78  395.12  639.22
  404.28  637.69  407.33  638.18  416.48  642.13  428.69  649.57  431.74  649.81
  450.05  660.91   459.2  667.36  462.26  669.13  465.31  669.48  471.41  673.78
#Mann= 3 , 0 , 0
       0      .1       0  178.84    .041       0  236.53      .1       0
Bank Sta=178.84,236.53
XS Rating Curve= 0 ,0
Exp/Cntr=0.3,0.1

Type RM Length L Ch R = 1 ,19423.52,92,91.58,67.98
XS GIS Cut Line= 6
     628864.6975    4315788.3538     628812.7735    4315908.6743
     628808.8538    4315927.7433     628800.3632    4315949.6647
     628789.7547    4315967.8088     628699.9067    4316207.4385
#Sta/Elev= 30
       0   675.6   21.33  671.38   42.67  666.23   45.71   666.1   76.19  661.42
   82.28  661.05  124.95  655.72  136.61  649.92  144.95  642.45  147.73  641.97
  155.06  637.97  159.33  636.14  162.27  635.91  177.02  635.95  189.03  638.03
  195.04  638.52  262.07   638.2  286.44  639.07  301.67  640.07  341.28  639.85
  362.61  639.22   368.7  637.58  374.79  636.93  390.03  638.19  396.12  640.55
  402.21  644.05  417.45  655.68  423.54  658.03  435.73  666.72  450.96  676.14
#Mann= 3 , 0 , 0
       0      .1       0  155.06    .041       0  189.03      .1       0
Bank Sta=155.06,189.03
XS Rating Curve= 0 ,0
Exp/Cntr=0.3,0.1

Type RM Length L Ch R = 1 ,19331.94,91.12,91.25,122.86
XS GIS Cut Line= 5
     628760.1869    4315779.0934     628707.7978    4315939.1615
     628710.6044    4315963.0286      628709.943    4316002.0547
     628653.9873    4316177.5971
#Sta/Elev= 30
       0  666.25    6.12  665.61   33.68  660.84   39.81  660.35   64.31  656.42
   73.49  655.56   91.87  652.05   97.99  649.64  107.18  647.88  110.24  646.97
   113.3  645.14  119.43  639.66  122.49  637.76  128.61  635.75  150.05  635.68
  153.11  635.75   162.3  637.28  201.46  637.15  222.48  638.62   240.7  639.41
  277.55  638.62  348.17  638.22  357.39  636.71   366.6  636.94  369.67  637.46
  372.74  638.82  388.09  649.01  397.31  653.34  406.52  659.73  415.73  665.29
#Mann= 3 , 0 , 0
       0      .1       0  122.49    .041       0   162.3      .1       0
Bank Sta=122.49,162.3
XS Rating Curve= 0 ,0
Exp/Cntr=0.3,0.1

Type RM Length L Ch R = 1 ,19240.69,101.89,91.39,61.37
XS GIS Cut Line= 6
      628676.843    4315743.3746     628617.8103    4315919.9807
      628608.431    4315929.0252     628599.7261    4315954.7957
     628590.2011    4315967.0988     628546.4487    4316149.9648
#Sta/Elev= 30
       0   665.3    6.11  664.03   24.42  662.19   76.32  658.86   94.63  656.52
  106.84  653.54  112.95  649.66  125.16  643.77  131.26  638.43  134.32  637.31
  143.47  635.54  164.84  635.54  180.11   637.4  186.21   635.9  191.42  635.51
  199.24  635.95  205.29  637.24  214.35  638.02  284.46  636.38  299.62  636.63
  323.88  638.38  342.08  638.59  375.44     636  381.51  637.52  387.57  641.06
  393.64  643.25   417.9  659.34  420.93  660.96  423.96   661.4  430.03  665.35
#Mann= 3 , 0 , 0
       0      .1       0  134.32    .041       0  205.29      .1       0
Bank Sta=134.32,205.29
XS Rating Curve= 0 ,0
Exp/Cntr=0.3,0.1

Type RM Length L Ch R = 1 ,19149.29,103.42,91.54,54.42
XS GIS Cut Line= 5
     628498.2489    4315666.6452     628545.9156    4315890.9787
     628538.0271    4315929.3874     628536.9228    4315962.7155
     628504.3039    4316131.3934
#Sta/Elev= 30
       0  667.01    6.12  665.71   15.29  662.42   30.58   659.6   48.93  657.78
   79.51  656.79   91.74  654.49   94.79  654.51  110.08   650.7  119.26     649
  165.13   647.7   174.3  645.86  180.42  643.29  183.47  642.84  195.71  636.69
  198.76  635.67  201.82  635.54  229.34  635.48  244.42  635.58  250.46  636.82
   259.5  638.26   378.6  635.65  409.28  635.79  433.82  636.75  436.89  637.52
  439.95   639.2  455.29  652.48  458.36  654.48  461.43  654.95   473.7   665.1
#Mann= 3 , 0 , 0
       0      .1       0  195.71    .041       0  250.46      .1       0
Bank Sta=195.71,250.46
XS Rating Curve= 0 ,0
Exp/Cntr=0.3,0.1