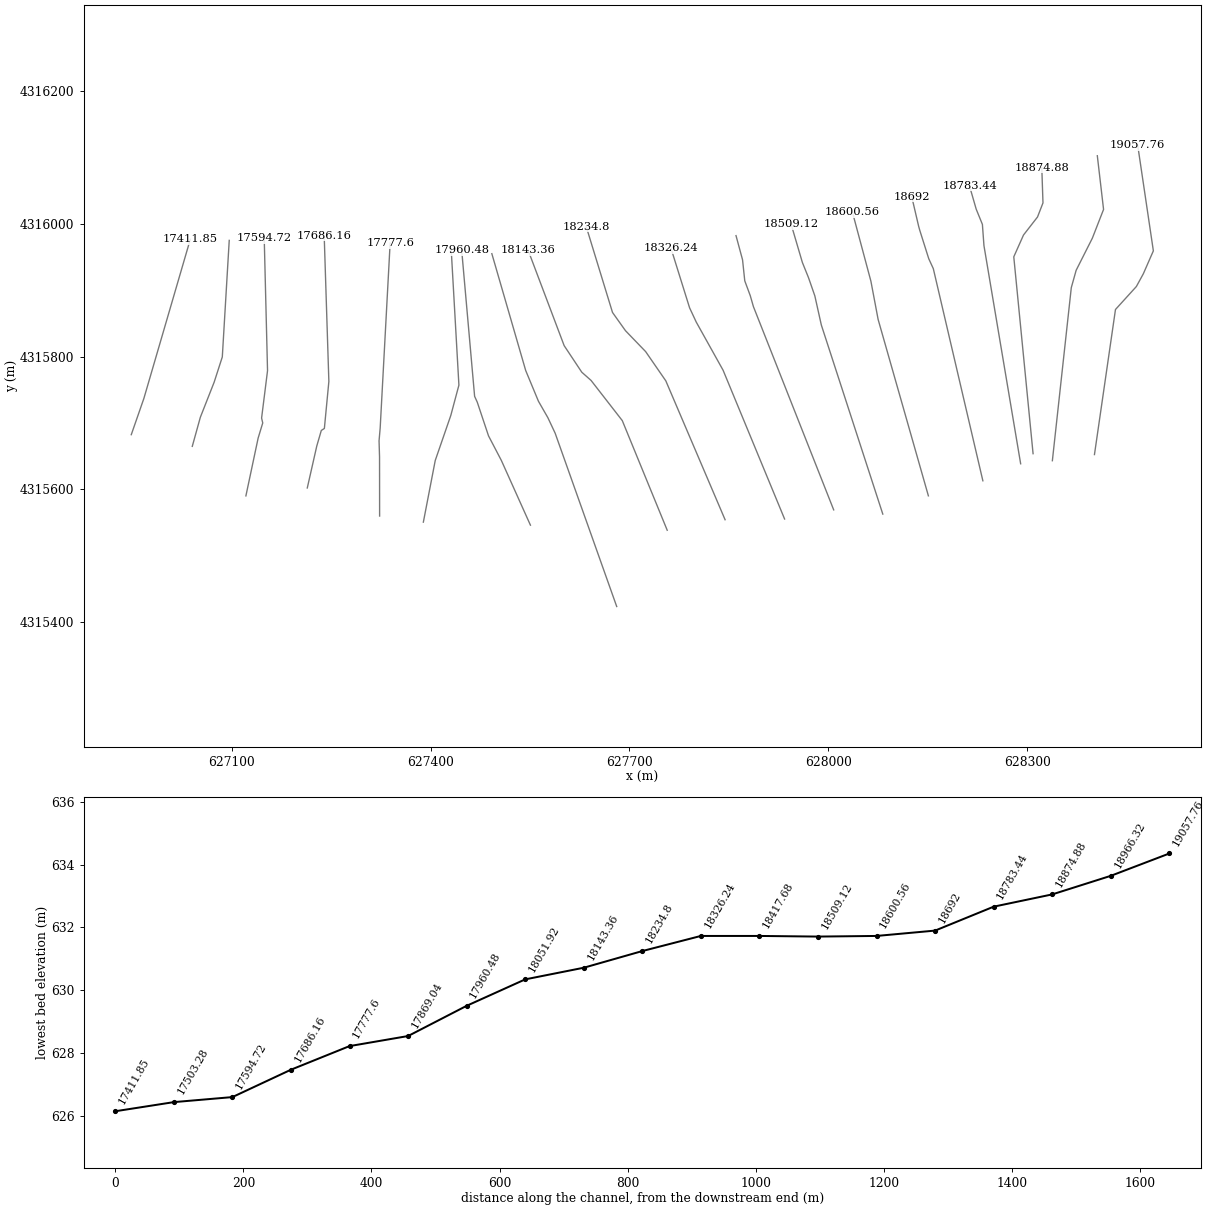
HEC-RAS study RedCreek.prj: RedCreek

--- RedCreek.g01 (geometry) --- (continued)

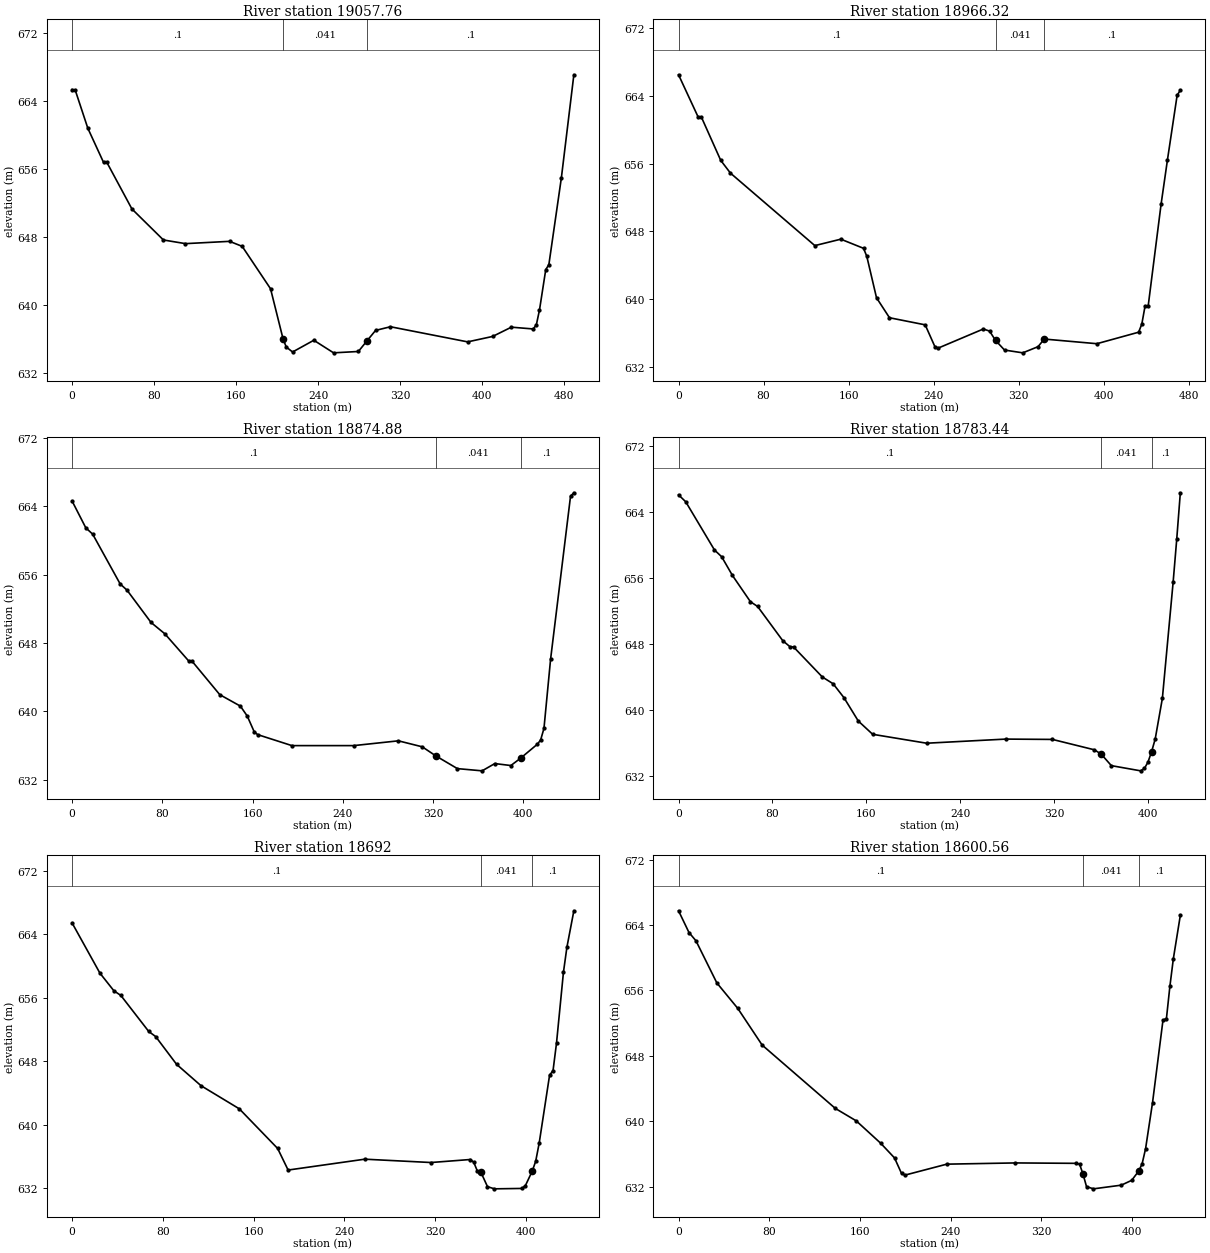
Type RM Length L Ch R = 1 ,19057.76,82.92,91.44,92.62
XS GIS Cut Line= 6
     628401.6758    4315652.0931     628433.3911    4315870.9578
     628464.9256    4315905.6624     628475.4599     4315924.933
     628490.5412    4315959.4611     628466.8664    4316119.1382
#Sta/Elev= 30
       0  665.32    3.07  665.27   15.36  660.78   30.72  656.75   33.79  656.79
   58.36  651.28   89.07  647.63  110.58   647.2  153.58  647.47  165.86  646.88
  193.51  641.89  205.79  635.95  208.86  635.03  215.01  634.45   235.7  635.83
  254.96  634.35  279.15  634.51  287.38  635.74  295.92  636.99  310.41  637.42
  385.67  635.64  410.04  636.28  428.31  637.37  449.63  637.16  452.68  637.66
  455.72  639.39  461.82  644.14  464.86  644.73  477.04  654.93  489.23  667.07
#Mann= 3 , 0 , 0
       0      .1       0  205.79    .041       0  287.38      .1       0
Bank Sta=205.79,287.38
XS Rating Curve= 0 ,0
Exp/Cntr=0.3,0.1

Type RM Length L Ch R = 1 ,18966.32,96.89,91.44,88.71
XS GIS Cut Line= 6
     628338.1756    4315642.8327     628366.7358    4315903.9515
       628374.07    4315930.1622      628398.504    4315978.5795
     628415.4192    4316021.9559      628405.985    4316102.9401
#Sta/Elev= 30
       0  666.52   18.33  661.56   21.38  661.55   39.71   656.4   48.87  654.89
  128.28  646.32  152.72  647.08   174.1     646  177.15  645.06  186.32  640.15
  198.53  637.79  232.13  636.95   241.3  634.36  244.35   634.2  286.87  636.46
  292.71  636.21  298.34  635.11  306.78  633.97  323.95  633.64  338.38  634.37
  344.15  635.27  393.72  634.72  432.98  636.08     436  637.04  439.02  639.15
  442.04  639.23  454.12   651.2  460.16  656.49  469.22  664.08  472.24   664.7
#Mann= 3 , 0 , 0
       0      .1       0  298.34    .041       0  344.15      .1       0
Bank Sta=298.34,344.15
XS Rating Curve= 0 ,0
Exp/Cntr=0.3,0.1

Type RM Length L Ch R = 1 ,18874.88,56.56,91.44,102.2
XS GIS Cut Line= 6
     628309.0714    4315653.4161     628279.9523    4315950.4135
     628294.6367    4315983.3542     628315.7701    4316010.5462
     628324.0055     4316031.773     628322.2312    4316084.7455
#Sta/Elev= 30
       0  664.61   12.18  661.47   18.27  660.73   42.63  654.91   48.72  654.18
   70.04   650.4   82.22  649.08  103.53  645.88  106.58  645.84  130.94  641.96
  149.21  640.62   155.3  639.46  161.39  637.64  164.44  637.29  194.89     636
   249.7     636  289.29  636.56  310.44  635.86  322.47   634.8  341.61  633.31
  363.51  633.05  374.78   633.9  389.01  633.67  397.74  634.54  412.47  636.16
  415.41  636.66  418.36  638.02  424.24  646.12  441.91  665.17  444.86  665.57
#Mann= 3 , 0 , 0
       0      .1       0  322.47    .041       0  397.74      .1       0
Bank Sta=322.47,397.74
XS Rating Curve= 0 ,0
Exp/Cntr=0.3,0.1

Type RM Length L Ch R = 1 ,18783.44,92.88,91.44,91.08
XS GIS Cut Line= 5
       628290.33    4315638.2025      628234.951    4315967.3468
     628232.6086    4315999.3773     628223.2522     4316022.357
     628213.0667    4316057.6047
#Sta/Elev= 30
       0  666.13    6.12  665.29   30.62  659.44   36.75  658.62   45.93  656.35
   61.24  653.17   67.37  652.59    88.8  648.44   94.93  647.71   97.99  647.68
  122.48  644.04  131.67  643.22  140.86  641.54  153.11   638.7  165.35  637.09
  211.29  636.01  278.65  636.51  318.46  636.47  354.21  635.21  360.05  634.68
  368.64  633.29   393.6  632.66  396.81  632.95  399.87  633.73  402.93  634.99
  405.99  636.52   412.1  641.45  421.27  655.55  424.33  660.75  427.39  666.38
#Mann= 3 , 0 , 0
       0      .1       0  360.05    .041       0  402.93      .1       0
Bank Sta=360.05,402.93
XS Rating Curve= 0 ,0
Exp/Cntr=0.3,0.1

Type RM Length L Ch R = 1 ,18692   ,96.9,91.44,91.09
XS GIS Cut Line= 6
     628233.3122    4315612.5378     628158.5331     4315932.657
     628151.7038    4315947.4895     628138.0064    4315990.7832
     628136.3917    4315996.6273     628125.9617    4316041.3048
#Sta/Elev= 30
       0  665.44   24.58   659.1   36.87  656.88   43.01  656.29   67.59  651.75
   73.74   651.1   92.17   647.6  113.68  644.91  147.47  641.99  181.27  636.99
  190.48  634.27  258.07  635.64  316.45  635.22  351.12   635.6  354.15  635.25
  357.18   634.2   360.2  634.07  366.26  632.18  372.31   631.9  396.54  631.95
   399.6  632.28  405.71  634.13  408.77  635.38  411.83  637.65  421.01  646.23
  424.07  646.82  427.12  650.28  433.24  659.22   436.3  662.38  442.42  666.97
#Mann= 3 , 0 , 0
       0      .1       0   360.2    .041       0  405.71      .1       0
Bank Sta=360.2,405.71
XS Rating Curve= 0 ,0
Exp/Cntr=0.3,0.1

Type RM Length L Ch R = 1 ,18600.56,86.98,91.44,92.9
XS GIS Cut Line= 4
     628151.1148    4315589.8189     628075.2994    4315855.9057
     628064.3839    4315913.6898     628036.6355    4316017.3385
#Sta/Elev= 30
       0  665.75    9.22  663.09   15.37  662.08   33.82  656.92   52.26  653.81
   73.78  649.32  138.34  641.57  156.78  640.05   178.3  637.32   190.6  635.51
  196.75  633.62  199.82  633.41  236.71  634.75  297.26   634.9  350.81  634.85
  353.88  634.75  356.94  633.52  360.01     632  366.14  631.73  390.67  632.18
  399.86  632.77  405.99  633.89  409.06  634.79  412.12  636.64  418.26  642.28
  427.45  652.34  430.52  652.57  433.58  656.52  436.65  659.91  442.78  665.19
#Mann= 3 , 0 , 0
       0      .1       0  356.94    .041       0  405.99      .1       0
Bank Sta=356.94,405.99
XS Rating Curve= 0 ,0
Exp/Cntr=0.3,0.1

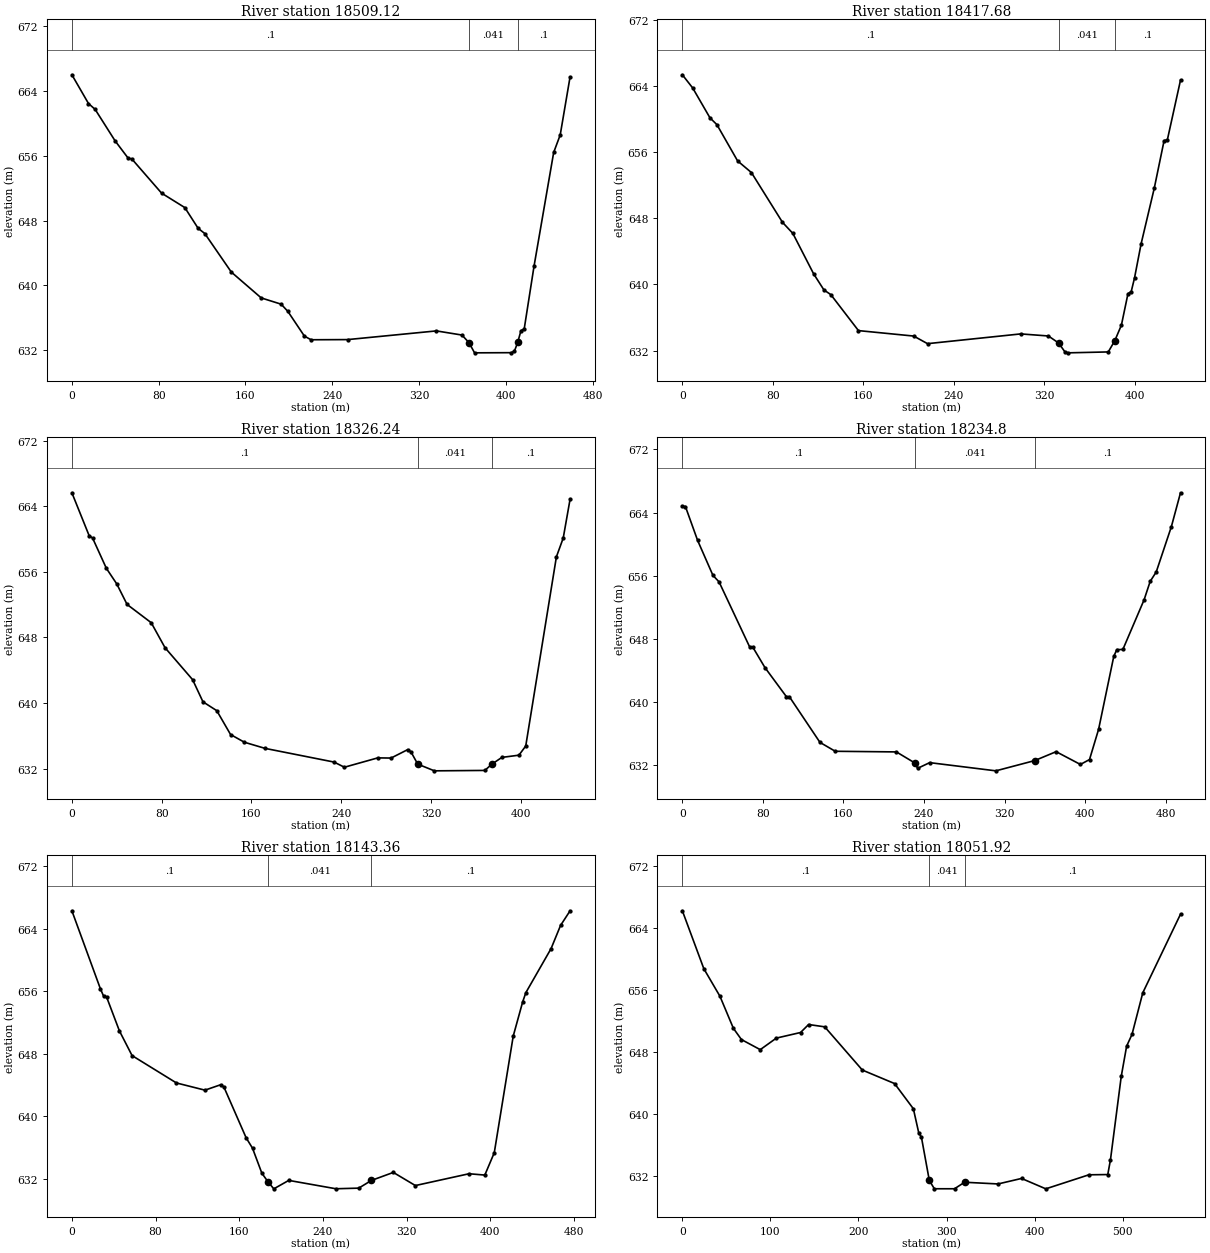
Type RM Length L Ch R = 1 ,18509.12,91.97,91.44,89.53
XS GIS Cut Line= 6
      628082.323    4315562.3022     627989.5743     4315847.633
      627979.813    4315891.4719     627970.2605    4315918.9643
     627961.0005    4315941.9278     627943.9653      4315999.79
#Sta/Elev= 30
       0  665.94   15.31   662.4   21.43  661.68    39.8  657.81   52.05  655.64
   55.11   655.6   82.66  651.37  104.09  649.59  116.34  647.04  122.46   646.4
  146.95  641.65  174.51  638.47  192.87   637.7     199  636.82   214.3  633.77
  220.43  633.32   254.1  633.34  335.96  634.41  359.49   633.9   365.9  632.98
  371.13  631.71  404.84  631.73  407.85  631.91  410.87     633  413.88  634.43
   416.9  634.67  425.95  642.39  444.04  656.38  450.07  658.54  459.12  665.66
#Mann= 3 , 0 , 0
       0      .1       0   365.9    .041       0  410.87      .1       0
Bank Sta=365.9,410.87
XS Rating Curve= 0 ,0
Exp/Cntr=0.3,0.1

Type RM Length L Ch R = 1 ,18417.68,85.09,91.44,95.21
XS GIS Cut Line= 6
     628008.2396    4315568.6522     627887.1264    4315875.3165
     627882.3877    4315891.7822     627874.0779    4315914.2077
     627870.7293    4315945.9425     627860.8778     4315982.393
#Sta/Elev= 30
       0  665.37    9.16  663.77   24.42  660.16   30.53  659.34   48.85  654.95
   61.06  653.54   88.53  647.52   97.69  646.18  116.01   641.3  125.17  639.34
  131.28  638.77   155.7  634.42  204.54  633.76  216.76  632.84  299.19  634.02
  323.61  633.77  332.57  632.93  338.34  631.83  341.14  631.73  376.57  631.84
  382.37  633.21  388.17  635.08  393.97  638.88  396.87  639.15  399.77  640.79
  405.58  644.91   417.2  651.63  425.91   657.4  428.82  657.51  440.43  664.72
#Mann= 3 , 0 , 0
       0      .1       0  332.57    .041       0  382.37      .1       0
Bank Sta=332.57,382.37
XS Rating Curve= 0 ,0
Exp/Cntr=0.3,0.1

Type RM Length L Ch R = 1 ,18326.24,85.37,91.44,108.11
XS GIS Cut Line= 5
     627934.1561    4315554.8938     627841.3825    4315779.3153
     627800.8818     4315851.961     627790.8288    4315873.5031
     627762.7652    4315963.3565
#Sta/Elev= 30
       0  665.65   15.37  660.42   18.44  660.13   30.74  656.43   39.96  654.54
   49.18  652.03    70.7   649.8      83  646.75  107.59  642.85  116.81  640.15
  129.11  639.07   141.4  636.16   153.7  635.22  172.14  634.47  233.62   632.8
  242.84  632.17  272.55  633.31  284.43  633.29  299.28  634.32  302.25  634.02
  308.19  632.55  323.04  631.73  368.01  631.78  374.08  632.53  383.19  633.37
  398.37  633.64  404.44  634.76  431.77  657.84  437.85  660.13  443.92  664.84
#Mann= 3 , 0 , 0
       0      .1       0  308.19    .041       0  374.08      .1       0
Bank Sta=308.19,374.08
XS Rating Curve= 0 ,0
Exp/Cntr=0.3,0.1

Type RM Length L Ch R = 1 ,18234.8 ,89.27,91.44,89.17
XS GIS Cut Line= 6
      627844.385    4315553.8024     627754.9694    4315763.3035
     627724.5324    4315807.4242     627694.1151    4315838.9745
     627674.5359    4315866.4912     627634.8483    4315996.1373
#Sta/Elev= 30
       0   664.8    3.04  664.77   15.19  660.46   30.37  656.04   36.45  655.21
   66.82  646.97   69.85  646.96      82  644.35  103.26  640.67   106.3  640.65
  136.67  634.86  151.86  633.73   212.6  633.65  230.76  632.26  233.74  631.57
  245.65  632.29  311.39  631.25  349.99  632.55  371.25  633.68  395.36  632.06
   404.4  632.68  413.44  636.52   428.5  645.76  431.51  646.62  437.54  646.64
  458.63  652.94  464.66  655.27  470.68  656.47  485.75  662.23  494.79  666.51
#Mann= 3 , 0 , 0
       0      .1       0  230.76    .041       0  349.99      .1       0
Bank Sta=230.76,349.99
XS Rating Curve= 0 ,0
Exp/Cntr=0.3,0.1

Type RM Length L Ch R = 1 ,18143.36,107.24,91.44,72.18
XS GIS Cut Line= 6
     627757.0723    4315537.9274     627689.2909    4315703.3224
     627642.2165    4315763.9109      627628.172    4315776.3475
     627601.5813     4315816.432     627547.2026    4315960.4417
#Sta/Elev= 30
       0  666.28   27.27   656.3    30.3  655.37   33.33   655.2   45.44  650.92
   57.56  647.76   99.98  644.26  127.24  643.34  142.39  644.04  145.42  643.72
  166.63  637.24  172.69  635.92  181.61  632.73  187.33  631.65  193.06  630.72
  207.37   631.8  252.45  630.73  274.27  630.81  286.29  631.79  307.34  632.82
  328.41  631.14  379.72  632.65  394.81  632.48  403.86  635.34  421.97  650.25
  431.03  654.64  434.05  655.81  458.19  661.45  467.25  664.41   476.3  666.27
#Mann= 3 , 0 , 0
       0      .1       0  187.33    .041       0  286.29      .1       0
Bank Sta=187.33,286.29
XS Rating Curve= 0 ,0
Exp/Cntr=0.3,0.1

Type RM Length L Ch R = 1 ,18051.92,90.56,91.44,85.97
XS GIS Cut Line= 6
     627680.8721    4315422.8334     627587.9827    4315684.4001
     627577.0278    4315707.7033     627562.8032    4315732.5258
     627543.5702    4315778.8742     627492.4884    4315955.1762
#Sta/Elev= 30
       0  666.19    24.4  658.72    42.7  655.17   57.95  651.04   67.11  649.59
   88.46  648.29  106.76  649.78  134.21   650.5  143.36  651.53  161.66  651.23
  204.37  645.66  240.97  643.92  262.32  640.67  268.42  637.57  271.47  637.01
  280.43  631.43  286.15  630.36  309.04  630.36  320.49   631.2   358.5  630.98
  385.17  631.69   412.7  630.35  461.65  632.16  483.06  632.19  486.12  634.09
  498.36  644.84  504.48  648.74   510.6  650.26  522.83  655.62  565.66  665.75
#Mann= 3 , 0 , 0
       0      .1       0  280.43    .041       0  320.49      .1       0
Bank Sta=280.43,320.49
XS Rating Curve= 0 ,0
Exp/Cntr=0.3,0.1

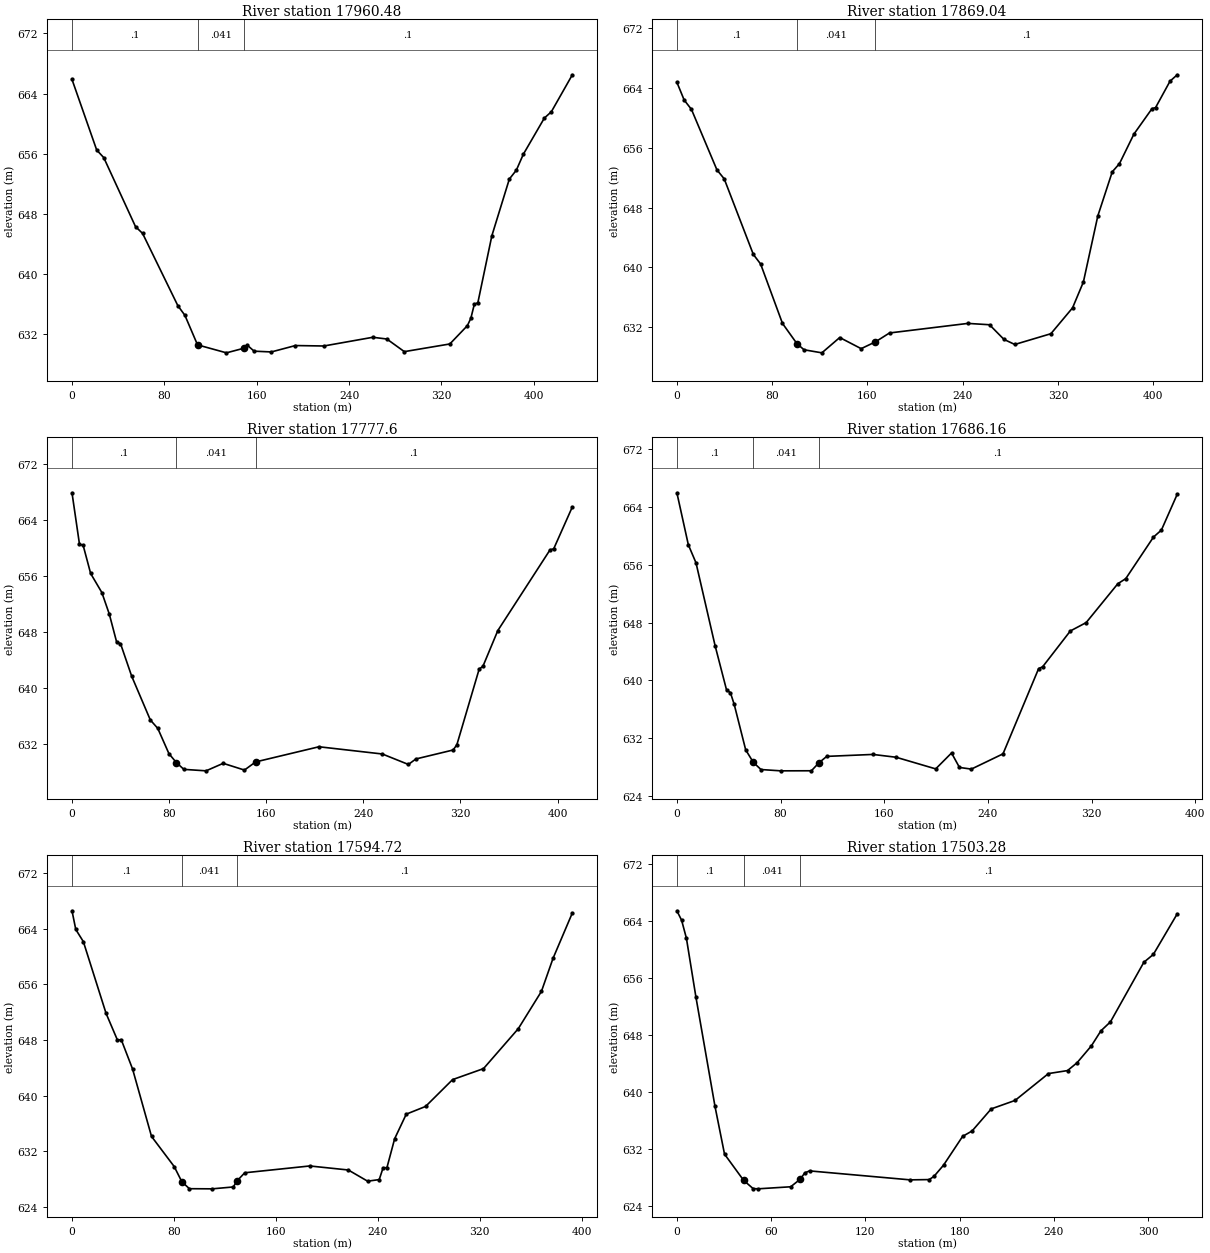
Type RM Length L Ch R = 1 ,17960.48,107.65,91.44,30.77
XS GIS Cut Line= 6
     627550.6969    4315545.6003     627506.8405    4315643.2052
     627487.4772    4315680.3023     627470.4635    4315731.2029
     627466.4947    4315739.9342       627446.98    4315960.4678
#Sta/Elev= 30
       0  665.88    21.4  656.49   27.52  655.48   55.03   646.3   61.15   645.4
   91.72  635.78   97.83   634.5  108.76  630.57  133.82  629.51  148.86  630.12
  151.84  630.53   157.8  629.73  172.71  629.63  193.58  630.48  218.18  630.42
  260.64  631.58  272.77  631.35  287.94  629.67  327.36  630.69  342.53  633.12
  345.56   634.1  348.59  635.98  351.63  636.17  363.76  645.08  378.92  652.63
  384.99  653.81  391.05  655.93  409.25  660.74  415.32  661.58  433.51   666.5
#Mann= 3 , 0 , 0
       0      .1       0  108.76    .041       0  148.86      .1       0
Bank Sta=108.76,148.86
XS Rating Curve= 0 ,0
Exp/Cntr=0.3,0.1

Type RM Length L Ch R = 1 ,17869.04,84.1,91.44,115.83
XS GIS Cut Line= 5
     627389.1518    4315550.1823     627407.0945    4315643.2085
     627430.5852    4315711.1855      627442.788    4315756.8609
      627431.105    4315962.5845
#Sta/Elev= 30
       0  664.77    6.11  662.39   12.22  661.14   33.62  653.04   39.73  651.84
   64.18  641.72   70.29  640.44   88.63  632.49  100.73  629.79  106.73  628.96
  121.71  628.55  136.69   630.6  154.68  629.11  166.66  630.02  178.48  631.21
  244.24  632.49  262.42  632.31  274.54  630.35  283.63  629.67  313.94  631.11
  332.12  634.57  341.21  638.03  353.33  646.88  365.45  652.78  371.51  653.88
  383.63  657.83  398.78  661.23  401.81  661.38  413.93  664.91  419.99  665.77
#Mann= 3 , 0 , 0
       0      .1       0  100.73    .041       0  166.66      .1       0
Bank Sta=100.73,166.66
XS Rating Curve= 0 ,0
Exp/Cntr=0.3,0.1

Type RM Length L Ch R = 1 ,17777.6 ,96.79,91.44,81.71
XS GIS Cut Line= 5
     627323.1548    4315559.3587     627323.0511    4315648.4568
     627322.3148    4315672.8323     627324.0064    4315692.1261
     627339.0298    4315971.0512
#Sta/Elev= 30
       0  667.85    6.14  660.55    9.22  660.34   15.36  656.35   24.58  653.64
   30.72  650.57   36.87  646.52   39.94  646.37   49.16  641.72   64.52  635.48
   70.66  634.28   79.88  630.67   86.03   629.4   92.15  628.44  110.44  628.23
  124.55   629.3  142.06  628.34  151.27   629.5  203.45  631.66  255.63  630.63
  277.12  629.14  283.26  629.92  313.96   631.2  317.03  631.94  335.44  642.74
  338.51  643.12  350.79  648.22  393.77  659.71  396.83  659.87  412.18  665.84
#Mann= 3 , 0 , 0
       0      .1       0   86.03    .041       0  151.27      .1       0
Bank Sta=86.03,151.27
XS Rating Curve= 0 ,0
Exp/Cntr=0.3,0.1

Type RM Length L Ch R = 1 ,17686.16,90.48,91.44,94.36
XS GIS Cut Line= 6
     627214.0139    4315601.6921     627228.3577     4315664.997
     627235.1752    4315688.4792     627239.8158    4315691.5087
     627246.5892    4315762.4172     627239.5463    4315982.3401
#Sta/Elev= 30
       0  665.95    8.85  658.75   14.75  656.26    29.5  644.79   38.36  638.65
   41.31   638.3   44.26  636.66   53.11  630.38   59.01  628.65   64.91  627.66
   80.19  627.48  103.81  627.49  109.74  628.61  115.68  629.48  151.29  629.75
  169.19  629.36  199.75  627.75  211.98  629.95  218.09  627.95  227.26  627.72
   251.7  629.83  279.21  641.63  282.26  641.87  303.66  646.83  315.88  647.99
  340.33  653.37  346.44  654.07  367.83  659.82  373.95  660.79  386.17  665.75
#Mann= 3 , 0 , 0
       0      .1       0   59.01    .041       0  109.74      .1       0
Bank Sta=59.01,109.74
XS Rating Curve= 0 ,0
Exp/Cntr=0.3,0.1

Type RM Length L Ch R = 1 ,17594.72,92.87,91.44,76.34
XS GIS Cut Line= 6
     627121.4096    4315589.7417      627139.887    4315676.9664
     627146.8215    4315699.8096     627145.0948    4315707.1544
     627154.0554     4315778.645     627149.0586      4315978.68
#Sta/Elev= 30
       0   666.6    2.97  663.91    8.92  662.16   26.75  651.84   35.66  648.01
   38.64  648.07   47.55  643.84   62.41  634.15   80.24  629.81   86.19  627.64
   92.14  626.63  110.05  626.61  126.58  626.88  129.58  627.76  135.59  628.92
  186.62   629.9  216.88  629.32  232.04  627.71  241.14  627.94  244.17  629.63
   247.2  629.66  253.26  633.82  262.36  637.35  277.52  638.46  298.74  642.32
  322.99   643.9  350.28  649.64  368.47  655.01  377.57  659.76  392.73  666.29
#Mann= 3 , 0 , 0
       0      .1       0   86.19    .041       0  129.58      .1       0
Bank Sta=86.19,129.58
XS Rating Curve= 0 ,0
Exp/Cntr=0.3,0.1

Type RM Length L Ch R = 1 ,17503.28,90.19,91.43,95.26
XS GIS Cut Line= 5
     627040.5185    4315664.4968     627052.6801    4315708.3445
     627073.5309    4315761.3153     627085.8192    4315799.3994
     627096.2741    4315975.2404
#Sta/Elev= 30
       0  665.48    3.03  664.14    6.07  661.62   12.13  653.36   24.27  638.02
   30.34  631.32   42.47  627.65    48.5  626.49    51.5  626.45   72.47  626.74
   78.46  627.79   81.46  628.69   84.45  628.97  148.52  627.71  160.67  627.75
  163.71   628.2  169.78  629.77  181.93  633.81     188  634.58  200.15  637.67
  215.34  638.86   236.6  642.63  248.75  643.05  254.82  644.15  263.93  646.52
  270.01  648.63  276.08  649.89  297.34  658.25  303.41  659.36   318.6  665.05
#Mann= 3 , 0 , 0
       0      .1       0   42.47    .041       0   78.46      .1       0
Bank Sta=42.47,78.46
XS Rating Curve= 0 ,0
Exp/Cntr=0.3,0.1

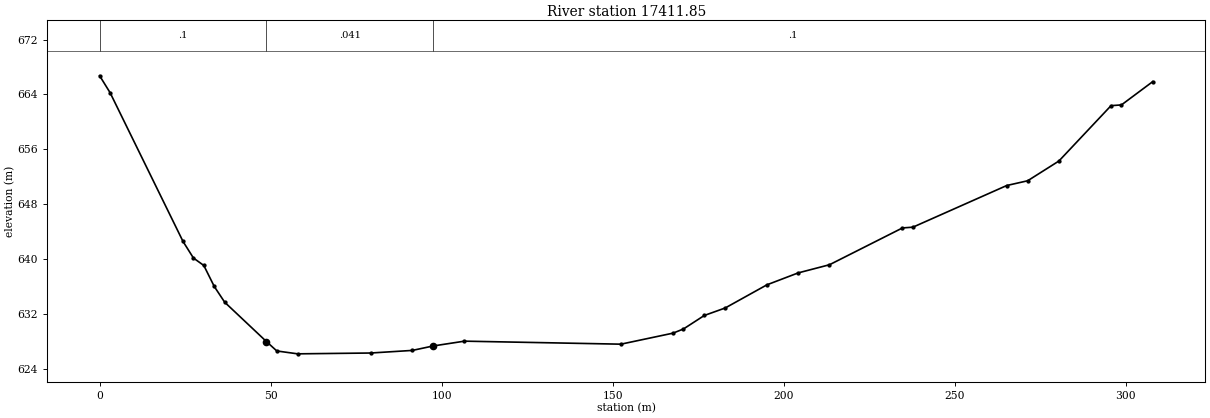
Type RM Length L Ch R = 1 ,17411.85,89.06,91.45,102.75
XS GIS Cut Line= 3
     626948.4668    4315682.0943     626967.4917    4315736.7811
     627037.5365    4315976.8279
#Sta/Elev= 30
       0  666.73    3.05  664.27   24.38  642.56   27.43  640.14   30.47  639.05
   33.52  635.99   36.57  633.69   48.76  627.96   51.81  626.58    57.9  626.16
   79.25  626.28   91.45  626.66   97.54  627.31  106.69  628.01  152.44  627.57
  167.68  629.18  170.73  629.79  176.83  631.76  182.93  632.85  195.13  636.23
  204.28  637.97  213.43  639.16  234.77  644.53  237.82  644.64  265.27  650.72
  271.37  651.41  280.51  654.29  295.76  662.37  298.81  662.48  307.96  665.88
#Mann= 3 , 0 , 0
       0      .1       0   48.76    .041       0   97.54      .1       0
Bank Sta=48.76,97.54
XS Rating Curve= 0 ,0
Exp/Cntr=0.3,0.1