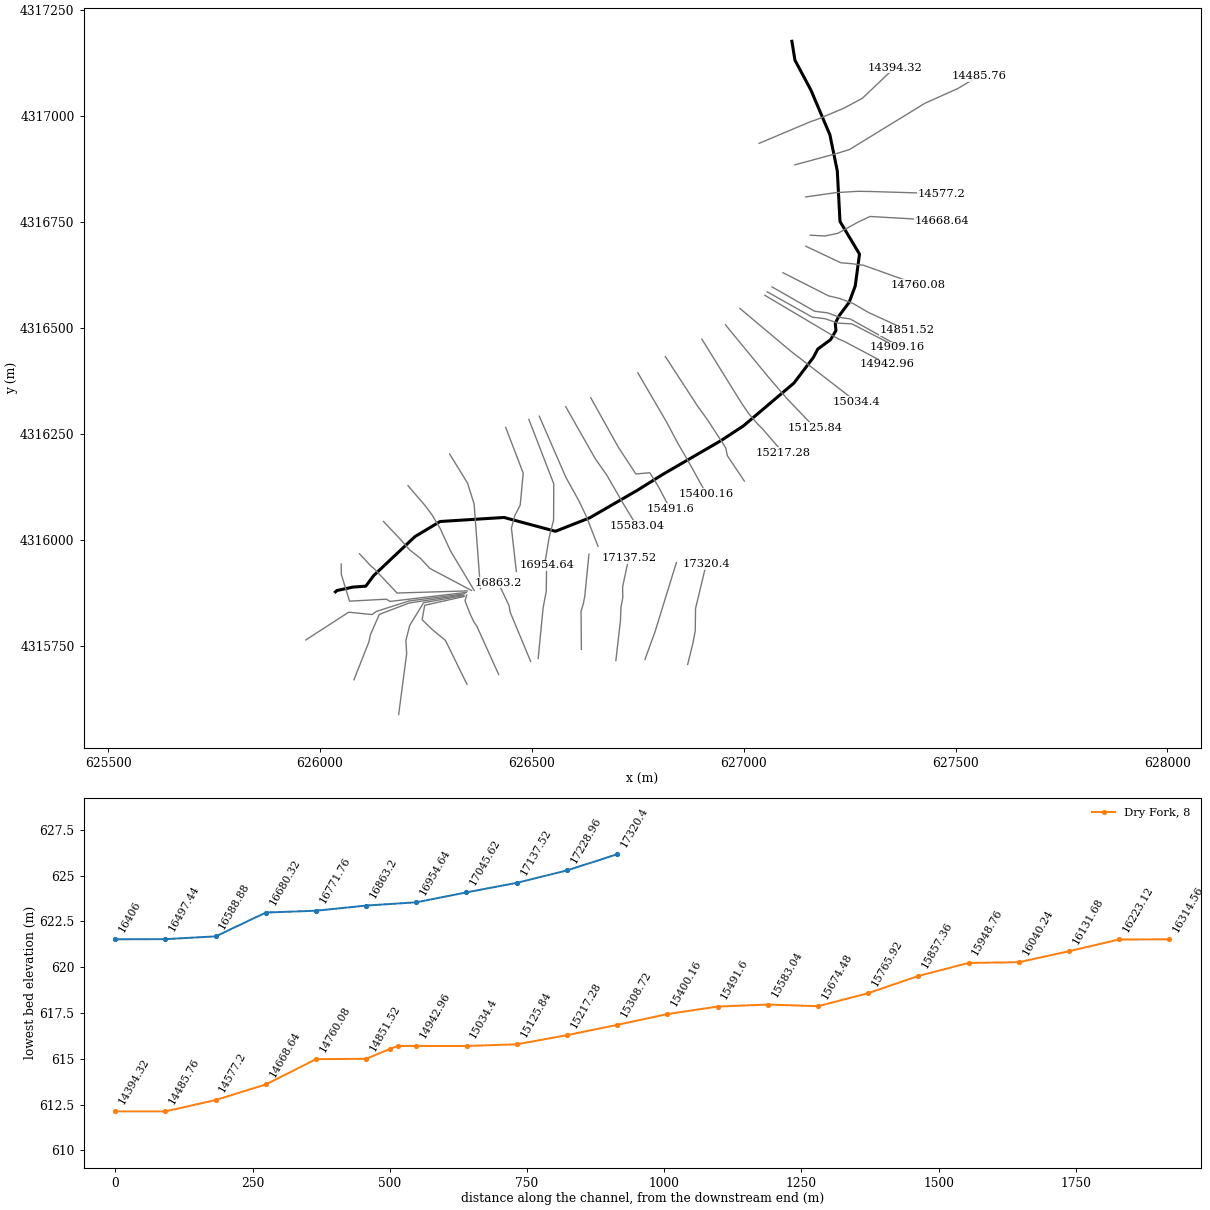
HEC-RAS study RedCreek.prj: RedCreek

--- RedCreek.g01 (geometry) --- (continued)

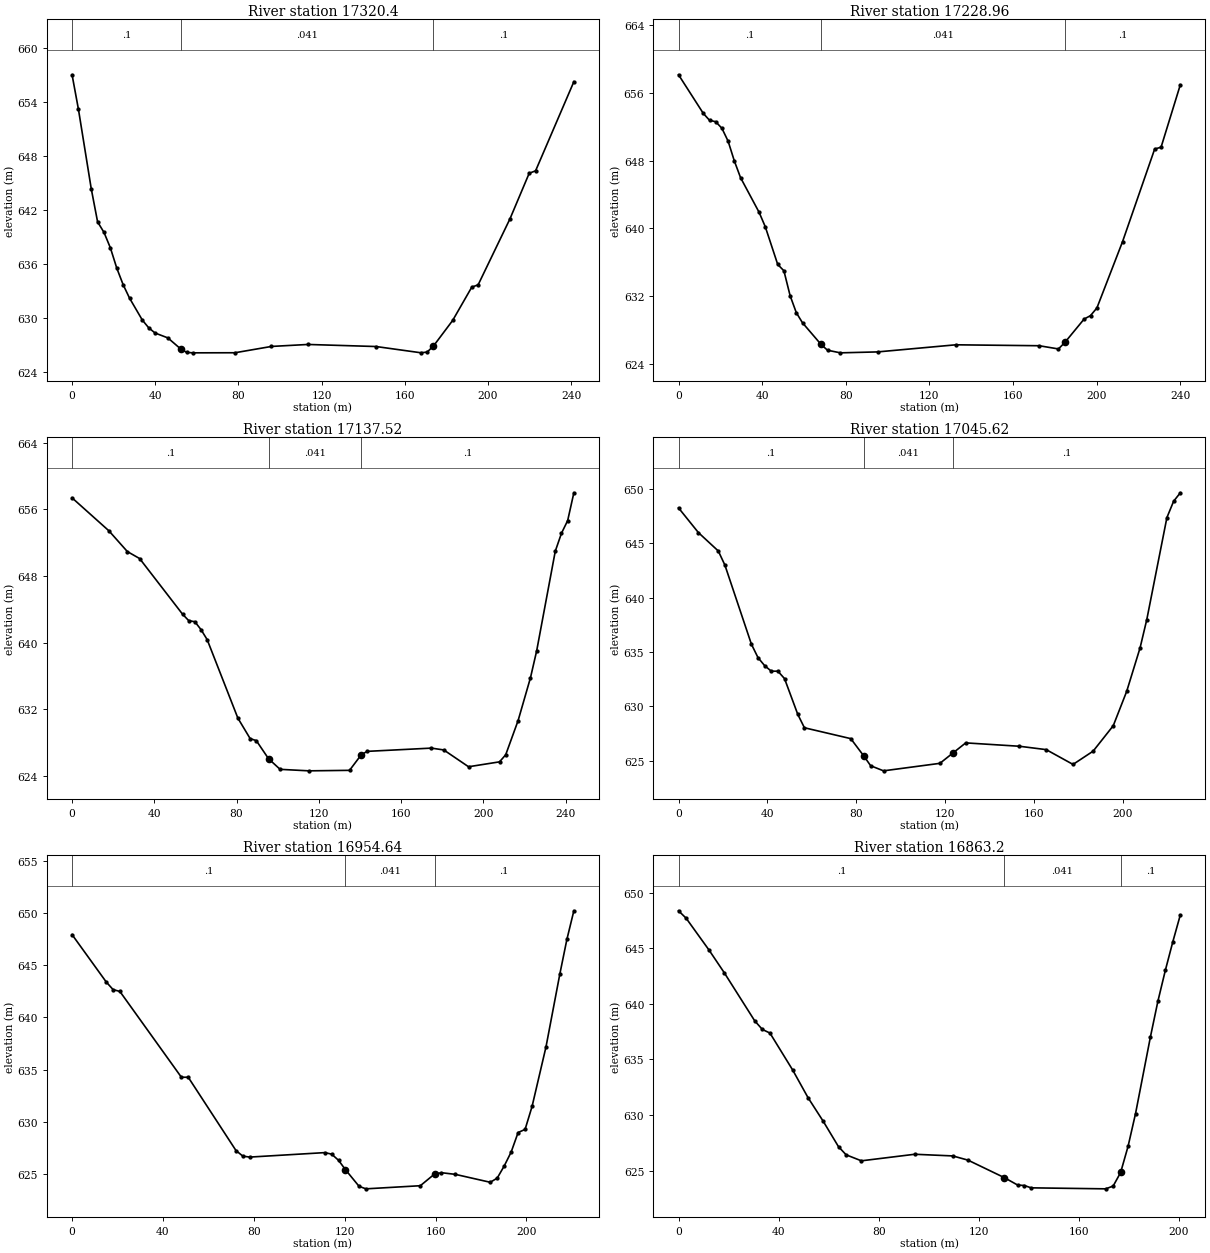
Type RM Length L Ch R = 1 ,17320.4 ,94.2,91.44,80.63
XS GIS Cut Line= 5
      626867.815    4315706.5267     626880.2961    4315757.2173
     626885.6886     4315785.766     626886.3891    4315838.4255
     626911.4296     4315942.863
#Sta/Elev= 30
       0  657.02    3.07  653.18    9.21  644.39   12.28  640.69   15.35  639.53
   18.43  637.81    21.5  635.56   24.57  633.72   27.64  632.23   33.78   629.8
   36.85  628.94   39.92  628.36   46.06  627.82    52.2   626.6   55.11  626.21
   58.02  626.16   78.35  626.17   95.89  626.87  113.44  627.09   146.2  626.86
  167.68  626.17  170.74  626.24  173.81  626.92  183.02  629.75  192.22  633.45
  195.29  633.71  210.63  641.05  219.84  646.09  222.91  646.36  241.32  656.25
#Mann= 3 , 0 , 0
       0      .1       0    52.2    .041       0  173.81      .1       0
Bank Sta=52.2,173.81
XS Rating Curve= 0 ,0
Exp/Cntr=0.3,0.1

Type RM Length L Ch R = 1 ,17228.96,85.43,91.44,102.24
XS GIS Cut Line= 3
      626767.004    4315718.4104     626790.3864    4315782.4792
     626841.1682    4315946.6731
#Sta/Elev= 30
       0  658.15   11.86  653.58   14.83  652.77   17.79   652.6   20.76  651.82
   23.72   650.3   26.69  647.97   29.65     646   38.55  641.89   41.51  640.18
   47.45  635.73   50.41  634.98   53.38  632.04   56.34  630.03   59.31  628.83
    68.2  626.27   71.27  625.59   77.41  625.28   95.26  625.39  132.65  626.23
  172.55  626.12  181.76  625.74  184.83  626.51  194.03  629.27   197.1  629.68
  200.17  630.59  212.45  638.44  227.79  649.37  230.86  649.59  240.07  656.97
#Mann= 3 , 0 , 0
       0      .1       0    68.2    .041       0  184.83      .1       0
Bank Sta=68.2,184.83
XS Rating Curve= 0 ,0
Exp/Cntr=0.3,0.1

Type RM Length L Ch R = 1 ,17137.52,93.35,91.9,88.75
XS GIS Cut Line= 6
     626698.3179     4315715.816     626709.2202      4315810.75
     626710.3205    4315841.5158     626714.6168    4315864.0174
     626714.2861    4315889.4836     626728.7295    4315957.2521
#Sta/Elev= 30
       0  657.39   17.92  653.43   26.88  650.94   32.85   650.1   53.75  643.41
   56.74  642.64   59.72  642.51   62.71  641.56    65.7  640.36   80.63  630.93
    86.6  628.47   89.59  628.23   95.56  626.05  101.16  624.78  115.15   624.6
  134.93  624.66  140.66  626.54  143.52  626.94  174.72  627.33  180.75  627.11
   192.8  625.09  207.86  625.68  210.87  626.53   216.9  630.64  222.92  635.79
  225.93  639.02  234.97  650.98  237.99  653.14     241  654.66  244.01     658
#Mann= 3 , 0 , 0
       0      .1       0   95.56    .041       0  140.66      .1       0
Bank Sta=95.56,140.66
XS Rating Curve= 0 ,0
Exp/Cntr=0.3,0.1

Type RM Length L Ch R = 1 ,17045.62,92.23,90.98,91.96
XS GIS Cut Line= 5
     626616.9584    4315742.2743     626616.1696    4315831.7161
     626621.7282    4315850.5166     626624.9591    4315867.3985
     626634.8178    4315966.5092
#Sta/Elev= 30
       0  648.25    8.94  645.98   17.89  644.29   20.87  642.99    32.8  635.72
   35.78  634.48   38.76  633.75   41.74  633.24   44.72  633.24    47.7  632.56
   53.67  629.27   56.65  628.04   77.52  627.04   83.48  625.42   86.46  624.55
   92.25  624.08  117.64  624.77  123.37   625.7  129.26  626.65   153.4  626.34
  165.47  626.03  177.55  624.67   186.6  625.89  195.66  628.23  201.69  631.38
  207.73  635.39  210.75  637.99   219.8  647.36  222.82  648.86  225.84  649.64
#Mann= 3 , 0 , 0
       0      .1       0   83.48    .041       0  123.37      .1       0
Bank Sta=83.48,123.37
XS Rating Curve= 0 ,0
Exp/Cntr=0.3,0.1

Type RM Length L Ch R = 1 ,16954.64,74.6,91.44,104.45
XS GIS Cut Line= 4
     626514.9834    4315720.6115     626526.6829    4315840.3493
     626534.0566    4315878.8782     626534.8271    4315940.2161
#Sta/Elev= 30
       0  647.96   15.04  643.41   18.05  642.68   21.05   642.5   48.12  634.26
   51.13  634.26   72.18  627.21   75.19  626.68    78.2  626.59  111.28  627.02
  114.29  626.87   117.3  626.28  120.31  625.39  126.34  623.78  129.36  623.54
   153.3  623.84  159.54  624.96   162.6  625.09  168.74  624.93  184.07  624.17
  187.14  624.57  190.21  625.73  193.27  627.07  196.34  628.95  199.41  629.25
  202.48  631.45  208.61  637.17  214.74  644.21  217.81   647.5  220.88  650.25
#Mann= 3 , 0 , 0
       0      .1       0  120.31    .041       0  159.54      .1       0
Bank Sta=120.31,159.54
XS Rating Curve= 0 ,0
Exp/Cntr=0.3,0.1

Type RM Length L Ch R = 1 ,16863.2 ,84.97,91.44,89.36
XS GIS Cut Line= 4
     626497.1239    4315713.9969     626449.1017    4315829.2336
      626446.345    4315845.0563     626420.8433    4315898.9833
#Sta/Elev= 30
       0  648.37    3.04   647.7   12.18  644.84   18.27   642.8   30.45  638.47
   33.49   637.7   36.54  637.37   45.67  634.03   51.76  631.56   57.85  629.43
   63.94  627.15   66.99  626.42   73.08  625.88   94.39  626.47  109.62  626.32
  115.71  625.94   130.2  624.37  135.55   623.7  138.23  623.66   140.9  623.45
  170.73  623.36  173.71  623.61   176.7  624.83  179.68  627.19  182.66  630.13
  188.63  637.05  191.61  640.25  194.59  643.03  197.57  645.59  200.56     648
#Mann= 3 , 0 , 0
       0      .1       0   130.2    .041       0   176.7      .1       0
Bank Sta=130.2,176.7
XS Rating Curve= 0 ,0
Exp/Cntr=0.3,0.1

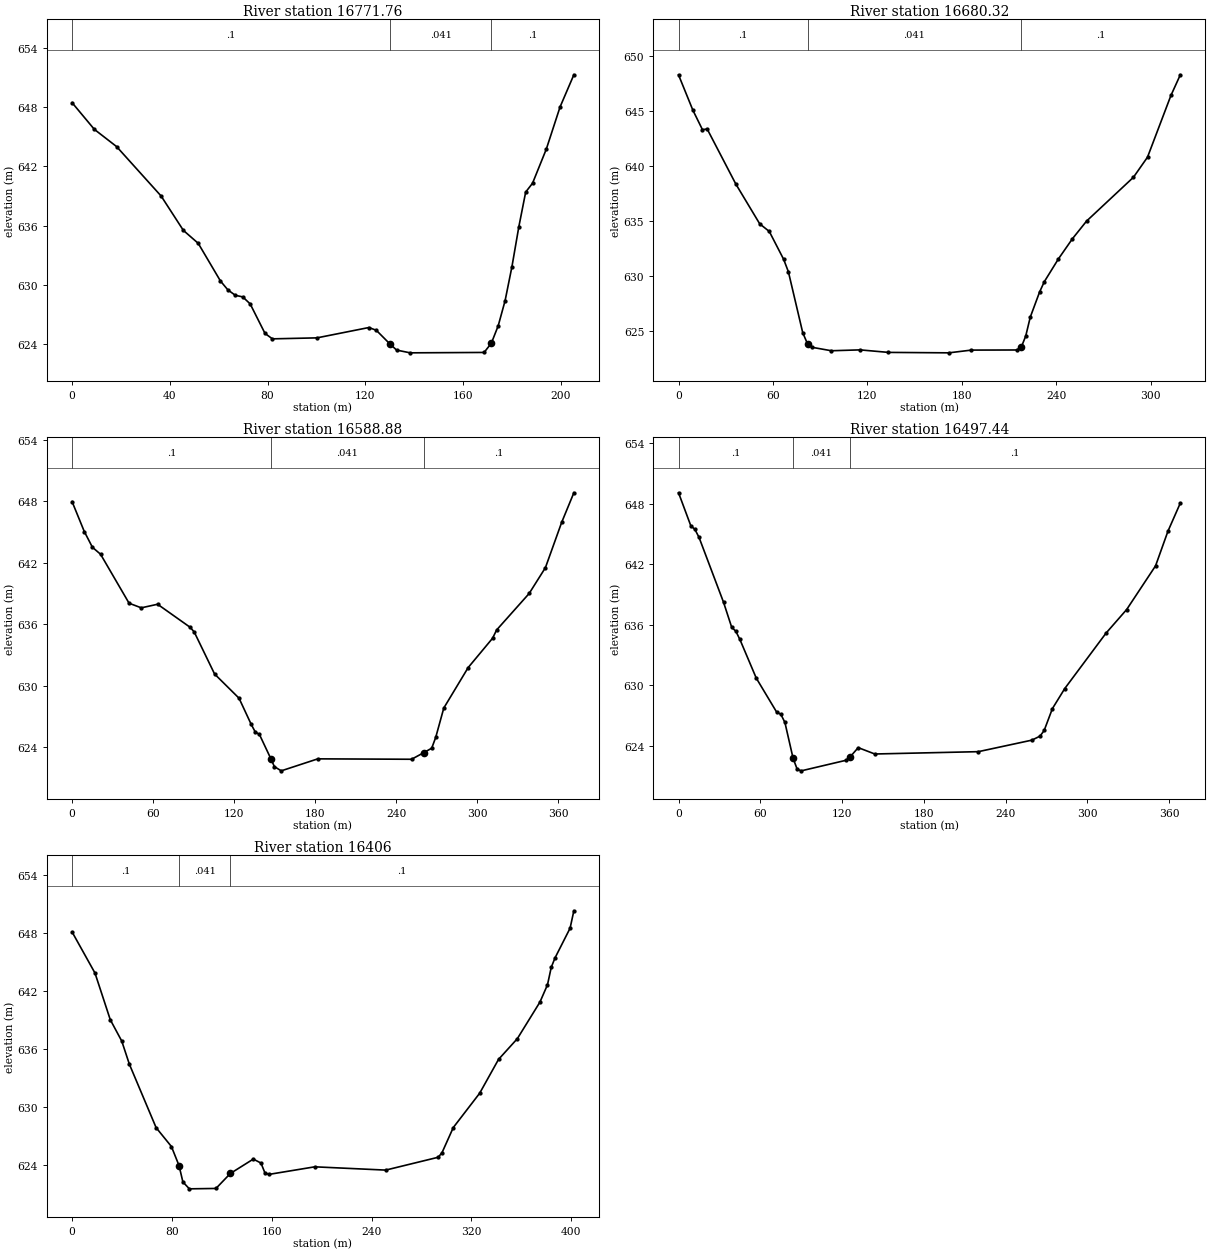
Type RM Length L Ch R = 1 ,16771.76,82.37,91.44,111.69
XS GIS Cut Line= 6
     626421.7175    4315682.9083      626370.388    4315796.3591
       626362.63    4315807.8365      626353.402    4315828.0843
     626342.3434    4315856.5692     626346.3111    4315870.1014
#Sta/Elev= 30
       0  648.48    9.11  645.77   18.22  644.02   36.45     639   45.56  635.51
   51.63   634.2   60.74  630.37   63.78  629.47   66.82  628.92   69.85  628.76
   72.89  628.05   78.97  625.05      82   624.5  100.23   624.6  121.49  625.65
  124.52  625.37  130.06  623.99  132.83  623.36  138.38  623.08  168.65  623.12
  171.61  624.06  174.42  625.83  177.23  628.37  180.04  631.83  182.85  635.87
  185.66   639.4  188.47   640.3   194.1  643.76  199.74  648.05  205.38  651.31
#Mann= 3 , 0 , 0
       0      .1       0  130.06    .041       0  171.61      .1       0
Bank Sta=130.06,171.61
XS Rating Curve= 0 ,0
Exp/Cntr=0.3,0.1

Type RM Length L Ch R = 1 ,16680.32,111.41,91.44,42.95
XS GIS Cut Line= 6
     626346.9726    4315659.7572      626296.117    4315763.2393
     626263.6523    4315790.1129     626241.1438    4315812.0443
     626247.1722    4315846.0936     626340.2257    4315866.7941
#Sta/Elev= 30
       0  648.28     9.1  645.07   15.17   643.3   18.21  643.35   36.41  638.34
   51.58  634.72   57.65  634.03   66.75   631.5   69.79  630.36   78.89  624.82
   81.93   623.8   84.96  623.48    97.1  623.17   115.3  623.25  133.37  623.02
  171.73  622.98  186.02  623.23  214.81  623.24  217.69  623.48  220.57  624.51
  223.45  626.23  229.41  628.53  232.39  629.46  241.33  631.53  250.26  633.37
   259.2  634.97  288.99  638.96  297.93  640.79  312.82  646.41  318.78  648.29
#Mann= 3 , 0 , 0
       0      .1       0   81.93    .041       0  217.69      .1       0
Bank Sta=81.93,217.69
XS Rating Curve= 0 ,0
Exp/Cntr=0.3,0.1

Type RM Length L Ch R = 1 ,16588.88,95.8,91.44,77.04
XS GIS Cut Line= 6
      626185.722    4315588.6636     626204.6332     4315732.135
     626202.7377      4315763.08     626211.8659    4315798.7988
     626244.5786    4315852.1097      626339.432    4315868.7785
#Sta/Elev= 30
       0  647.96    9.04  645.04   15.07   643.5    21.1  642.82   42.21  638.04
   51.25  637.59   63.31  637.94   87.43  635.69   90.45  635.23  105.52  631.13
  123.61  628.77  132.65  626.21  135.67  625.46  138.68  625.24  147.25  622.84
  149.79  622.09  154.88  621.68  181.94  622.85  251.38  622.81  260.31  623.45
  266.27  623.89  269.25  624.95  275.21  627.81  293.26  631.76  311.32  634.62
  314.33  635.43  338.41  638.99  350.45  641.51  362.48  645.93  371.51  648.82
#Mann= 3 , 0 , 0
       0      .1       0  147.25    .041       0  260.31      .1       0
Bank Sta=147.25,260.31
XS Rating Curve= 0 ,0
Exp/Cntr=0.3,0.1

Type RM Length L Ch R = 1 ,16497.44,102.18,91.44,15.68
XS GIS Cut Line= 6
      626080.153      4315670.42     626115.4893    4315759.7468
     626119.1292    4315776.8251     626140.0362    4315824.5318
     626210.3283    4315851.3953     626336.1067    4315870.1644
#Sta/Elev= 30
       0  649.09    9.01  645.82   12.01  645.46   15.01  644.68   33.02  638.24
   39.03  635.75   42.03  635.37   45.03  634.55   57.04  630.72   72.05  627.34
   75.05  627.14   78.05  626.33   84.05  622.78   87.06  621.69   90.06  621.53
  122.72  622.57  125.76  622.89  131.85  623.83  144.03   623.2  219.98  623.43
  259.22  624.57  265.28  624.97  268.31  625.53  274.36   627.7  283.44  629.69
  313.72  635.18  328.86  637.52  350.06  641.85  359.14  645.28  368.23  648.07
#Mann= 3 , 0 , 0
       0      .1       0   84.05    .041       0  125.76      .1       0
Bank Sta=84.05,125.76
XS Rating Curve= 0 ,0
Exp/Cntr=0.3,0.1

Type RM Length L Ch R = 1 ,16406   ,91.15,91.44,54.55
XS GIS Cut Line= 6
     625966.5746    4315764.2794     626067.7779    4315829.7639
      626122.679    4315824.1415     626132.9885     4315831.472
      626209.852    4315856.1578     626341.6148    4315873.0912
#Sta/Elev= 30
       0  648.12   18.37  643.86   30.62  639.03   39.81  636.82   45.93  634.42
   67.37  627.85   79.62   625.9   85.74  623.92   88.81  622.23   94.01  621.52
  115.31  621.56  126.84  623.11  145.23   624.6  151.37  624.19  154.43  623.21
   157.5  623.01  194.52   623.8  251.33  623.46  293.43  624.79  296.45  625.26
  305.51  627.87  326.64  631.42  341.74  634.92  356.83  637.07  374.95  640.86
  380.99  642.65  384.01  644.46  387.02  645.43   399.1  648.51  402.12  650.31
#Mann= 3 , 0 , 0
       0      .1       0   85.74    .041       0  126.84      .1       0
Bank Sta=85.74,126.84
XS Rating Curve= 0 ,0
Exp/Cntr=0.3,0.1

River Reach=Dry Fork        ,8
Reach XY= 30
     626036.5238    4315877.6759     626039.8343    4315880.7694
     626077.8286    4315888.8973     626108.0969    4315891.0882
     626127.1469    4315916.4883     626223.9846    4316007.7697
      626283.516    4316043.4885     626434.3288    4316053.0135
     626555.7728    4316020.4697     626636.7355    4316052.2198
     626749.4482    4316117.3074     626807.7818    4316153.7404
     626946.4141    4316234.1347     626999.4799     4316268.914
     627118.5427    4316369.7204     627164.2151    4316429.8569
      627174.899    4316449.8893     627205.0616    4316472.1144
     627217.7616    4316493.5457     627216.1741    4316511.0082
     627225.1964    4316528.3862     627249.0099    4316560.2004
     627263.2957     4316598.847     627273.3242    4316673.7273
     627227.2866    4316750.7212     627220.9366    4316869.7839
     627203.4741    4316954.7153      627159.024    4317059.4905
     627120.9239    4317130.9282     627113.7622    4317175.3165

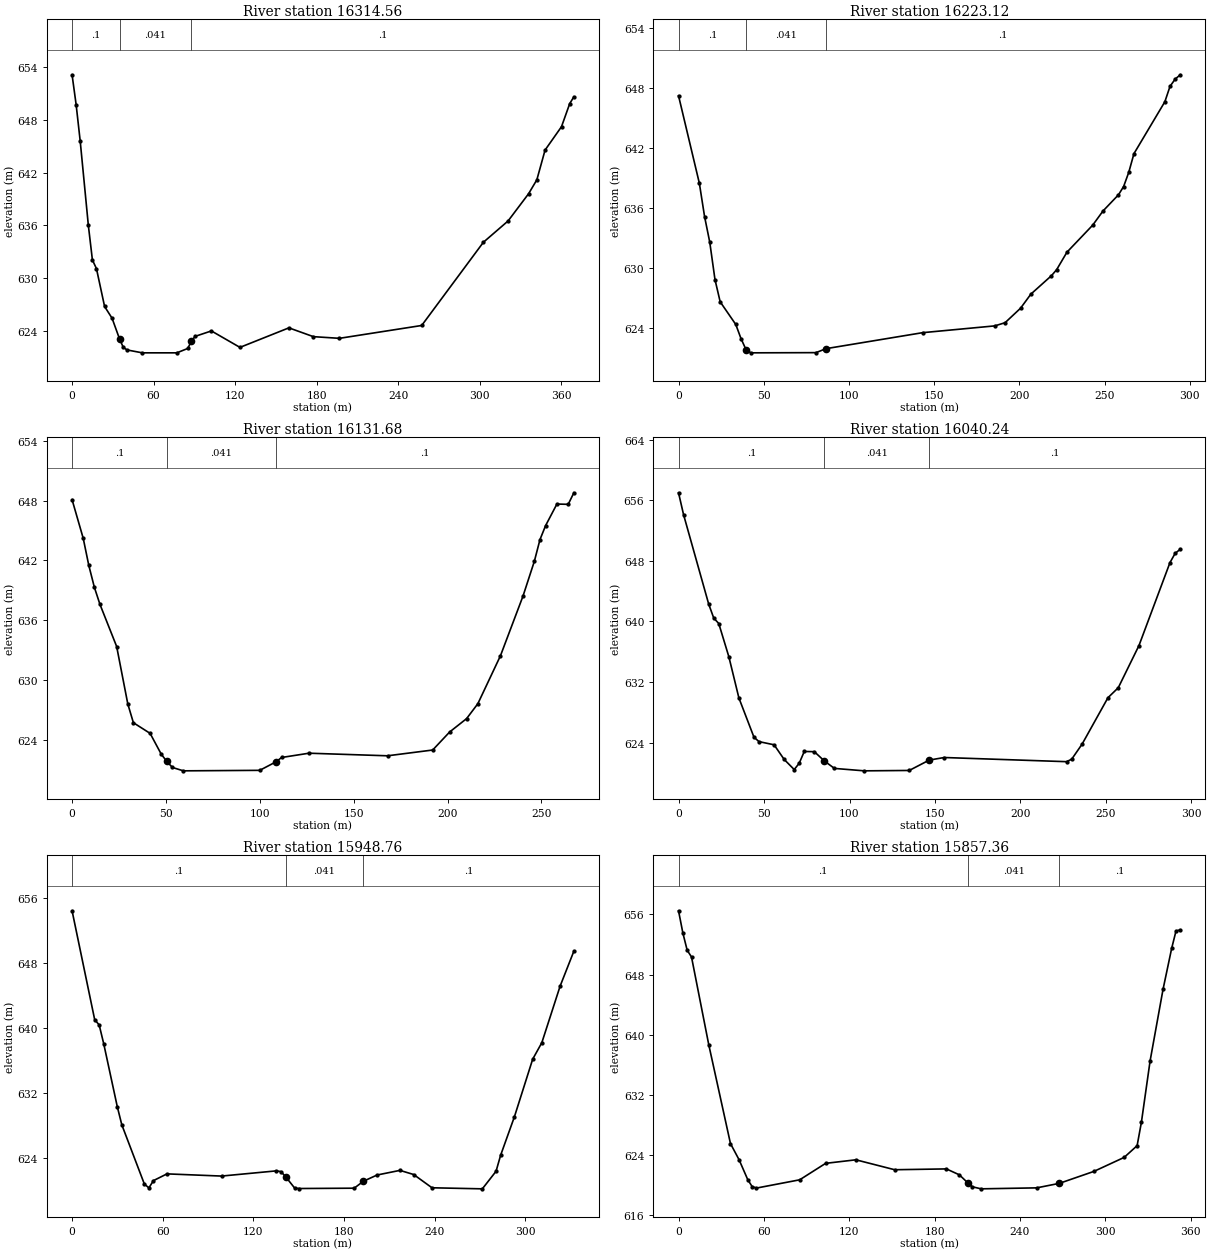
Type RM Length L Ch R = 1 ,16314.56,75.96,91.44,29.45
XS GIS Cut Line= 6
     626050.2413    4315943.2255     626050.2536    4315919.2815
     626069.7667    4315855.7813     626156.7486    4315860.4115
     626165.3476    4315855.1199       626345.75    4315876.4184
#Sta/Elev= 30
       0  653.13    2.99  649.74    5.99  645.59   11.97  636.03   14.97  632.08
   17.96  631.09   23.94  626.79   29.46  625.45   34.97  623.09   37.72  622.14
   40.48  621.85   51.72  621.52   77.12  621.52   85.18  622.02   87.86  622.85
   90.55  623.39  102.56  624.01  123.59  622.14  159.63  624.36  177.66  623.36
  196.83  623.17  257.39  624.63   302.8  634.09  320.97  636.51   336.1  639.61
  342.16  641.19  348.21  644.57  360.32  647.23  366.38  649.86  369.41  650.62
#Mann= 3 , 0 , 0
       0      .1       0   34.97    .041       0   87.86      .1       0
Bank Sta=34.97,87.86
XS Rating Curve= 0 ,0
Exp/Cntr=0.3,0.1

Type RM Length L Ch R = 1 ,16223.12,94.28,91.44,96.28
XS GIS Cut Line= 5
     626093.2717    4315967.3083     626120.4157    4315938.3425
     626126.9323    4315933.2078     626181.8724    4315874.9235
     626348.0872    4315879.9461
#Sta/Elev= 30
       0  647.26   12.21   638.5   15.27  635.16   18.32  632.59   21.38  628.85
   24.43  626.62   33.59  624.35   36.64  622.94    39.7  621.79   42.46  621.51
   80.62  621.53   86.56  621.93  143.21  623.53  185.54  624.21  191.58  624.53
  200.65  625.98   206.7  627.39  218.79  629.24  221.82  629.84  227.86  631.59
  242.98   634.3  249.03  635.72   258.1  637.34  261.12  638.17  264.15   639.6
  267.17  641.46  285.31  646.66  288.33   648.2  291.36  648.93  294.38  649.36
#Mann= 3 , 0 , 0
       0      .1       0    39.7    .041       0   86.56      .1       0
Bank Sta=39.7,86.56
XS Rating Curve= 0 ,0
Exp/Cntr=0.3,0.1

Type RM Length L Ch R = 1 ,16131.68,95.05,91.44,70.54
XS GIS Cut Line= 6
       626149.84    4316043.6682      626188.599    4316002.6717
     626211.6495    4315976.6435     626236.8591    4315956.9075
     626259.2223    4315932.9657     626357.6122    4315881.0045
#Sta/Elev= 30
       0  648.09    5.94  644.21    8.91  641.49   11.88  639.29   14.85  637.58
   23.75  633.35   29.69  627.58   32.66   625.7   41.57  624.63   47.51  622.54
   50.48  621.81   53.45  621.21   59.27  620.87   99.95  620.92  108.68  621.78
  111.59  622.21  126.21  622.64  168.03  622.38  192.08  622.96  201.11  624.77
  210.13  626.11  216.14  627.61  228.17  632.42   240.2  638.42  246.22   641.9
  249.22  644.08  252.23  645.49  258.24  647.65  264.26  647.62  267.27  648.78
#Mann= 3 , 0 , 0
       0      .1       0   50.48    .041       0  108.68      .1       0
Bank Sta=50.48,108.68
XS Rating Curve= 0 ,0
Exp/Cntr=0.3,0.1

Type RM Length L Ch R = 1 ,16040.24,105.54,91.47,71.22
XS GIS Cut Line= 6
     626207.7417    4316127.9257     626248.0245    4316081.0943
     626263.9559    4316059.9349     626283.4611    4316027.4261
     626307.9528    4315974.3347     626363.9622    4315881.0045
#Sta/Elev= 30
       0     657    2.94  654.11   17.65  642.29   20.59  640.45   23.53  639.73
   29.42  635.35    35.3   629.9   44.12  624.71   47.07  624.13   55.89  623.71
   61.77  621.78   67.66  620.44    70.6  621.28   73.54  622.83   79.43   622.8
   85.32  621.57   91.18  620.59  108.67  620.27  134.94  620.32  146.63  621.69
   155.4  622.03  226.97  621.48  229.99  621.82  236.04   623.8  251.16  629.93
   257.2  631.25   269.3  636.82  287.44  647.78  290.46     649  293.49  649.55
#Mann= 3 , 0 , 0
       0      .1       0   85.32    .041       0  146.63      .1       0
Bank Sta=85.32,146.63
XS Rating Curve= 0 ,0
Exp/Cntr=0.3,0.1

Type RM Length L Ch R = 1 ,15948.76,120.03,91.41,83.35
XS GIS Cut Line= 4
     626306.1205    4316202.4733      626348.454    4316133.6815
     626363.8275    4316084.5983     626378.7789    4315885.2378
#Sta/Elev= 30
       0  654.42   14.96  641.04   17.95  640.38   20.94  638.08   29.92  630.34
   32.91  628.11   47.87  620.81   50.86  620.35   53.85  621.24   62.82  622.07
   98.93   621.8  135.24  622.44  138.27  622.35   141.3  621.73  147.35  620.32
  150.38  620.27  186.73  620.31  192.79  621.16  201.88  621.93  217.02   622.5
  226.11  621.99  238.23  620.36  271.55  620.23  280.63  622.39  283.66  624.36
  292.75  629.07  304.87  636.17  310.93   638.2  323.04  645.16  332.13  649.45
#Mann= 3 , 0 , 0
       0      .1       0   141.3    .041       0  192.79      .1       0
Bank Sta=141.3,192.79
XS Rating Curve= 0 ,0
Exp/Cntr=0.3,0.1

Type RM Length L Ch R = 1 ,15857.36,75.81,91.44,88.66
XS GIS Cut Line= 6
      626438.386    4316265.2679     626479.6611    4316157.3176
     626472.5173    4316081.9112     626459.8757    4316057.5069
     626451.8522    4316028.3013     626463.4457    4315925.4546
#Sta/Elev= 30
       0  656.49    3.04  653.54    6.08  651.24    9.12  650.35   21.29  638.64
    36.5  625.54   42.58  623.38   48.66  620.74    51.7  619.83   54.74  619.62
   85.16  620.72  103.41  622.91  124.66  623.38  151.93  622.06  188.29  622.17
  197.42  621.38  203.53  620.28  206.59  619.79  212.69  619.52  251.75  619.65
  267.71  620.25     292  621.84  313.25   623.7  322.36  625.26   325.4  628.41
  331.47  636.52  340.58  646.05  346.65   651.5  349.69   653.8  352.73  653.95
#Mann= 3 , 0 , 0
       0      .1       0  203.53    .041       0  267.71      .1       0
Bank Sta=203.53,267.71
XS Rating Curve= 0 ,0
Exp/Cntr=0.3,0.1

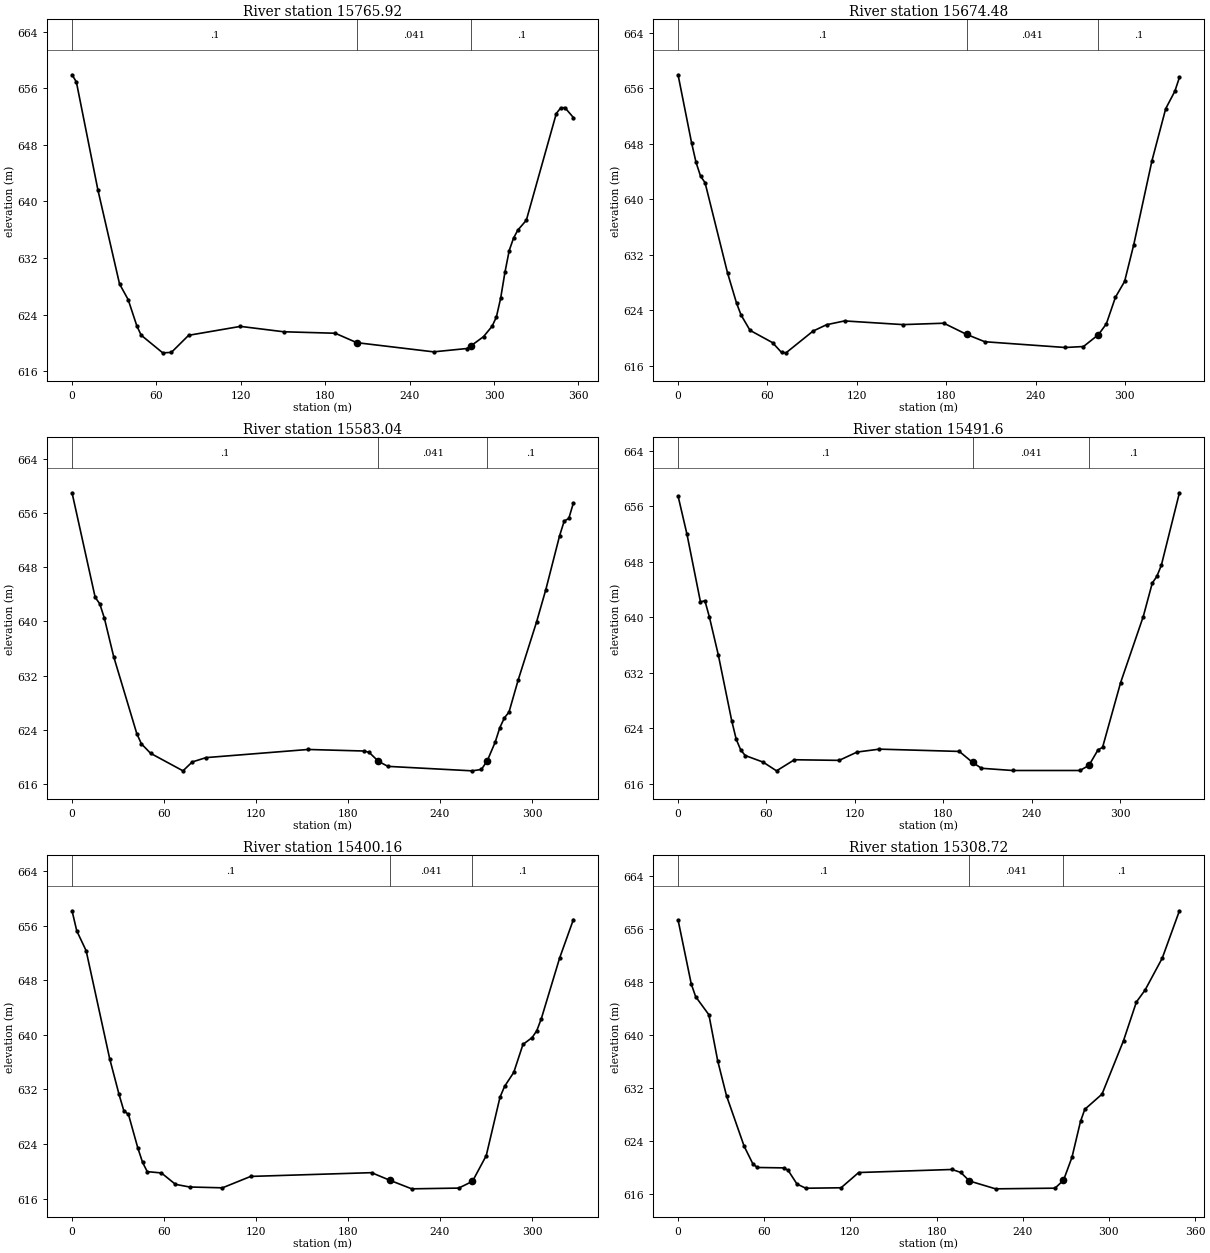
Type RM Length L Ch R = 1 ,15765.92,42.5,91.44,102.68
XS GIS Cut Line= 5
     626493.0323    4316284.0376     626551.7699    4316132.2988
     626551.3652    4316046.8061     626541.0415    4316006.8018
     626530.0299    4315940.7621
#Sta/Elev= 30
       0   657.9    3.07  656.89   18.42  641.58   33.77  628.32   39.91   626.1
   46.05   622.4   49.12  621.08   64.47  618.58   70.61  618.64   82.89  621.06
  119.73  622.32  150.43  621.56  187.14  621.35   202.4  620.02  257.06  618.72
  280.67  619.19  283.62  619.57  292.56  620.87  298.65  622.34  301.69  623.64
  304.74  626.31  307.78  629.97  310.82  633.05  313.87  634.79  316.91  635.93
  322.99  637.33   344.3  652.42  347.34   653.2  350.38  653.26  356.47  651.85
#Mann= 3 , 0 , 0
       0      .1       0   202.4    .041       0  283.62      .1       0
Bank Sta=202.4,283.62
XS Rating Curve= 0 ,0
Exp/Cntr=0.3,0.1

Type RM Length L Ch R = 1 ,15674.48,84.11,91.44,94.65
XS GIS Cut Line= 5
     626517.6193    4316291.7048     626580.3008    4316147.7218
     626609.9248    4316094.2552     626628.1343    4316056.6933
     626656.1309    4315985.3019
#Sta/Elev= 30
       0  657.95    9.06  648.16   12.08  645.32    15.1  643.34   18.12   642.4
   33.22  629.39   39.26  625.04   42.28  623.33   48.32  621.11   63.42  619.34
   69.46  617.93   72.48  617.87    90.6     621   99.66  621.92  111.74  622.47
     151  621.94  178.43  622.14  193.71  620.53  205.94  619.47   259.9  618.64
  272.17  618.78  282.21  620.49  287.51  622.04  293.64  625.89  299.78  628.16
  305.91  633.45  318.18  645.59  327.39  653.07  333.52  655.58  336.59  657.57
#Mann= 3 , 0 , 0
       0      .1       0  193.71    .041       0  282.21      .1       0
Bank Sta=193.71,282.21
XS Rating Curve= 0 ,0
Exp/Cntr=0.3,0.1

Type RM Length L Ch R = 1 ,15583.04,59.84,91.44,91.66
XS GIS Cut Line= 5
     626580.0168    4316314.0495     626650.0738     4316190.871
     626676.5796    4316153.3275     626714.7524    4316087.2235
     626747.6021    4316033.4345
#Sta/Elev= 30
       0  658.95   15.08  643.54   18.09  642.58   21.11  640.44   27.14  634.81
   42.21  623.46   45.23  621.94   51.26  620.54   72.36  617.96   78.39  619.27
   87.44  619.91  153.96  621.11  190.72  620.88  193.77  620.68  199.88  619.36
  205.98  618.62  260.95  617.96     267  618.16  270.91  619.48     276  622.19
  279.01  624.32  282.01  625.77  285.01  626.62  291.01  631.36  303.02  639.93
  309.02  644.67  318.02  652.62  321.02  654.78  324.02  655.17  327.03  657.46
#Mann= 3 , 0 , 0
       0      .1       0  199.88    .041       0  270.91      .1       0
Bank Sta=199.88,270.91
XS Rating Curve= 0 ,0
Exp/Cntr=0.3,0.1

Type RM Length L Ch R = 1 ,15491.6 ,127.69,91.44,90.76
XS GIS Cut Line= 6
     626638.9878    4316335.2252     626704.2077    4316218.5642
     626745.4827    4316155.5932     626778.4637    4316158.3468
     626797.9855    4316127.0901     626826.6394    4316072.8059
#Sta/Elev= 30
       0   657.5    6.08  651.95   15.19  642.23   18.23  642.38   21.26  640.04
   27.34  634.55   36.45  625.05   39.49  622.39   42.53  620.87   45.56  620.06
   57.71  619.11   66.83  617.85   78.98  619.45  109.35  619.36   121.5  620.56
  136.67  620.98  190.88  620.65  199.91  619.06  205.94  618.22     227   617.9
  272.75   617.9  278.89  618.64  285.03  620.88   288.1  621.23  300.38  630.59
  315.72   640.1  321.86  644.94  324.93  645.89     328   647.5  340.28  657.96
#Mann= 3 , 0 , 0
       0      .1       0  199.91    .041       0  278.89      .1       0
Bank Sta=199.91,278.89
XS Rating Curve= 0 ,0
Exp/Cntr=0.3,0.1

Type RM Length L Ch R = 1 ,15400.16,84.93,91.44,89.22
XS GIS Cut Line= 5
      626750.265    4316393.8134     626818.3271    4316277.3194
      626845.315    4316226.5884     626872.3314    4316180.0012
     626911.4992    4316109.3272
#Sta/Elev= 30
       0  658.19    3.07  655.25     9.2  652.33   24.53  636.53   30.66  631.27
   33.73  628.92    36.8  628.34   42.93  623.41      46  621.32   49.06  619.96
   58.26  619.77   67.46   618.1   76.66  617.71   98.12  617.59  116.52  619.26
  195.37  619.81  207.34  618.69  221.57  617.44  252.22  617.55   261.2  618.54
  270.18  622.31  279.16  630.88  282.15  632.46  288.13  634.51  294.12   638.6
   300.1  639.61   303.1   640.6  306.09  642.37  318.06  651.28  327.04  656.91
#Mann= 3 , 0 , 0
       0      .1       0  207.34    .041       0   261.2      .1       0
Bank Sta=207.34,261.2
XS Rating Curve= 0 ,0
Exp/Cntr=0.3,0.1

Type RM Length L Ch R = 1 ,15308.72,92.39,91.44,103.84
XS GIS Cut Line= 6
     626815.1006    4316432.2241     626890.4427    4316316.5605
      626914.237    4316283.5895     626957.3824    4316217.7589
     626961.5496      4316198.49     627001.5438    4316138.7709
#Sta/Elev= 30
       0  657.41     9.2  647.74   12.27  645.82   21.47   643.1   27.61  636.15
   33.74  630.88   46.01  623.28   52.15  620.59   55.22  620.07   73.62  620.01
   76.69  619.62   82.82  617.57   88.96  616.94   113.5  617.01  125.77  619.31
  190.81  619.77  196.86  619.32  202.92  618.03  221.08  616.85  262.46  616.95
  268.37  618.14  274.27   621.6  280.22  627.02  283.21  628.84  295.19  631.13
  310.17   639.2  319.15  645.03  325.14  646.81  337.12  651.63   349.1  658.78
#Mann= 3 , 0 , 0
       0      .1       0  202.92    .041       0  268.37      .1       0
Bank Sta=202.92,268.37
XS Rating Curve= 0 ,0
Exp/Cntr=0.3,0.1

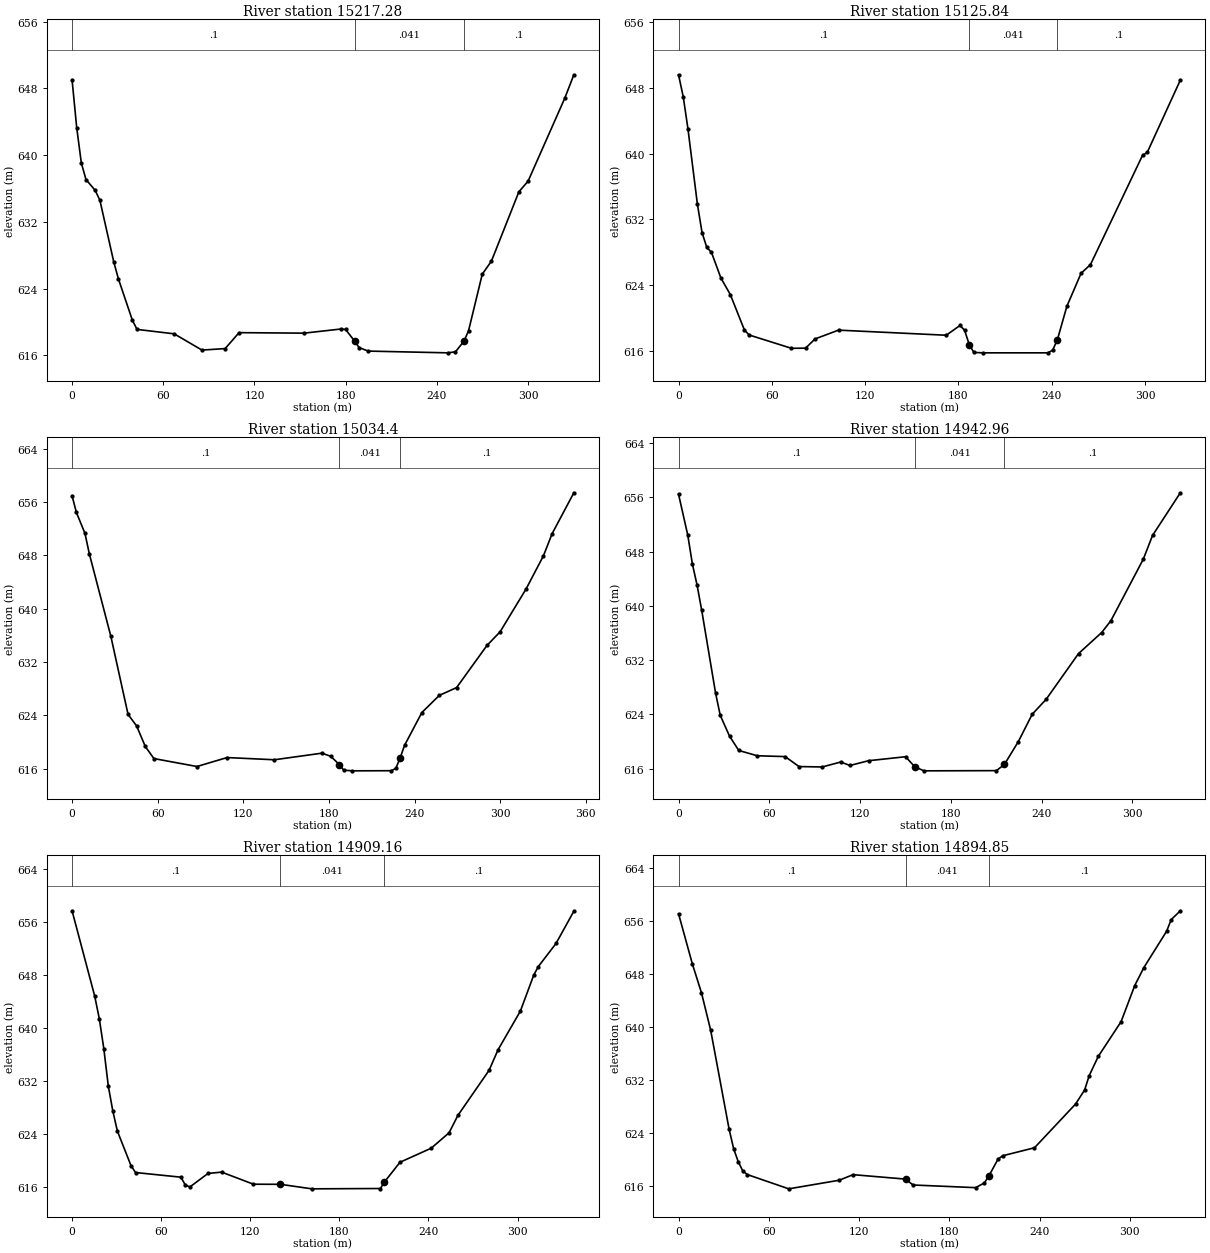
Type RM Length L Ch R = 1 ,15217.28,83.03,91.44,91.03
XS GIS Cut Line= 6
       626901.16    4316473.4474     626994.5499    4316323.0664
     627011.1692     4316298.663     627032.4537    4316273.6768
     627043.5337    4316262.9104     627092.7458    4316205.8932
#Sta/Elev= 30
       0  649.03    3.05  643.29     6.1  639.05    9.16  637.07   15.26  635.76
   18.31  634.58   27.47  627.16   30.52  625.14   39.68   620.2   42.73   619.1
   67.15  618.57   85.46  616.62  100.72   616.8  109.87  618.71   152.6  618.65
  177.02  619.15  179.97  619.09  185.88   617.7  188.83  616.93  194.74   616.5
  247.09  616.29  252.24  616.41  257.83  617.69  260.84  618.93  269.88  625.72
  275.91  627.29  293.98   635.6  300.01  636.87  324.11   646.8  330.14  649.63
#Mann= 3 , 0 , 0
       0      .1       0  185.88    .041       0  257.83      .1       0
Bank Sta=185.88,257.83
XS Rating Curve= 0 ,0
Exp/Cntr=0.3,0.1

Type RM Length L Ch R = 1 ,15125.84,77.26,91.44,96.53
XS GIS Cut Line= 4
     626956.9395    4316507.1041        627056.9    4316385.6011
     627101.2482    4316334.0334     627168.5818    4316263.8274
#Sta/Elev= 30
       0  649.59    3.03  646.91    6.05  643.03    12.1   633.9   15.13  630.39
   18.15  628.62   21.18     628   27.23  624.89   33.28  622.88   42.36  618.56
   45.39  617.96   72.62  616.34   81.69  616.36   87.75  617.48  102.87  618.55
  172.12  617.93  180.99  619.12  183.95  618.53  186.91  616.79  189.87  615.84
  195.78  615.79  237.51  615.79  240.55  616.11  243.59  617.39  249.67  621.44
  258.79  625.45  264.87  626.52  298.31  639.79  301.35  640.15  322.63  648.94
#Mann= 3 , 0 , 0
       0      .1       0  186.91    .041       0  243.59      .1       0
Bank Sta=186.91,243.59
XS Rating Curve= 0 ,0
Exp/Cntr=0.3,0.1

Type RM Length L Ch R = 1 ,15034.4 ,80.48,91.44,99
XS GIS Cut Line= 3
     626990.9046    4316545.8068     627111.0893    4316444.9903
     627265.2659    4316326.0968
#Sta/Elev= 30
       0  656.91    3.02  654.43    9.05  651.27   12.07  648.24   27.15  635.88
   39.22  624.16   45.25  622.42   51.28  619.36   57.32  617.54   87.49  616.35
   108.6  617.69  141.79  617.36  175.12  618.35  181.21  617.88  187.29  616.64
  190.33   615.8  196.42   615.7   223.8  615.72  226.84  616.08  229.88  617.64
  232.92  619.51  245.09  624.44  257.26     627  269.43  628.18  290.72   634.5
  299.85  636.52   318.1  642.96  330.27  647.93  336.35  651.25  351.57  657.37
#Mann= 3 , 0 , 0
       0      .1       0  187.29    .041       0  229.88      .1       0
Bank Sta=187.29,229.88
XS Rating Curve= 0 ,0
Exp/Cntr=0.3,0.1

Type RM Length L Ch R = 1 ,14942.96,12.61,33.8,45.14
XS GIS Cut Line= 4
     627049.9116    4316576.6228     627223.8672    4316473.5382
     627236.1879    4316468.5293     627339.0053    4316414.2337
#Sta/Elev= 30
       0  656.45    6.13  650.39    9.19  646.14   12.25  643.07   15.32  639.35
   24.51  627.13   27.57  623.88    33.7  620.82   39.83   618.7   52.08  617.92
   70.47   617.8   79.66  616.33   94.98  616.27  107.23     617  113.36  616.49
  125.61  617.19  150.12  617.78  156.25  616.28  162.38   615.7  210.19  615.73
  215.51  616.65  224.68  620.01  233.86  624.04  243.04  626.23  264.46  632.97
  279.76  636.07  285.88  637.82   307.3  646.88  313.42  650.38  331.78  656.66
#Mann= 3 , 0 , 0
       0      .1       0  156.25    .041       0  215.51      .1       0
Bank Sta=156.25,215.51
XS Rating Curve= 0 ,0
Exp/Cntr=0.3,0.1

Type RM Length L Ch R = 1 ,14909.16,14.9,14.31,11.34
XS GIS Cut Line= 6
     627055.3026    4316584.8853     627161.8104    4316525.1743
      627191.973    4316521.4701     627223.1939    4316510.8867
     627255.4731    4316509.2992     627362.2555    4316454.3825
#Sta/Elev= 30
       0  657.65   15.26  644.76   18.32  641.39   21.37  636.86   24.42  631.17
   27.47  627.41   30.53   624.4   39.68   619.2   42.74  618.16   73.26  617.46
   76.31  616.26   79.37  615.99   91.58  618.03  100.74  618.22   122.1   616.4
  140.34  616.38  161.48   615.7  207.64  615.75  210.18  616.69   220.8  619.71
  241.82  621.83  253.83  624.15  259.83  626.79  280.84   633.6  286.85  636.69
  301.86  642.51  310.86  647.94  313.86  649.21  325.87  652.72  337.88  657.59
#Mann= 3 , 0 , 0
       0      .1       0  140.34    .041       0  210.18      .1       0
Bank Sta=140.34,210.18
XS Rating Curve= 0 ,0
Exp/Cntr=0.3,0.1

Type RM Length L Ch R = 1 ,14894.85,47.07,43.33,35.04
XS GIS Cut Line= 6
     627066.8802    4316596.3981     627167.6313    4316538.9326
      627198.323    4316535.2285     627226.3689    4316524.6451
     627251.2398    4316520.9409     627364.9755    4316457.4666
#Sta/Elev= 30
       0  657.06    9.16  649.51   15.26  645.12   21.37  639.47   33.58  624.58
   36.63  621.59   39.68  619.64   42.73  618.23   45.78  617.69   73.26  615.54
  106.83  616.84  115.99  617.68  150.87  617.01  155.89  616.12  197.46  615.72
  203.28  616.43  206.31   617.5  212.37  620.03   215.4  620.53   236.6  621.74
  263.86  628.33  269.92  630.46  272.95  632.62  279.01  635.54  294.15  640.77
  303.24  646.23   309.3  648.94  324.44  654.43  327.47  656.18  333.53  657.51
#Mann= 3 , 0 , 0
       0      .1       0  150.87    .041       0  206.31      .1       0
Bank Sta=150.87,206.31
XS Rating Curve= 0 ,0
Exp/Cntr=0.3,0.1

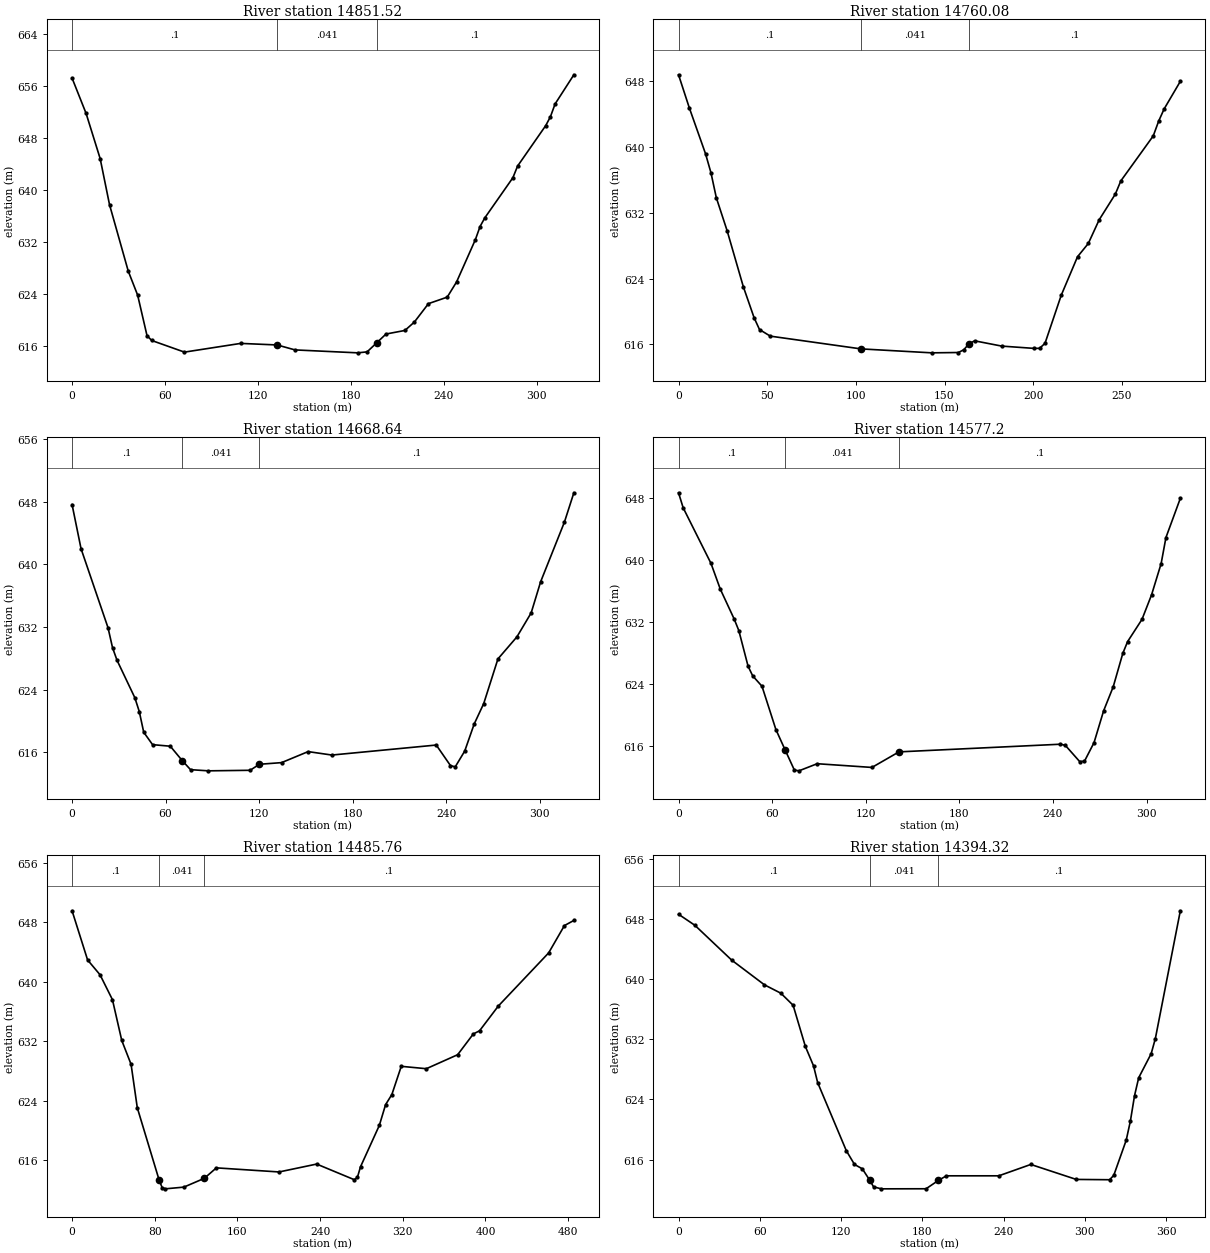
Type RM Length L Ch R = 1 ,14851.52,82.35,91.44,97.17
XS GIS Cut Line= 6
     627092.6129    4316629.8959     627200.4556    4316575.2391
     627225.6328    4316569.3598     627258.0074    4316557.3924
     627294.9121    4316535.9484     627385.7718    4316494.4289
#Sta/Elev= 30
       0  657.22    9.07  651.78   18.14  644.84   24.18  637.76   36.27  627.55
   42.32  623.87   48.36  617.65   51.38   616.9   72.54  615.11  108.81  616.45
  132.39  616.21  143.88  615.45  184.32     615  190.42  615.15  196.52  616.52
  202.61  617.89  214.81  618.44  220.91  619.73  230.01  622.56  242.12  623.56
  248.17   625.9  260.28  632.39  263.31  634.41  266.34  635.73   284.5  641.91
  287.53   643.7  305.69  649.92  308.72  651.28  311.74  653.25  323.85  657.73
#Mann= 3 , 0 , 0
       0      .1       0  132.39    .041       0  196.52      .1       0
Bank Sta=132.39,196.52
XS Rating Curve= 0 ,0
Exp/Cntr=0.3,0.1

Type RM Length L Ch R = 1 ,14760.08,64.11,91.44,127.93
XS GIS Cut Line= 5
      627146.588    4316692.3377     627229.1707    4316653.3058
      627255.077     4316651.124      627283.116    4316647.3688
     627412.4646    4316601.1325
#Sta/Elev= 30
       0  648.79    6.09  644.76   15.22  639.19   18.27  636.89   21.31  633.84
    27.4  629.83   36.54  623.02   42.63  619.24   45.67  617.81   51.76  617.01
   102.9  615.46   142.8  614.98  157.84  615.02  160.89  615.36  163.94  616.11
     167  616.44  182.26   615.8  200.58  615.52  203.63  615.53  206.68  616.14
  215.84  621.99     225  626.66   231.1  628.28  237.21  631.15  246.36  634.29
  249.42  635.88  267.73  641.36  270.78  643.16  273.84  644.63  282.99  647.99
#Mann= 3 , 0 , 0
       0      .1       0   102.9    .041       0  163.94      .1       0
Bank Sta=102.9,163.94
XS Rating Curve= 0 ,0
Exp/Cntr=0.3,0.1

Type RM Length L Ch R = 1 ,14668.64,96.29,91.44,59.59
XS GIS Cut Line= 6
     627157.1457     4316718.345     627191.6988    4316716.3785
     627222.3055    4316722.7637     627269.7648    4316749.0802
     627298.0615    4316762.4161      627468.322    4316752.6628
#Sta/Elev= 30
       0  647.66    5.77  642.01   23.07  631.91   25.96  629.36   28.84  627.75
   40.29  622.95   43.14  621.18   45.98  618.54   51.66  616.95   63.03  616.75
   70.75   614.9   76.02  613.75   87.49   613.6  114.27  613.67  120.22  614.44
  134.44  614.65   151.5  616.06  166.73  615.62  233.73   616.9  242.86  614.27
  245.91  614.11     252  616.13  258.09   619.6  264.18   622.2  273.32  627.92
   285.5  630.74  294.63   633.8  300.72  637.79  315.95   645.4  322.04  649.17
#Mann= 3 , 0 , 0
       0      .1       0   70.75    .041       0  120.22      .1       0
Bank Sta=70.75,120.22
XS Rating Curve= 0 ,0
Exp/Cntr=0.3,0.1

Type RM Length L Ch R = 1 ,14577.2 ,89.65,91.44,133.36
XS GIS Cut Line= 5
     627146.4803     4316808.447     627217.0874     4316818.575
     627269.6441    4316821.7127     627301.4041    4316821.2154
     627467.2637    4316816.1629
#Sta/Elev= 30
       0  648.68    2.97  646.74    20.8  639.56   26.75  636.24   35.66  632.37
   38.64  630.88   44.58  626.27   47.55  625.02    53.5  623.68   62.41  618.09
   68.36  615.44   74.25  612.85   77.18  612.75   88.88  613.67  123.98  613.19
  141.31   615.2  244.86  616.19  247.93  616.05  257.15  613.95  260.22  613.99
  266.37   616.4  272.51  620.51  278.66  623.61  284.81  627.93  287.88  629.45
   297.1  632.32  303.24  635.49  309.39  639.54  312.46   642.9  321.68  647.96
#Mann= 3 , 0 , 0
       0      .1       0   68.36    .041       0  141.31      .1       0
Bank Sta=68.36,141.31
XS Rating Curve= 0 ,0
Exp/Cntr=0.3,0.1

Type RM Length L Ch R = 1 ,14485.76,91.58,91.44,89.5
XS GIS Cut Line= 6
     627120.8532    4316884.0376     627219.7177     4316910.933
      627249.441     4316920.021     627427.8316    4317029.2793
     627505.2755    4317063.9016     627555.0767    4317093.4349
#Sta/Elev= 30
       0  649.51   15.02   642.9   27.04  640.91   39.06  637.56   48.07  632.08
   57.09  628.87    63.1  623.03   84.13  613.36   87.13   612.3   90.14  612.13
  108.14  612.36  127.92  613.54  139.63  614.95  200.27   614.4  236.65  615.46
  273.03  613.36  276.06  613.67  279.09   615.1  297.28  620.66  303.34  623.45
  309.41  624.81   318.5   628.6  342.76  628.28  373.05  630.16   388.2  632.95
  394.26  633.38  412.44  636.71  461.11  643.85  476.35  647.52  485.49  648.21
#Mann= 3 , 0 , 0
       0      .1       0   84.13    .041       0  127.92      .1       0
Bank Sta=84.13,127.92
XS Rating Curve= 0 ,0
Exp/Cntr=0.3,0.1

Type RM Length L Ch R = 1 ,14394.32,83.72,91.44,95.76
XS GIS Cut Line= 6
     627036.4329    4316934.7847     627158.9422    4316986.3323
     627172.0725    4316990.6884     627235.7605     4317017.225
     627280.0335    4317040.9336     627355.8318    4317112.8153
#Sta/Elev= 30
       0  648.61   12.08  647.14   39.27  642.51   63.44  639.23   75.52  638.12
   84.58  636.52   93.64  631.04   99.68  628.46  102.71  626.24  123.85   617.2
  129.89  615.37  135.68  614.79  141.21  613.26  143.98  612.39  149.75  612.13
  182.74  612.14  191.74  613.24  197.74  613.86  236.42  613.86  260.05  615.37
  293.61  613.38  318.19  613.34  321.27  613.91  330.48  618.59  333.56  621.13
  336.63  624.51   339.7  626.89  348.92  630.09  351.99  632.09  370.43  649.07
#Mann= 3 , 0 , 0
       0      .1       0  141.21    .041       0  191.74      .1       0
Bank Sta=141.21,191.74
XS Rating Curve= 0 ,0
Exp/Cntr=0.3,0.1