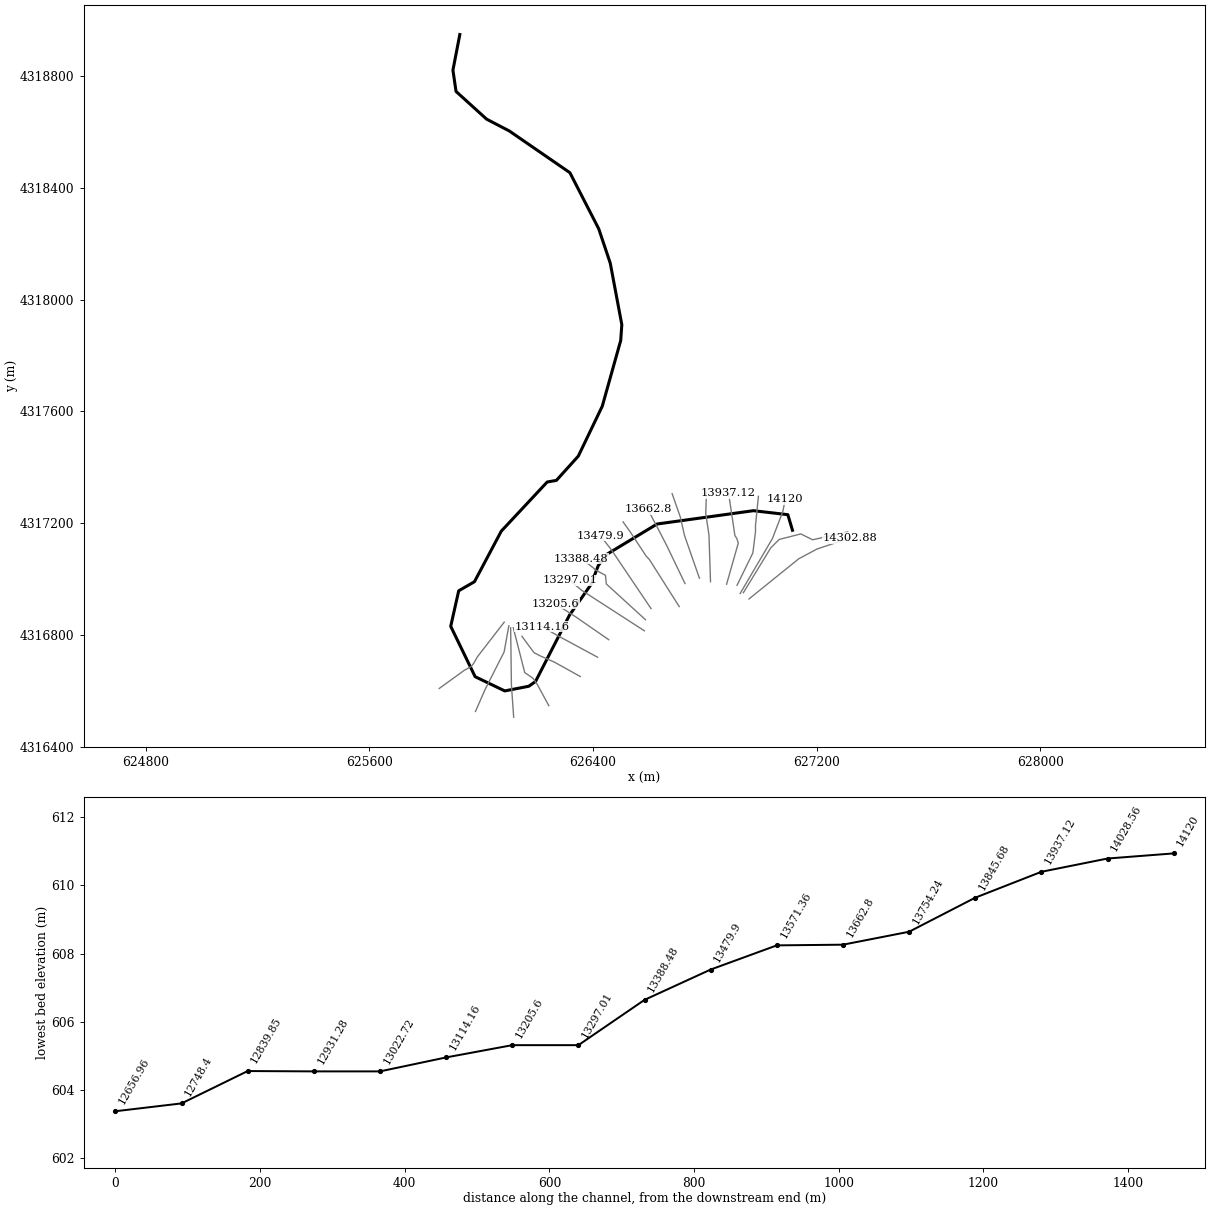
HEC-RAS study RedCreek.prj: RedCreek

--- RedCreek.g01 (geometry) --- (continued)

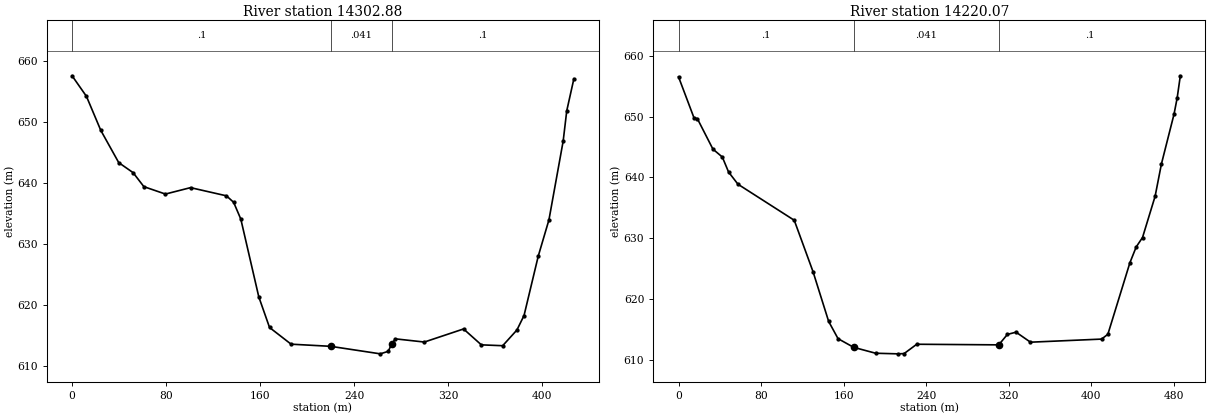
Type RM Length L Ch R = 1 ,14302.88,95.93,82.81,35.39
XS GIS Cut Line= 4
     626958.1161     4316929.493     627136.3556    4317073.3528
     627201.3526    4317108.0178     627319.0085    4317147.5101
#Sta/Elev= 30
       0  657.53   12.22  654.17   24.43   648.6    39.7  643.32   51.92  641.68
   61.08  639.39    79.4  638.18  100.78  639.23  131.32  637.89  137.43  636.83
  143.54  634.08  158.81  621.37  167.97  616.35   186.3  613.62  219.89  613.27
  262.17  612.04  268.95  612.45  272.02  613.73  275.09  614.49  299.65  613.97
  332.99  616.11  348.12  613.51  366.28  613.37  378.39  615.94  384.44  618.31
  396.55  628.04  405.63  633.96  417.74  646.86  420.77   651.8  426.82  657.03
#Mann= 3 , 0 , 0
       0      .1       0  219.89    .041       0  272.02      .1       0
Bank Sta=219.89,272.02
XS Rating Curve= 0 ,0
Exp/Cntr=0.3,0.1

Type RM Length L Ch R = 1 ,14220.07,17.35,100.07,92.06
XS GIS Cut Line= 6
     626938.0077     4316951.718     627035.9989    4317112.1993
     627066.4623    4317142.4706     627143.5036    4317162.1203
      627186.018    4317141.1712     627311.2037    4317169.3779
#Sta/Elev= 30
       0  656.58   15.16  649.75    18.2  649.71   33.36  644.67   42.46  643.37
   48.52   640.9   57.62  638.89  112.21  632.95  130.41  624.48  145.57  616.28
  154.67  613.44  169.84  612.01   191.1  611.04  212.57  610.94  218.71  610.98
  230.98  612.52  310.49  612.42  318.88  614.14  327.28  614.51  341.27  612.86
  410.19  613.37   416.3  614.16  437.69  625.96   443.8  628.56  449.91  630.11
  462.13  636.91  468.24  642.23  480.46  650.43  483.52  653.12  486.57  656.76
#Mann= 3 , 0 , 0
       0      .1       0  169.84    .041       0  310.49      .1       0
Bank Sta=169.84,310.49
XS Rating Curve= 0 ,0
Exp/Cntr=0.3,0.1

River Reach=Dry Fork        ,7
Reach XY= 30
     627113.7622    4317175.3165     627097.1114    4317230.9409
     626974.0799    4317245.2284     626629.5917    4317197.6033
     626451.7913    4317090.4468     626419.2475    4317049.1718
     626393.0162     4316980.944     626316.0598    4316871.3714
     626194.7174    4316634.3442     626170.8033    4316617.3709
     626084.7183    4316600.6271     625978.7154    4316651.5022
     625891.4027    4316831.6838     625919.9778    4316958.6841
     625976.3341    4316991.2279     626072.3781    4317172.2033
     626236.5295    4317347.8642     626269.4022    4317353.5603
     626347.8099    4317440.4913      626433.535    4317619.0854
     626499.4164    4317854.0359     626503.3852    4317910.3922
     626462.1101    4318130.2614      626420.835    4318253.2929
     626317.6473    4318454.1121     626100.9184    4318603.3108
     626019.9905    4318645.4062     625910.4528    4318744.6252
     625899.3402    4318820.8253     625923.9652     4318948.156

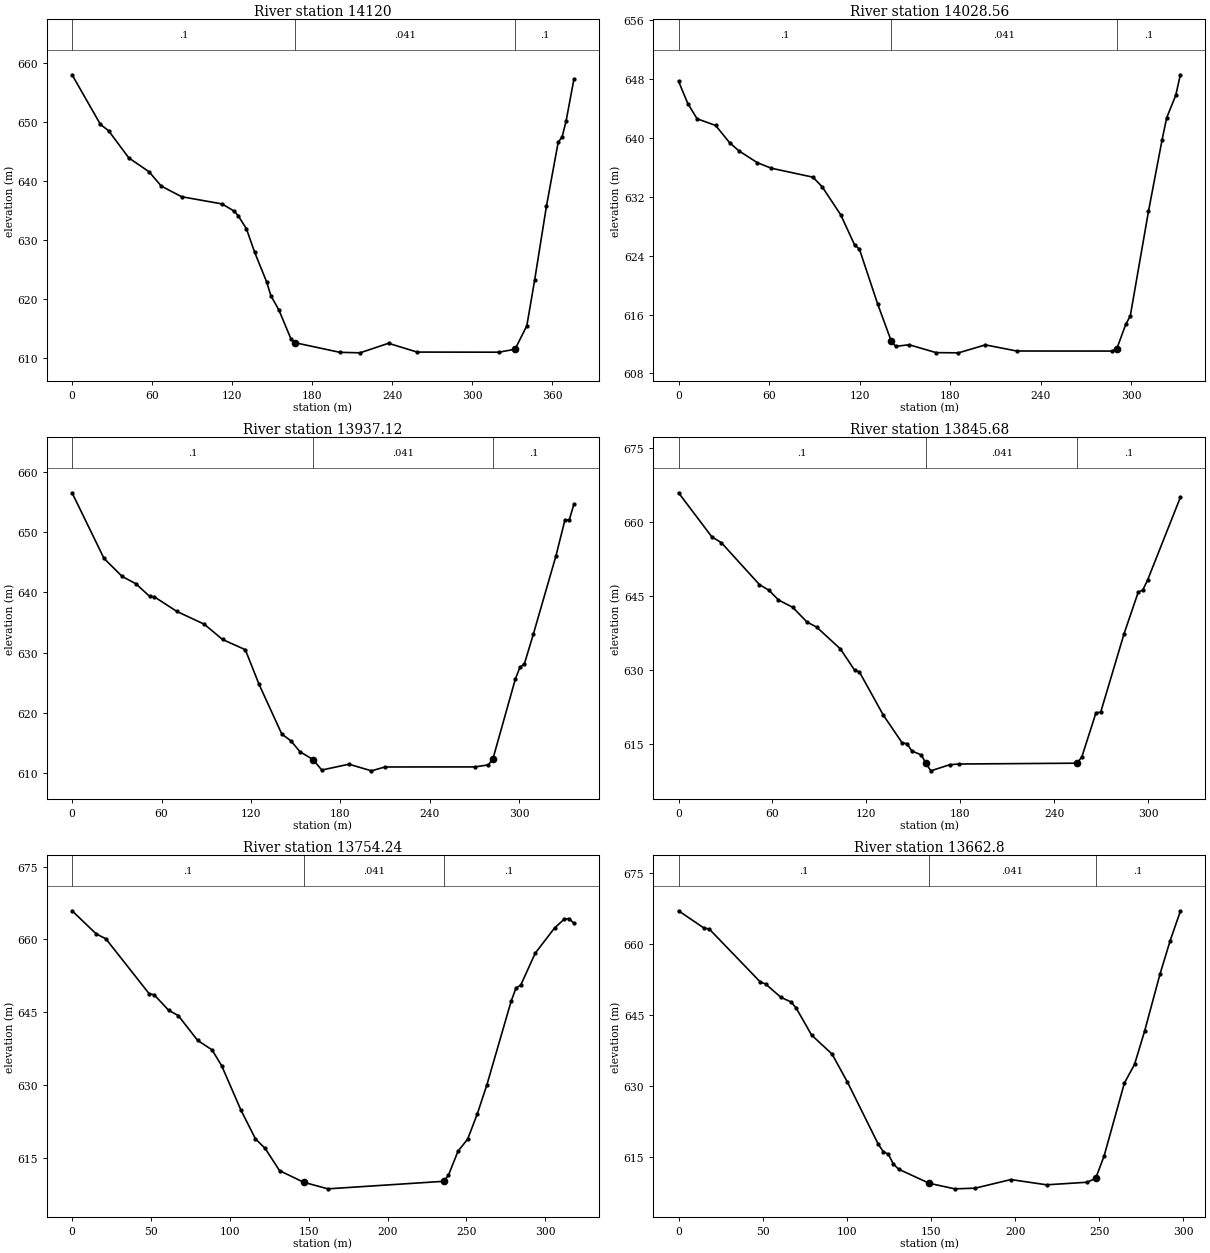
Type RM Length L Ch R = 1 ,14120   ,61.55,91.44,93.56
XS GIS Cut Line= 4
     626926.4939    4316948.9289     627042.0066    4317145.5493
     627079.3619    4317242.6734     627087.7537    4317285.9405
#Sta/Elev= 30
       0  658.08   21.28  649.66   27.36   648.6   42.57  643.98   57.77  641.63
   66.89  639.21   82.09  637.41   112.5  636.18  121.62  634.95  124.66  634.14
  130.74  631.96  136.82  628.02  145.95  622.92  148.99  620.65  155.07  618.19
  164.19  613.25  167.23  612.65  200.68  611.03  215.88  610.94  237.22  612.56
  258.65  611.07  319.86  611.05   332.1  611.55  340.92  615.54  346.79  623.29
  355.61  635.79  364.42  646.64  367.36  647.55   370.3  650.18  376.17  657.28
#Mann= 3 , 0 , 0
       0      .1       0  167.23    .041       0   332.1      .1       0
Bank Sta=167.23,332.1
XS Rating Curve= 0 ,0
Exp/Cntr=0.3,0.1

Type RM Length L Ch R = 1 ,14028.56,67.37,91.44,99.24
XS GIS Cut Line= 5
     626915.3814    4316978.2977     626972.1103    4317094.2374
     626981.5842    4317170.9752     626981.3926    4317191.6881
     626991.8957    4317296.7194
#Sta/Elev= 30
       0  647.72    6.15  644.68   12.29  642.61   24.59   641.7   33.81  639.37
   39.95  638.26   52.24  636.64   61.46  635.89   89.12  634.67   95.27  633.35
  107.56  629.54  116.78  625.43  119.85  624.92  132.05  617.41  140.97  612.42
  143.94  611.67  152.87  611.89  170.71  610.82  185.58  610.79  203.42  611.87
  224.15  611.04  287.43  611.03  290.44  611.29  296.47  614.65  299.49  615.82
  311.55  630.03   320.6  639.78  323.62  642.75  329.65  645.81  332.66  648.59
#Mann= 3 , 0 , 0
       0      .1       0  140.97    .041       0  290.44      .1       0
Bank Sta=140.97,290.44
XS Rating Curve= 0 ,0
Exp/Cntr=0.3,0.1

Type RM Length L Ch R = 1 ,13937.12,101.34,91.44,88.59
XS GIS Cut Line= 5
     626878.0751    4316982.2665     626919.8918     4317129.341
     626914.6002    4317146.0098     626907.8224     4317156.265
     626885.1059    4317308.4656
#Sta/Elev= 30
       0   656.5   21.41  645.62   33.64  642.62   42.81  641.42   51.99  639.33
   55.05  639.27   70.34  636.82   88.68  634.71  100.92  632.18  116.21  630.48
  125.38  624.76  140.67   616.5  146.79  615.37   152.9  613.56  161.65  612.27
  167.48  610.53   185.7   611.5  200.79   610.4  209.84  611.04  270.19  611.05
  279.24  611.39  282.26  612.37  297.35  625.64  300.36  627.55  303.38  628.13
  309.42  633.08   324.5  645.99  330.54  651.94  333.55  652.06  336.57  654.58
#Mann= 3 , 0 , 0
       0      .1       0  161.65    .041       0  282.26      .1       0
Bank Sta=161.65,282.26
XS Rating Curve= 0 ,0
Exp/Cntr=0.3,0.1

Type RM Length L Ch R = 1 ,13845.68,83.83,91.44,101.72
XS GIS Cut Line= 4
     626820.5943    4316991.0639     626815.0859    4317158.1656
     626803.4988    4317235.7995     626806.0421    4317310.5489
#Sta/Elev= 30
       0  665.92   21.28     657   27.36  655.82   51.68  647.33   57.76  646.19
   63.84  644.22   72.96  642.73   82.08  639.74   88.16  638.75  103.36  634.32
  112.47  630.01  115.51  629.66  130.71  620.96  142.87  615.28  145.91  615.16
  148.95  613.68  155.03  612.85  158.07  611.13  161.11  609.64  173.23  610.88
  179.27  611.02  254.66  611.19  257.65  612.53  266.63  621.41  269.62  621.51
  284.58  637.42  293.55  645.76  296.55  646.26  299.54  648.23  320.48  664.98
#Mann= 3 , 0 , 0
       0      .1       0  158.07    .041       0  254.66      .1       0
Bank Sta=158.07,254.66
XS Rating Curve= 0 ,0
Exp/Cntr=0.3,0.1

Type RM Length L Ch R = 1 ,13754.24,71.71,91.44,95.68
XS GIS Cut Line= 4
     626780.9067    4317003.7639     626727.4935    4317156.8946
     626712.5851    4317222.4185     626683.2752    4317306.1832
#Sta/Elev= 30
       0  665.91    15.3  661.15   21.42  660.14   48.96  648.79   52.02  648.62
    61.2  645.43   67.32  644.33   79.56  639.23   88.74  637.26   94.86  633.98
   107.1  624.83  116.28  618.93   122.4  616.97  131.58  612.37  146.88  609.99
  162.18  608.64   235.5  610.19  238.56   611.4  244.68   616.4   250.8  618.88
  256.92  624.09  263.04  630.12  278.34  647.26   281.4  649.97  284.46  650.61
  293.64  657.18  305.88  662.36     312  664.18  315.06  664.31  318.12  663.34
#Mann= 3 , 0 , 0
       0      .1       0  146.88    .041       0   235.5      .1       0
Bank Sta=146.88,235.5
XS Rating Curve= 0 ,0
Exp/Cntr=0.3,0.1

Type RM Length L Ch R = 1 ,13662.8 ,80.69,91.44,93.55
XS GIS Cut Line= 5
     626729.3128    4316984.7139     626664.7058    4317118.9823
     626621.6364    4317202.4841     626616.7303    4317211.0949
     626596.1752    4317251.5088
#Sta/Elev= 30
       0  667.02    15.2  663.35   18.25  663.17   48.65  651.95    51.7  651.56
   60.82  648.73    66.9  647.75   69.94  646.45   79.06  640.76   91.23  636.74
  100.35  630.84  118.59  617.77  121.64  616.13  124.68  615.58  127.72  613.48
  130.76  612.42     149  609.43  164.16  608.26  176.28   608.4   197.5  610.22
  218.71  609.11  242.96  609.66  247.91  610.49  252.87  615.15  264.96   630.6
  271.01  634.57  277.05  641.67  286.12  653.63  292.16  660.69  298.21  666.91
#Mann= 3 , 0 , 0
       0      .1       0     149    .041       0  247.91      .1       0
Bank Sta=149,247.91
XS Rating Curve= 0 ,0
Exp/Cntr=0.3,0.1

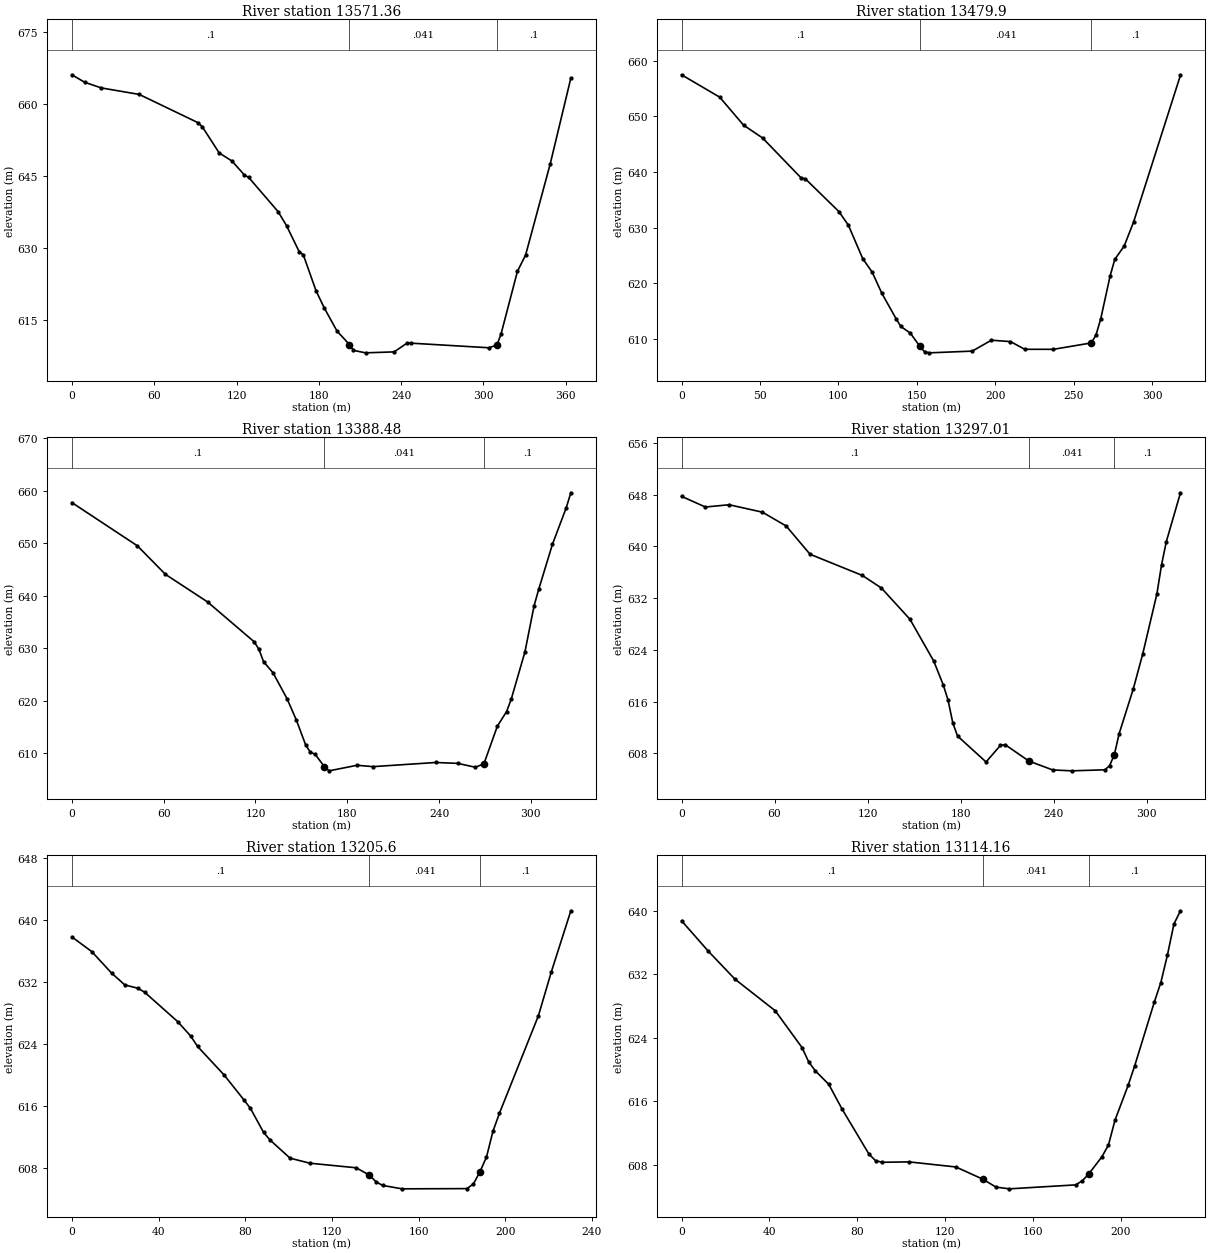
Type RM Length L Ch R = 1 ,13571.36,92.37,91.46,92.66
XS GIS Cut Line= 5
     626708.6753    4316902.1637     626601.9251    4317070.6437
     626589.9526    4317083.4741     626535.6697    4317166.0784
     626507.8207    4317205.0901
#Sta/Elev= 30
       0  666.13    9.21  664.58   21.48  663.39    49.1  662.04   92.05  656.14
   95.12  655.28   107.4  649.85   116.6  648.19  125.81  645.26  128.88  644.76
  150.36  637.63  156.49  634.71   165.7  629.31  168.77  628.61  177.97  621.17
  184.11  617.52  193.31  612.76  202.38  609.97   205.3  608.75  214.08  608.24
  234.97  608.44  243.96  610.19  246.95  610.26  303.86   609.3  309.85  609.84
  312.85  612.12  324.83   625.2  330.82  628.63   348.8  647.63  363.78  665.44
#Mann= 3 , 0 , 0
       0      .1       0  202.38    .041       0  309.85      .1       0
Bank Sta=202.38,309.85
XS Rating Curve= 0 ,0
Exp/Cntr=0.3,0.1

Type RM Length L Ch R = 1 ,13479.9 ,83.62,91.42,94.94
XS GIS Cut Line= 3
     626607.8688    4316895.0199     626465.2387    4317106.6067
     626426.2941    4317155.8669
#Sta/Elev= 30
       0  657.47    24.3  653.45   39.49  648.43   51.64  646.12   75.94  639.02
   78.98  638.76  100.25  632.91  106.32  630.46  115.43  624.47  121.51  622.01
  127.59  618.25   136.7  613.67  139.74  612.27  145.81  611.07  151.89   608.7
  154.93   607.7  157.96  607.53   185.3  607.84  197.45   609.8   209.6  609.55
  218.72  608.17  236.94  608.16  261.15  609.31  264.14  610.74  267.13  613.61
  273.11  621.31   276.1  624.32  282.08   626.7  288.06     631  317.97   657.4
#Mann= 3 , 0 , 0
       0      .1       0  151.89    .041       0  261.15      .1       0
Bank Sta=151.89,261.15
XS Rating Curve= 0 ,0
Exp/Cntr=0.3,0.1

Type RM Length L Ch R = 1 ,13388.48,77.09,91.47,90.68
XS GIS Cut Line= 6
      626588.025    4316855.3323     626448.0558    4316983.0554
     626444.8204    4317013.9453     626406.8876    4317034.6358
     626401.2648    4317040.7887     626358.5183    4317073.8204
#Sta/Elev= 30
       0  657.72   42.79  649.49   61.12  644.06   88.63  638.81  119.19   631.2
  122.25  629.77   125.3  627.41  131.42  625.33  140.59   620.4   146.7  616.32
  152.81  611.56  155.87  610.18  158.92  609.81  165.04  607.44  168.09  606.64
  186.43   607.7  196.78  607.44  237.86  608.23  252.26  608.06  263.78  607.32
  269.34  607.99  278.12  615.16  284.12  617.92  287.13  620.24  296.13  629.29
  302.13  638.09  305.13   641.2  314.14  649.81  323.14  656.74  326.14  659.59
#Mann= 3 , 0 , 0
       0      .1       0  165.04    .041       0  269.34      .1       0
Bank Sta=165.04,269.34
XS Rating Curve= 0 ,0
Exp/Cntr=0.3,0.1

Type RM Length L Ch R = 1 ,13297.01,91.87,91.41,93.43
XS GIS Cut Line= 3
     626584.0563    4316815.6448     626359.6922     4316960.501
      626317.673    4316995.7091
#Sta/Elev= 30
       0  647.74   15.35  646.09    30.7  646.44   52.18  645.29   67.53  643.15
   82.88  638.79  116.65  635.51  128.93  633.57  147.35  628.74  162.69  622.28
  168.83   618.6   171.9  616.28  174.97  612.75  178.04  610.69  196.46  606.68
  205.67  609.23  208.74  609.36  224.09  606.82  239.44  605.45  251.71  605.31
  273.15  605.47   276.2  606.13  279.25  607.83  282.29  611.04  291.43  617.96
  297.52  623.37  306.65  632.63   309.7  637.19  312.75  640.74  321.88  648.29
#Mann= 3 , 0 , 0
       0      .1       0  224.09    .041       0  279.25      .1       0
Bank Sta=224.09,279.25
XS Rating Curve= 0 ,0
Exp/Cntr=0.3,0.1

Type RM Length L Ch R = 1 ,13205.6 ,96.46,91.44,92.59
XS GIS Cut Line= 3
     626456.5073    4316783.8223     626338.5629     4316865.398
      626265.472    4316912.3371
#Sta/Elev= 30
       0  637.85    9.15  635.96   18.31  633.18   24.41  631.65   30.51  631.22
   33.56  630.71   48.82  626.91   54.92  625.01   57.97  623.71   70.18  620.04
   79.33  616.82   82.38  615.71   88.48  612.59   91.54  611.59  100.69  609.27
  109.84  608.62   131.2  608.03   137.3  607.08  140.36  606.22  143.41  605.75
  152.39  605.31  182.35  605.34  185.34  605.96  188.34  607.53  191.33  609.41
  194.33  612.75  197.32  615.08   215.3  627.67  221.29  633.36  230.27  641.23
#Mann= 3 , 0 , 0
       0      .1       0   137.3    .041       0  188.34      .1       0
Bank Sta=137.3,188.34
XS Rating Curve= 0 ,0
Exp/Cntr=0.3,0.1

Type RM Length L Ch R = 1 ,13114.16,90.13,91.44,94.16
XS GIS Cut Line= 3
     626416.6138    4316721.1356     626269.2287    4316800.8532
     626217.7694     4316830.982
#Sta/Elev= 30
       0  638.77   12.19  634.93   24.37  631.39   42.65  627.42   54.84  622.78
   57.89  620.97   60.93  619.83   67.03  618.14   73.12     615    85.3  609.35
   88.35   608.5    91.4   608.3  103.58  608.35  124.91  607.71   137.1  606.18
  143.19  605.17  149.28  604.95  179.49  605.45  182.47  605.96  185.45  606.84
  191.41  608.99   194.4  610.48  197.38  613.62  203.34  617.99  206.32  620.45
  215.27   628.5  218.25  630.98  221.23  634.42  224.21  638.36  227.19  640.03
#Mann= 3 , 0 , 0
       0      .1       0   137.1    .041       0  185.45      .1       0
Bank Sta=137.1,185.45
XS Rating Curve= 0 ,0
Exp/Cntr=0.3,0.1

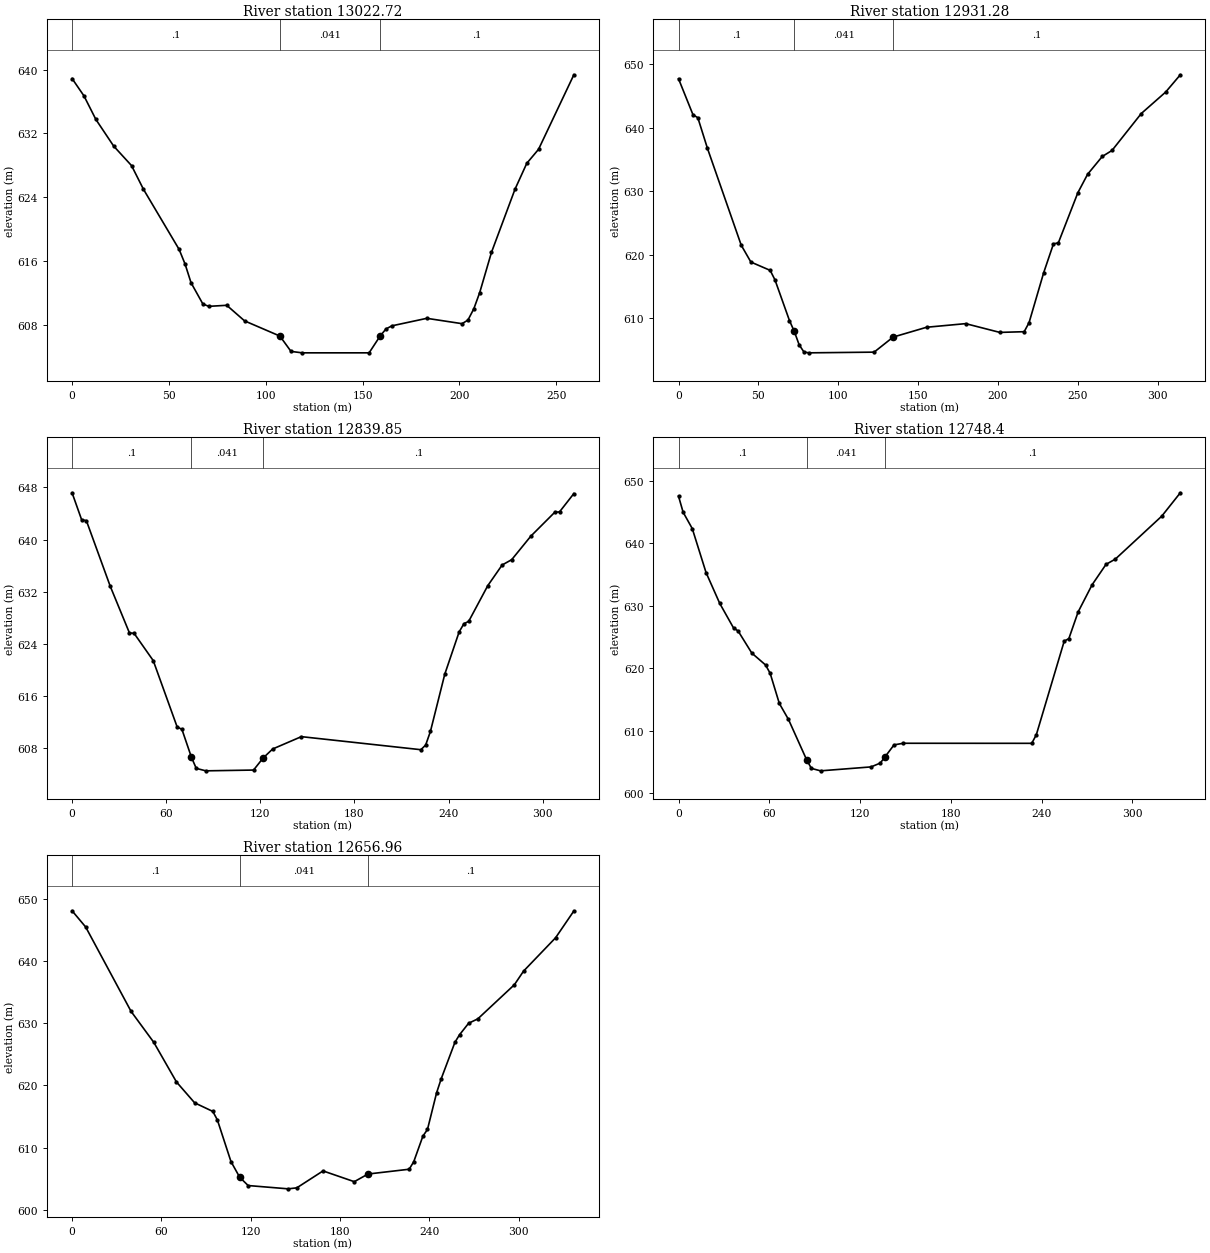
Type RM Length L Ch R = 1 ,13022.72,107.93,91.44,81.48
XS GIS Cut Line= 6
     626354.6393    4316652.1932     626263.3621    4316702.9491
     626226.2885    4316719.6957     626216.0457    4316723.7451
      626189.295    4316737.4145     626146.0401    4316796.1336
#Sta/Elev= 30
       0  638.87    6.14   636.7   12.29  633.75    21.5  630.41   30.72  627.97
   36.86  625.01   55.29  617.48   58.36  615.65   61.44  613.31   67.58  610.64
   70.65  610.36   79.87  610.49   89.08  608.54  107.31  606.64  113.06  604.72
  118.81  604.54  153.39  604.54  159.15  606.67  162.15  607.54  165.16  607.92
  183.18  608.86  201.38  608.19  204.42  608.64  207.46  610.05   210.5  612.08
  216.57  617.11  228.73  625.02  234.81  628.26  240.88  630.01  259.12  639.34
#Mann= 3 , 0 , 0
       0      .1       0  107.31    .041       0  159.15      .1       0
Bank Sta=107.31,159.15
XS Rating Curve= 0 ,0
Exp/Cntr=0.3,0.1

Type RM Length L Ch R = 1 ,12931.28,101.83,91.42,74.27
XS GIS Cut Line= 5
     626242.2657    4316547.9212     626200.4232    4316624.8802
     626185.3966    4316646.0515     626156.0971    4316666.3968
     626115.2655    4316826.2634
#Sta/Elev= 30
       0  647.71    9.06  642.04   12.08  641.58   18.12  636.74   39.27  621.49
   45.31  618.84   57.39  617.53   60.41  616.02   69.47  609.62    72.5  607.91
   75.52  605.81   78.54  604.67   81.56  604.54  122.48  604.65  134.37  607.02
  155.34  608.57  179.79  609.14  201.18  607.76  216.45  607.87  219.51   609.3
  228.67  617.17  234.79  621.71  237.84  621.86  250.06  629.76  256.17  632.67
  265.34  635.47  271.45  636.42  289.79  642.24  305.06  645.62  314.23  648.34
#Mann= 3 , 0 , 0
       0      .1       0    72.5    .041       0  134.37      .1       0
Bank Sta=72.5,134.37
XS Rating Curve= 0 ,0
Exp/Cntr=0.3,0.1

Type RM Length L Ch R = 1 ,12839.85,105.3,91.46,95.71
XS GIS Cut Line= 3
     626116.6118    4316506.7409     626108.4838    4316622.1371
     626105.7405    4316826.2634
#Sta/Elev= 30
       0  647.17    6.09  643.04    9.13  642.89   24.35  632.83   36.53  625.71
   39.58  625.61   51.75  621.44   66.97  611.28   70.02  610.91   76.11  606.61
   79.15  604.93   85.24  604.55  115.68  604.67  121.78  606.52  127.87   607.9
  146.15  609.79  222.32  607.79  225.37   608.5  228.42   610.6  237.56  619.37
   246.7  625.84  249.75   627.1  252.79  627.46  264.98  632.94  274.12   636.1
  280.22  636.92   292.4  640.52  307.64  644.18  310.69  644.24  319.83  647.05
#Mann= 3 , 0 , 0
       0      .1       0   76.11    .041       0  121.78      .1       0
Bank Sta=76.11,121.78
XS Rating Curve= 0 ,0
Exp/Cntr=0.3,0.1

Type RM Length L Ch R = 1 ,12748.4 ,109.69,91.44,77.82
XS GIS Cut Line= 4
     625979.8882    4316527.0284     626013.8794    4316604.6882
     626082.4068    4316740.0412     626099.3905    4316833.6717
#Sta/Elev= 30
       0  647.52    3.03  644.96    9.08  642.34   18.17  635.32   27.25  630.37
   36.33  626.46   39.36  625.97   48.44  622.43   57.52  620.53   60.55   619.2
   66.61  614.38   72.66  611.82   84.77  605.31   87.81  603.99   93.88   603.6
  127.25  604.23  133.32  604.84  136.35   605.8  142.42  607.75  148.49  608.01
  233.45     608  236.48  609.38   254.9  624.34  257.97  624.75  264.11  629.02
  273.32  633.35  282.53  636.62  288.67  637.46  319.36  644.33  331.64  648.07
#Mann= 3 , 0 , 0
       0      .1       0   84.77    .041       0  136.35      .1       0
Bank Sta=84.77,136.35
XS Rating Curve= 0 ,0
Exp/Cntr=0.3,0.1

Type RM Length L Ch R = 1 ,12656.96,98.34,91.44,70.54
XS GIS Cut Line= 6
     625850.2583    4316609.3399     625939.1993    4316673.7363
     625964.9796    4316688.1189     625973.8548    4316699.6563
     625986.9517    4316722.6751     626082.8275    4316846.6716
#Sta/Elev= 30
       0  648.05    9.15  645.44   39.65  631.88    54.9  626.91   70.15  620.54
   82.35  617.19   94.56  615.81   97.61  614.45  106.76  607.75  112.64  605.22
   118.3   603.9  145.16  603.37  150.98  603.53  168.61  606.25   189.6  604.52
  198.82  605.75  226.48  606.52  229.55  607.73   235.7  611.84  238.77  612.91
  244.92  618.82  247.99  621.05  257.21  626.91  260.29  628.12  266.43  629.98
  272.58  630.68  297.17  636.17  303.31  638.35  324.83  643.71  337.12  648.02
#Mann= 3 , 0 , 0
       0      .1       0  112.64    .041       0  198.82      .1       0
Bank Sta=112.64,198.82
XS Rating Curve= 0 ,0
Exp/Cntr=0.3,0.1