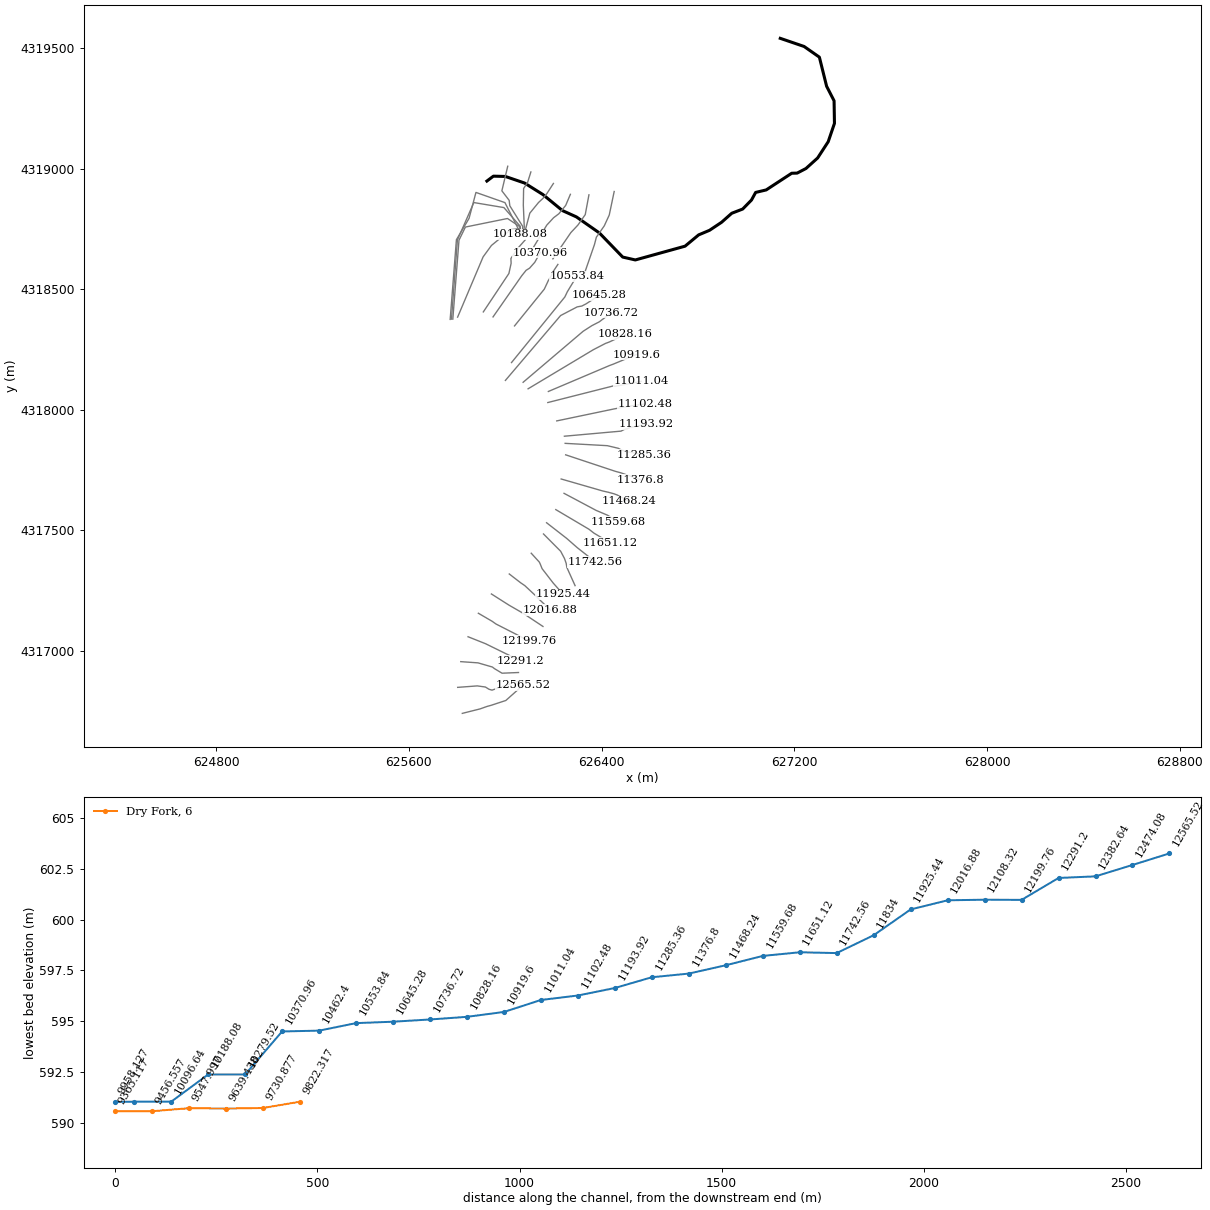
HEC-RAS study RedCreek.prj: RedCreek

--- RedCreek.g01 (geometry) --- (continued)

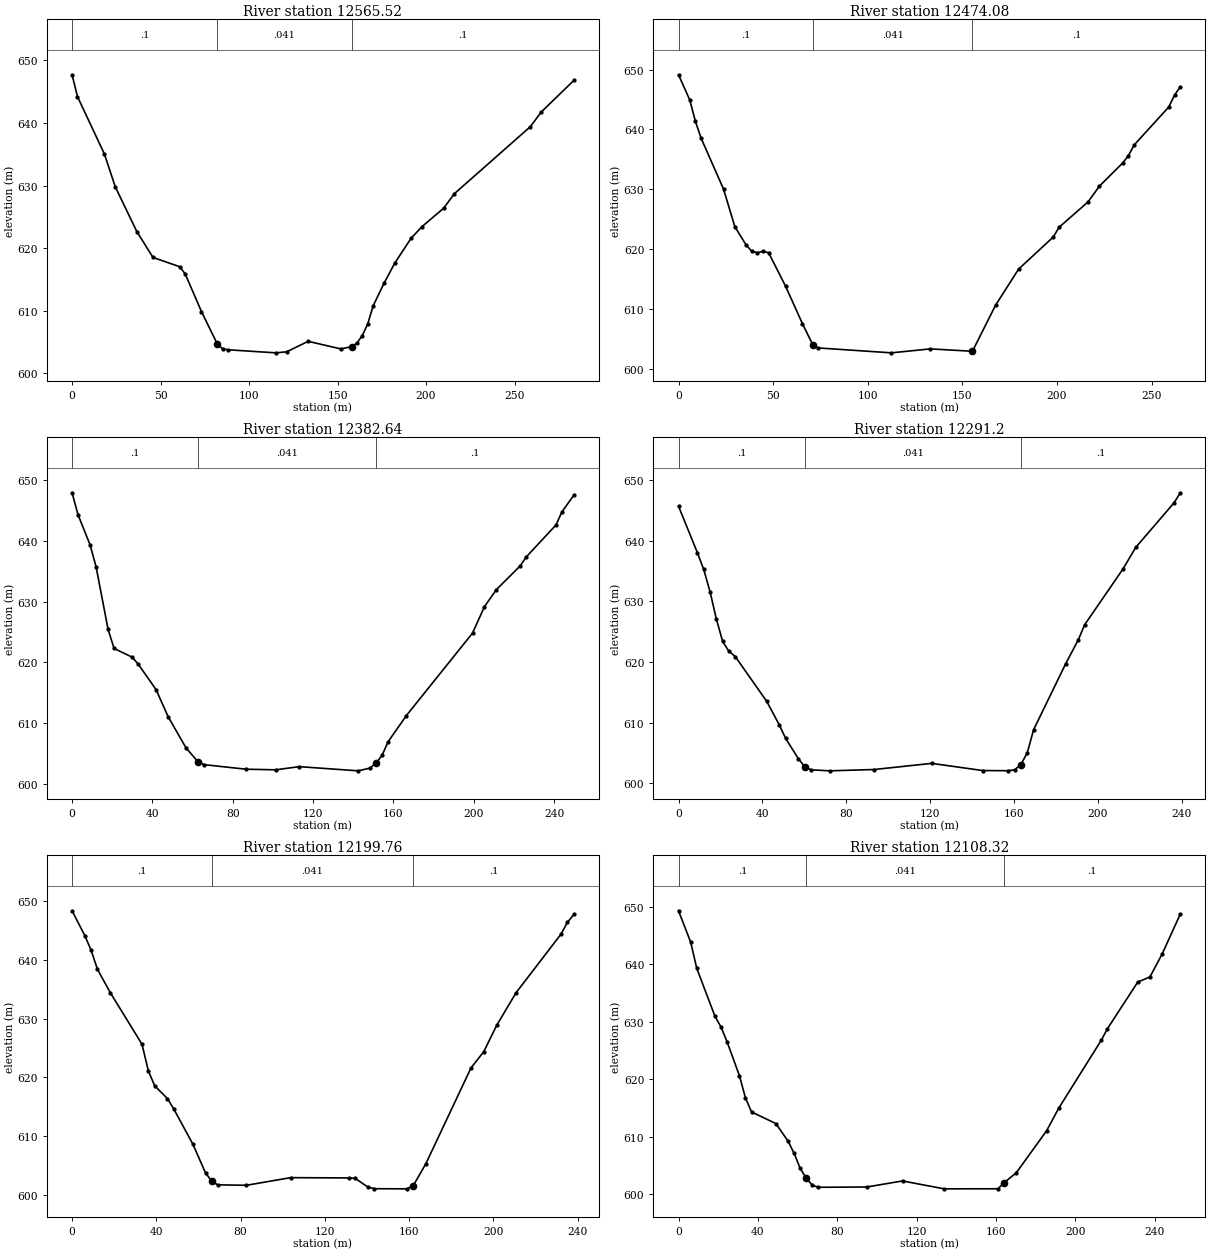
Type RM Length L Ch R = 1 ,12565.52,97.23,91.44,65.15
XS GIS Cut Line= 6
     625821.9421    4316739.2662     625895.8197    4316757.8603
     625923.8916    4316767.8415     625941.5089    4316772.7313
     626002.5313    4316792.7634     626073.5671    4316855.9321
#Sta/Elev= 30
       0   647.7    3.05  644.22   18.28  635.03   24.38  629.82   36.57  622.65
   45.71  618.51   60.95  617.01   63.99  615.83   73.13  609.85   82.14  604.63
   85.12   603.9    88.1  603.75  115.12  603.26  121.21  603.42  133.43   605.1
  151.78  603.89   157.9  604.24  160.96  604.82  164.02  606.03  167.08  607.89
  170.13  610.77  176.25  614.37  182.37  617.61  191.55  621.56  197.68  623.42
  209.95  626.37  216.08  628.71  259.01  639.42  265.15  641.76  283.54   646.8
#Mann= 3 , 0 , 0
       0      .1       0   82.14    .041       0   157.9      .1       0
Bank Sta=82.14,157.9
XS Rating Curve= 0 ,0
Exp/Cntr=0.3,0.1

Type RM Length L Ch R = 1 ,12474.08,99.01,91.44,88.86
XS GIS Cut Line= 6
     625802.7511    4316847.2327      625884.254    4316853.2729
     625917.7475    4316848.6288     625932.5819      4316839.35
     625945.1496     4316835.712      626057.692    4316874.4529
#Sta/Elev= 30
       0  649.13    5.95  644.91    8.93  641.34    11.9  638.56    23.8  630.02
   29.76  623.76   35.71  620.71   38.68  619.67   41.66   619.4   44.63  619.65
   47.61  619.41   56.54  613.84   65.46  607.58   71.11  603.93   73.78  603.51
  112.52  602.69  133.09  603.35  155.33  602.95  167.54  610.64  179.75  616.68
  198.06  622.04  201.11  623.66  216.37  627.88  222.47  630.54  234.68  634.38
  237.73   635.6  240.78   637.4  259.09  643.75  262.15  645.73   265.2  647.13
#Mann= 3 , 0 , 0
       0      .1       0   71.11    .041       0  155.33      .1       0
Bank Sta=71.11,155.33
XS Rating Curve= 0 ,0
Exp/Cntr=0.3,0.1

Type RM Length L Ch R = 1 ,12382.64,91.29,91.44,77.09
XS GIS Cut Line= 6
      625815.512    4316953.9341     625887.0162    4316948.8928
      625946.824    4316931.5571     625955.7337    4316924.6491
     625986.8657    4316905.9369     626055.0462    4316908.8488
#Sta/Elev= 30
       0  647.93    2.99  644.29    8.96  639.36   11.95  635.75   17.92  625.44
   20.91  622.29   29.87  620.86   32.85  619.74   41.81  615.51   47.79  611.07
   56.75   605.9   62.72  603.61   65.71  603.15   86.51   602.4  101.33   602.3
  113.19  602.82  142.41  602.13  148.25  602.58  151.28  603.41  154.31  604.67
  157.33  606.93  166.41  611.23  199.35  624.82  205.28  629.17  211.22  631.98
  223.09  635.89  226.05  637.35  240.89  642.63  243.86  644.79  249.79  647.54
#Mann= 3 , 0 , 0
       0      .1       0   62.72    .041       0  151.28      .1       0
Bank Sta=62.72,151.28
XS Rating Curve= 0 ,0
Exp/Cntr=0.3,0.1

Type RM Length L Ch R = 1 ,12291.2 ,98.12,91.44,91.15
XS GIS Cut Line= 3
     625845.6996    4317057.2671     625918.3063     4317028.339
      626063.063    4316957.3798
#Sta/Elev= 30
       0  645.65    9.02  637.97   12.02  635.23   15.03  631.57   18.04  627.07
   21.04  623.37   24.05  621.75   27.05  620.89   42.08  613.49    48.1   609.6
    51.1  607.39   57.11  604.08   60.12  602.76   63.13  602.22   72.15  602.05
   93.37  602.27  120.74  603.28  145.08   602.1  157.24  602.07  160.28  602.22
  163.33  603.07  166.37  605.05  169.41  608.85  184.62  619.66   190.7  623.64
  193.74  626.13  211.99   635.3  218.08  638.86  236.33   646.2  239.37  647.87
#Mann= 3 , 0 , 0
       0      .1       0   60.12    .041       0  163.33      .1       0
Bank Sta=60.12,163.33
XS Rating Curve= 0 ,0
Exp/Cntr=0.3,0.1

Type RM Length L Ch R = 1 ,12199.76,94.45,91.44,90
XS GIS Cut Line= 4
     625888.6009     4317154.702     625945.9645    4317121.2602
     625961.5384    4317110.1991     626097.4999    4317040.7406
#Sta/Elev= 30
       0  648.41    6.04  644.18    9.05  641.67   12.07   638.4   18.11  634.46
    33.2  625.64   36.22  621.08   39.24  618.54   45.27  616.37   48.29  614.59
   57.35  608.58   63.38  603.66    66.4  602.24   69.13  601.65   82.77  601.58
  103.82  602.88   131.3  602.83  134.36  602.76  140.47  601.26  143.52  600.99
  158.79  600.97  161.84  601.45  167.95  605.27  189.32  621.58  195.43  624.38
  201.54  628.85   210.7  634.41  232.07  644.42  235.12  646.44  238.18  647.78
#Mann= 3 , 0 , 0
       0      .1       0    66.4    .041       0  161.84      .1       0
Bank Sta=66.4,161.84
XS Rating Curve= 0 ,0
Exp/Cntr=0.3,0.1

Type RM Length L Ch R = 1 ,12108.32,106.22,91.44,86.29
XS GIS Cut Line= 4
     625942.7337    4317234.7298     626015.2015    4317188.6565
     626074.9955    4317154.1869     626156.6254    4317099.9498
#Sta/Elev= 30
       0   649.3    6.13  643.83     9.2  639.28    18.4  630.93   21.47  629.05
   24.54  626.47   30.67  620.66   33.74  616.77    36.8  614.34   49.07  612.32
    55.2  609.27   58.27  607.13   61.34  604.52   64.41  602.81   67.47  601.58
   70.54  601.25   94.88   601.3  112.88  602.35  133.89  600.98  161.02  600.99
  164.08  602.06  170.21  603.76  185.52  611.08  191.64  615.01  213.08  626.81
  216.15   628.8  231.46  636.92  237.58   637.8  243.71  641.77   252.9  648.74
#Mann= 3 , 0 , 0
       0      .1       0   64.41    .041       0  164.08      .1       0
Bank Sta=64.41,164.08
XS Rating Curve= 0 ,0
Exp/Cntr=0.3,0.1

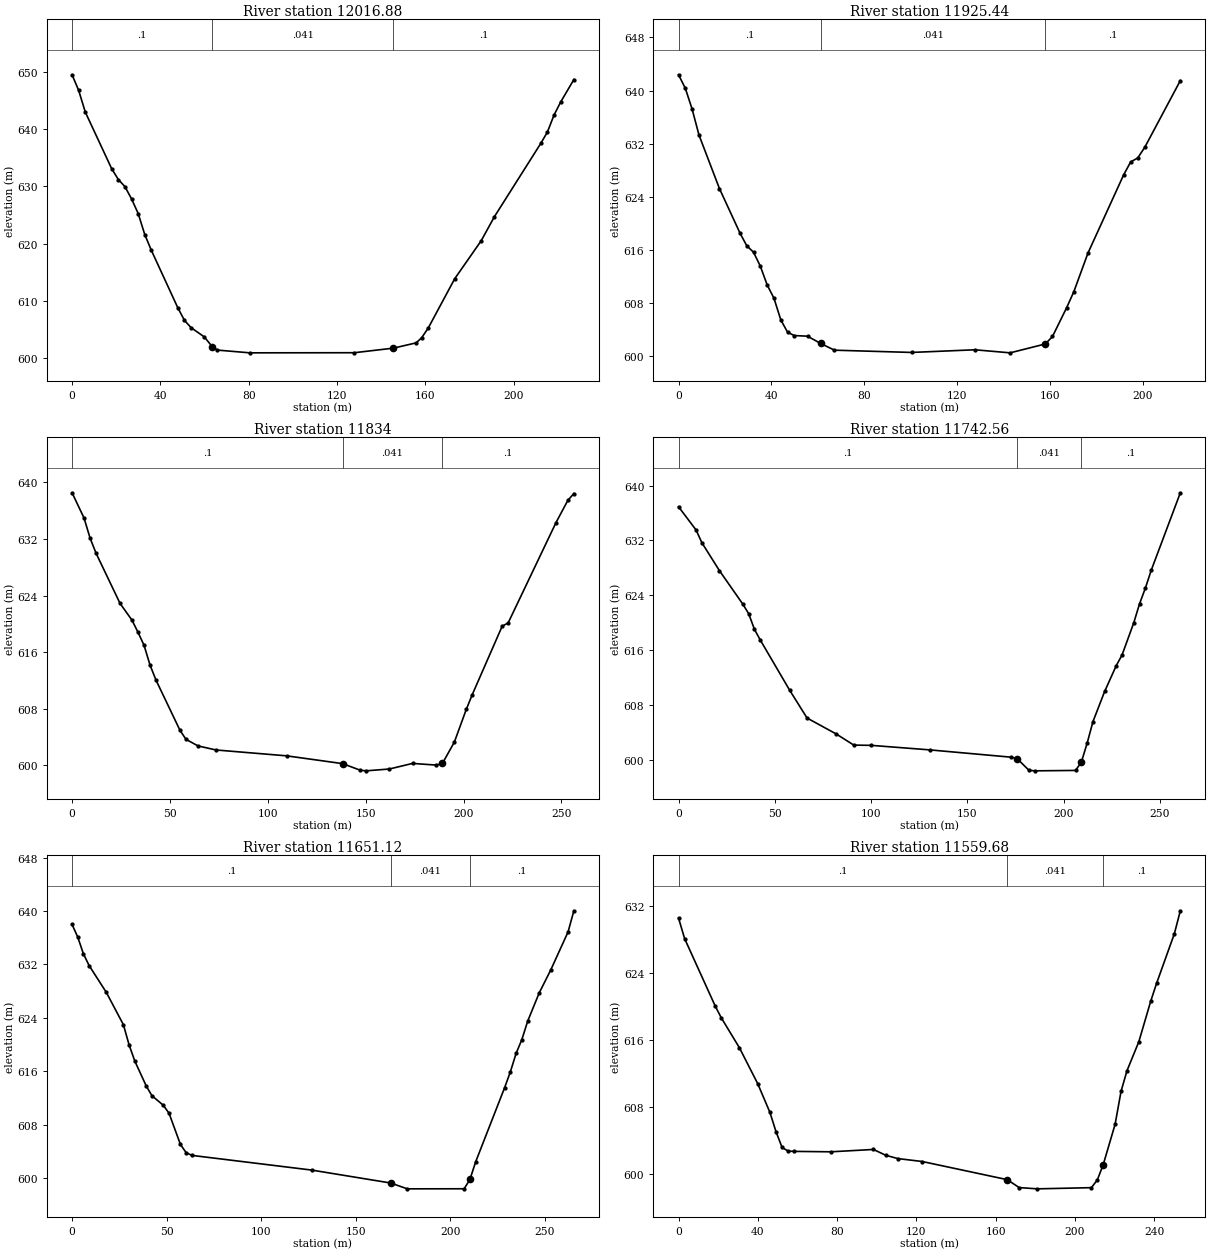
Type RM Length L Ch R = 1 ,12016.88,116.1,91.44,90.24
XS GIS Cut Line= 6
     626016.8107    4317317.6627     626064.1857    4317281.0518
     626081.2604    4317269.4457     626130.9317    4317223.0494
     626137.5446    4317215.7972     626187.3621    4317168.1645
#Sta/Elev= 30
       0  649.47    2.99  646.74    5.99  642.96   17.96  633.06   20.96  631.19
   23.95  629.95   26.94  627.81   29.94  625.26   32.93  621.58   35.92  618.82
    47.9   608.8   50.89  606.62   53.89  605.35   59.87  603.73   63.48  602.03
   65.77  601.43   80.52  600.95   127.8  600.97  145.53  601.77  155.81  602.69
   158.3  603.58   161.3  605.29  173.29  613.89  185.27  620.51  191.27  624.72
  212.24  637.49  215.24  639.47  218.24  642.43  221.23   644.7  227.23  648.64
#Mann= 3 , 0 , 0
       0      .1       0   63.48    .041       0  145.53      .1       0
Bank Sta=63.48,145.53
XS Rating Curve= 0 ,0
Exp/Cntr=0.3,0.1

Type RM Length L Ch R = 1 ,11925.44,100.19,91.44,80.63
XS GIS Cut Line= 6
     626107.9823    4317403.7206     626141.6499    4317366.8729
     626146.2801    4317356.6203     626152.9034    4317339.9101
     626199.2501    4317279.9321     626239.8027     4317234.138
#Sta/Elev= 30
       0  642.38    2.94  640.33    5.87  637.18    8.81   633.3   17.62  625.24
   26.42  618.57   29.36  616.64    32.3  615.65   35.23  613.55   38.17  610.73
    41.1  608.72   44.04  605.46   46.98  603.59   49.91   603.1   55.54  603.01
   61.16  601.92   67.15   600.9  100.36  600.56  127.65  600.96  142.81   600.5
  157.99  601.84  161.05  602.97  167.17  607.32  170.23   609.7  176.34  615.54
  191.64  627.27   194.7  629.25  197.75  629.85  200.81  631.47   216.1   641.5
#Mann= 3 , 0 , 0
       0      .1       0   61.16    .041       0  157.99      .1       0
Bank Sta=61.16,157.99
XS Rating Curve= 0 ,0
Exp/Cntr=0.3,0.1

Type RM Length L Ch R = 1 ,11834   ,63.43,91.44,101.25
XS GIS Cut Line= 6
     626158.8678    4317483.6573       626230.14    4317411.9227
      626246.015    4317381.7601     626252.8968    4317361.9397
      626255.927    4317344.4521     626289.8368    4317269.3444
#Sta/Elev= 30
       0  638.54    6.13  634.96    9.19  632.14   12.26  629.99   24.51   622.9
   30.64  620.52   33.71   618.8   36.77  616.98   39.84  614.17    42.9  612.04
   55.16  604.94   58.22  603.68   64.35  602.75   73.54  602.18  109.64  601.35
   138.2  600.25   147.2  599.32  150.19  599.23   162.1  599.49  173.94  600.28
  186.14  600.04   189.2  600.28   195.3   603.3  201.41  607.94  204.46  610.02
  219.72  619.68  222.77  620.14  247.19  634.31  253.29  637.48  256.34  638.43
#Mann= 3 , 0 , 0
       0      .1       0   138.2    .041       0   189.2      .1       0
Bank Sta=138.2,189.2
XS Rating Curve= 0 ,0
Exp/Cntr=0.3,0.1

Type RM Length L Ch R = 1 ,11742.56,87.31,91.44,93.66
XS GIS Cut Line= 4
     626171.6025    4317530.2841     626255.4077     4317465.071
     626298.7554    4317427.0591     626374.8452    4317367.2742
#Sta/Elev= 30
       0  636.91     9.1  633.52   12.14  631.65   21.24  627.58   33.37   622.7
   36.41  621.31   39.44     619   42.48  617.44   57.65  610.15   66.75  606.06
   81.92  603.73   91.02  602.11  100.12  602.07  130.46  601.41  172.91  600.34
  175.94  600.11  181.99  598.43  185.01  598.35  206.18  598.41   209.2  599.61
  212.23  602.41  215.25  605.55   221.3  609.94  227.35  613.72  230.37  615.28
  236.42  619.96  239.44  622.75  242.47  625.04  245.49  627.63  260.61  638.95
#Mann= 3 , 0 , 0
       0      .1       0  175.94    .041       0   209.2      .1       0
Bank Sta=175.94,209.2
XS Rating Curve= 0 ,0
Exp/Cntr=0.3,0.1

Type RM Length L Ch R = 1 ,11651.12,82.78,91.44,92.67
XS GIS Cut Line= 4
     626209.9099    4317584.7786     626347.5312    4317503.3506
     626368.1028    4317487.2785     626436.2572    4317446.5363
#Sta/Elev= 30
       0  637.98    3.02  636.08    6.03  633.56    9.05  631.81    18.1  627.82
   27.15  622.97   30.17  619.94   33.19  617.52   39.22   613.8   42.24  612.34
   48.27   610.9   51.29  609.71   57.33  605.03   60.34  603.81   63.36   603.4
  126.72   601.2  168.61  599.26  177.31  598.39  207.39   598.4  210.44  599.79
   213.5  602.45  228.77  613.52  231.82   615.9  234.88  618.68  237.93  620.75
  240.98  623.49  247.09  627.73   253.2  631.17  262.36  636.87  265.42  640.03
#Mann= 3 , 0 , 0
       0      .1       0  168.61    .041       0  210.44      .1       0
Bank Sta=168.61,210.44
XS Rating Curve= 0 ,0
Exp/Cntr=0.3,0.1

Type RM Length L Ch R = 1 ,11559.68,82.82,91.44,94.31
XS GIS Cut Line= 4
     626244.0859    4317652.3295     626377.0993    4317581.6366
     626424.7494    4317561.4271     626468.1523     4317534.917
#Sta/Elev= 30
       0   630.6    3.07  628.14   18.44  620.11   21.52  618.69   30.74  615.08
   39.96  610.79   46.11  607.36   49.19  605.05   52.26  603.16   55.33  602.72
   58.41  602.69   76.85  602.64   98.37  602.92  104.52  602.23  110.67  601.83
  122.97  601.48  165.86  599.31  171.94  598.36  181.08  598.21  208.37  598.35
  211.37  599.28  214.36  601.12  220.34  605.94  223.33  609.87  226.32  612.33
  232.31  615.81  238.29  620.64  241.28   622.8  250.26  628.74  253.25  631.47
#Mann= 3 , 0 , 0
       0      .1       0  165.86    .041       0  214.36      .1       0
Bank Sta=165.86,214.36
XS Rating Curve= 0 ,0
Exp/Cntr=0.3,0.1

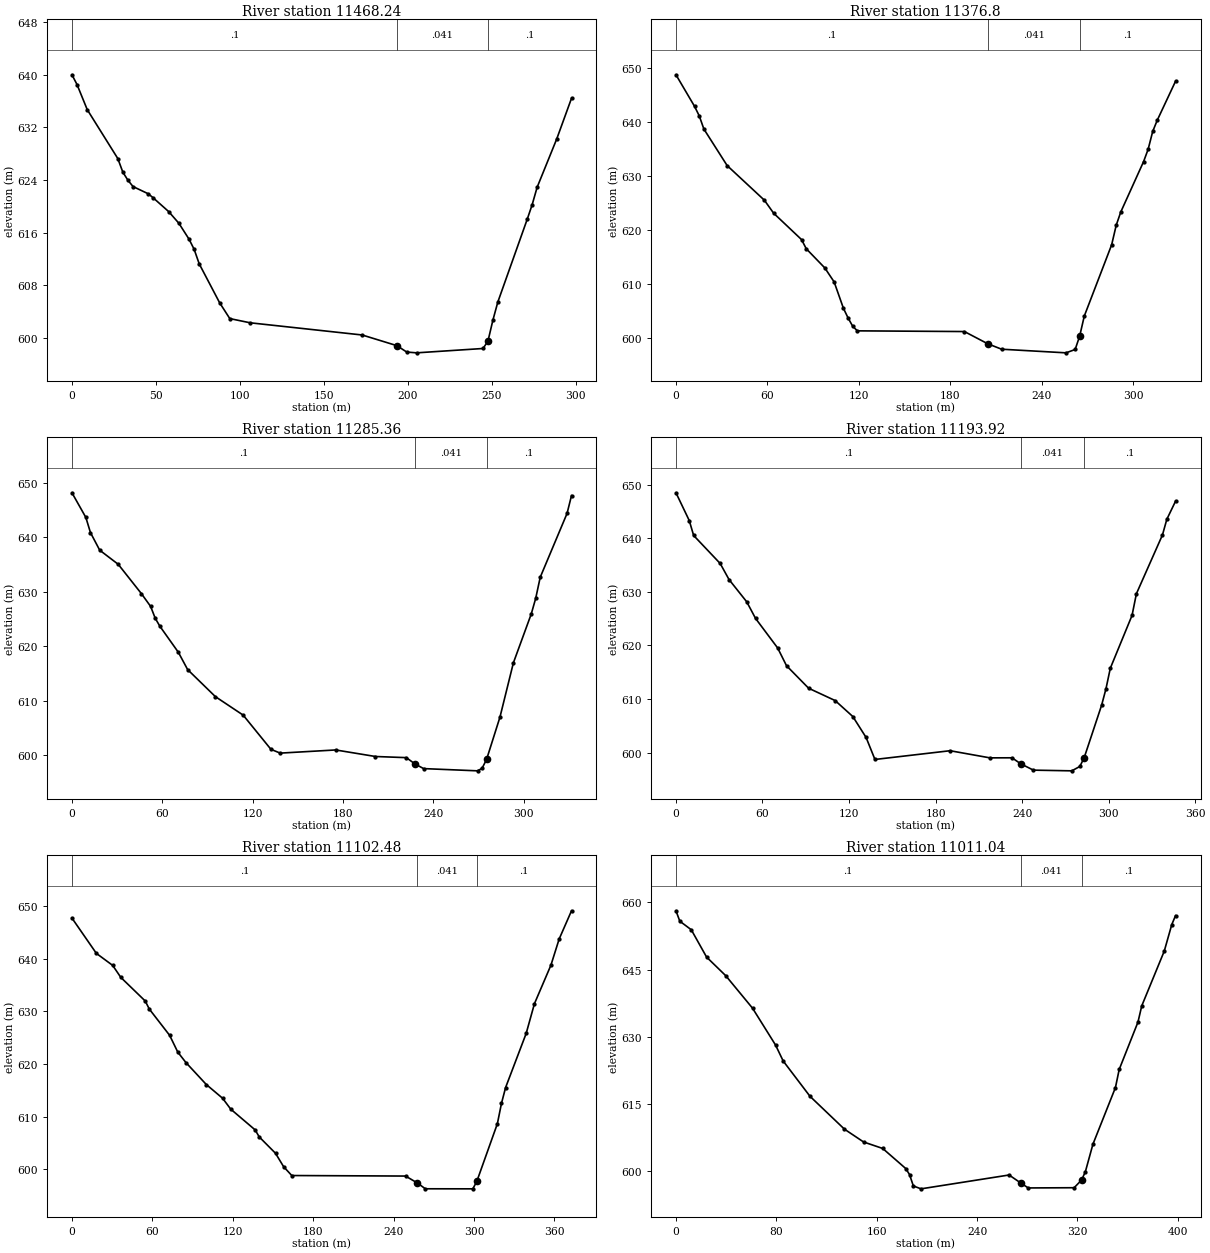
Type RM Length L Ch R = 1 ,11468.24,94.59,91.44,92.75
XS GIS Cut Line= 6
     626232.1796    4317711.8609     626404.1283    4317662.2519
     626429.7939    4317656.3145     626451.7312    4317650.3233
     626464.7829    4317645.4314     626513.8633    4317619.2395
#Sta/Elev= 30
       0  639.96    3.03  638.47     9.1  634.67    27.3  627.25   30.33  625.17
   33.37  623.94    36.4  622.99    45.5  621.89   48.53  621.25   57.63  619.19
    63.7  617.42   69.76     615    72.8  613.46   75.83  611.25   87.96  605.36
   94.03  602.95  106.16  602.31   172.9  600.46   193.6  598.84  199.45  597.87
  205.31  597.75  244.91  598.41  247.84  599.53  250.77   602.7   253.7  605.45
  271.26  618.05  274.19  620.25  277.12  622.87  288.83  630.23  297.62  636.39
#Mann= 3 , 0 , 0
       0      .1       0   193.6    .041       0  247.84      .1       0
Bank Sta=193.6,247.84
XS Rating Curve= 0 ,0
Exp/Cntr=0.3,0.1

Type RM Length L Ch R = 1 ,11376.8 ,92.7,91.44,94.95
XS GIS Cut Line= 4
     626250.8107    4317812.1161     626456.4088    4317743.8346
     626479.7789     4317737.452      626561.858    4317709.2514
#Sta/Elev= 30
       0  648.67   12.21  642.83   15.26  641.09   18.31  638.65   33.56  631.91
   57.97  625.52   64.08  623.11   82.38  618.24   85.44  616.56   97.64  613.01
  103.74  610.43  109.85  605.55   112.9  603.77  115.95  602.23     119   601.4
  189.18  601.27  204.44  599.02  213.59  598.01  255.83  597.34  261.82  597.96
  264.81  600.46   267.8  604.12  285.76  617.29  288.75   620.9  291.74  623.34
  306.71  632.65   309.7  634.93  312.69  638.22  315.68  640.29  327.65  647.47
#Mann= 3 , 0 , 0
       0      .1       0  204.44    .041       0  264.81      .1       0
Bank Sta=204.44,264.81
XS Rating Curve= 0 ,0
Exp/Cntr=0.3,0.1

Type RM Length L Ch R = 1 ,11285.36,63.2,91.44,107.89
XS GIS Cut Line= 6
      626248.694    4317859.7412     626423.5299    4317850.1258
     626469.1606    4317839.2896     626481.6012    4317832.1037
      626501.724    4317825.8587     626574.6836    4317812.2352
#Sta/Elev= 30
       0  648.16    9.22  643.64   12.29  640.85   18.43  637.63   30.72  635.04
   46.08  629.67   52.22  627.32   55.29  625.14   58.37  623.68   70.65   618.9
    76.8  615.73   95.23  610.77  113.66  607.38  132.09  601.11  138.24  600.41
   175.1  600.99  201.48  599.79     222  599.58  227.75  598.42  233.49  597.57
  269.31  597.16  272.28  597.63  275.25  599.24  284.16  607.02  293.06  616.96
  304.94  625.94  307.91  628.83  310.88  632.66  328.69  644.37  331.66  647.65
#Mann= 3 , 0 , 0
       0      .1       0  227.75    .041       0  275.25      .1       0
Bank Sta=227.75,275.25
XS Rating Curve= 0 ,0
Exp/Cntr=0.3,0.1

Type RM Length L Ch R = 1 ,11193.92,92.67,91.44,87.74
XS GIS Cut Line= 6
      626245.519    4317889.3746       626480.67    4317910.4626
     626493.6507    4317917.4341     626506.7175    4317919.8871
     626518.2409    4317925.8085     626586.4595    4317938.2591
#Sta/Elev= 30
       0  648.46     9.2  643.29   12.26   640.5   30.66  635.28   36.79  632.29
   49.06  628.14   55.19  625.04   70.52  619.53   76.65  616.23   91.98  612.03
  110.38  609.73  122.65  606.75  131.85  602.85  137.98  598.75   190.1  600.38
   217.7  599.05  233.03  599.06  239.04  597.95  247.88  596.76  274.49  596.63
  280.09  597.45  283.11   599.1  295.17  608.86  298.18  611.91   301.2  615.75
  316.28  625.61  319.29  629.64  337.38  640.61   340.4  643.52  346.43  646.88
#Mann= 3 , 0 , 0
       0      .1       0  239.04    .041       0  283.11      .1       0
Bank Sta=239.04,283.11
XS Rating Curve= 0 ,0
Exp/Cntr=0.3,0.1

Type RM Length L Ch R = 1 ,11102.48,92.68,91.44,91.73
XS GIS Cut Line= 4
      626213.769    4317952.8747     626451.6652    4318002.5896
     626509.7153    4318013.4872     626579.7477    4318023.1542
#Sta/Elev= 30
       0  647.72   18.23  641.01   30.38  638.73   36.46  636.45   54.68  631.96
   57.72  630.43   72.91  625.43   78.99  622.24   85.06  620.26  100.25  616.09
   112.4  613.48  118.48  611.41  136.71  607.46  139.75  606.13   151.9  603.02
  157.97  600.46  164.05  598.79  248.94  598.69   257.8  597.37  263.71  596.27
  299.15  596.26   302.1  597.66  317.47  608.64  320.54  612.52  323.62  615.52
  338.98  625.81  345.13  631.45  357.43  638.77  363.57  643.74   372.8  649.11
#Mann= 3 , 0 , 0
       0      .1       0   257.8    .041       0   302.1      .1       0
Bank Sta=257.8,302.1
XS Rating Curve= 0 ,0
Exp/Cntr=0.3,0.1

Type RM Length L Ch R = 1 ,11011.04,79.26,91.44,97.93
XS GIS Cut Line= 4
     626176.7272    4318029.0749     626448.8703    4318098.1419
     626455.2483    4318096.2995     626564.1119     4318116.736
#Sta/Elev= 30
       0  658.11    3.05  655.79   12.21  653.87   24.41  647.77   39.67  643.62
   61.04  636.36   79.35  628.15   85.45  624.58  106.81   616.7  134.28  609.36
  149.54   606.5   164.8  605.05  183.11  600.58  186.16  599.23  189.21  596.68
  195.32  596.04  265.51  599.13  274.67  597.37  280.77  596.24  317.35  596.29
  323.33  598.02  326.33  599.88  332.31  605.98  350.28  618.65  353.27  622.69
  368.24  633.27  371.23  636.87  389.19  649.11  395.18  655.03  398.17  657.03
#Mann= 3 , 0 , 0
       0      .1       0  274.67    .041       0  323.33      .1       0
Bank Sta=274.67,323.33
XS Rating Curve= 0 ,0
Exp/Cntr=0.3,0.1

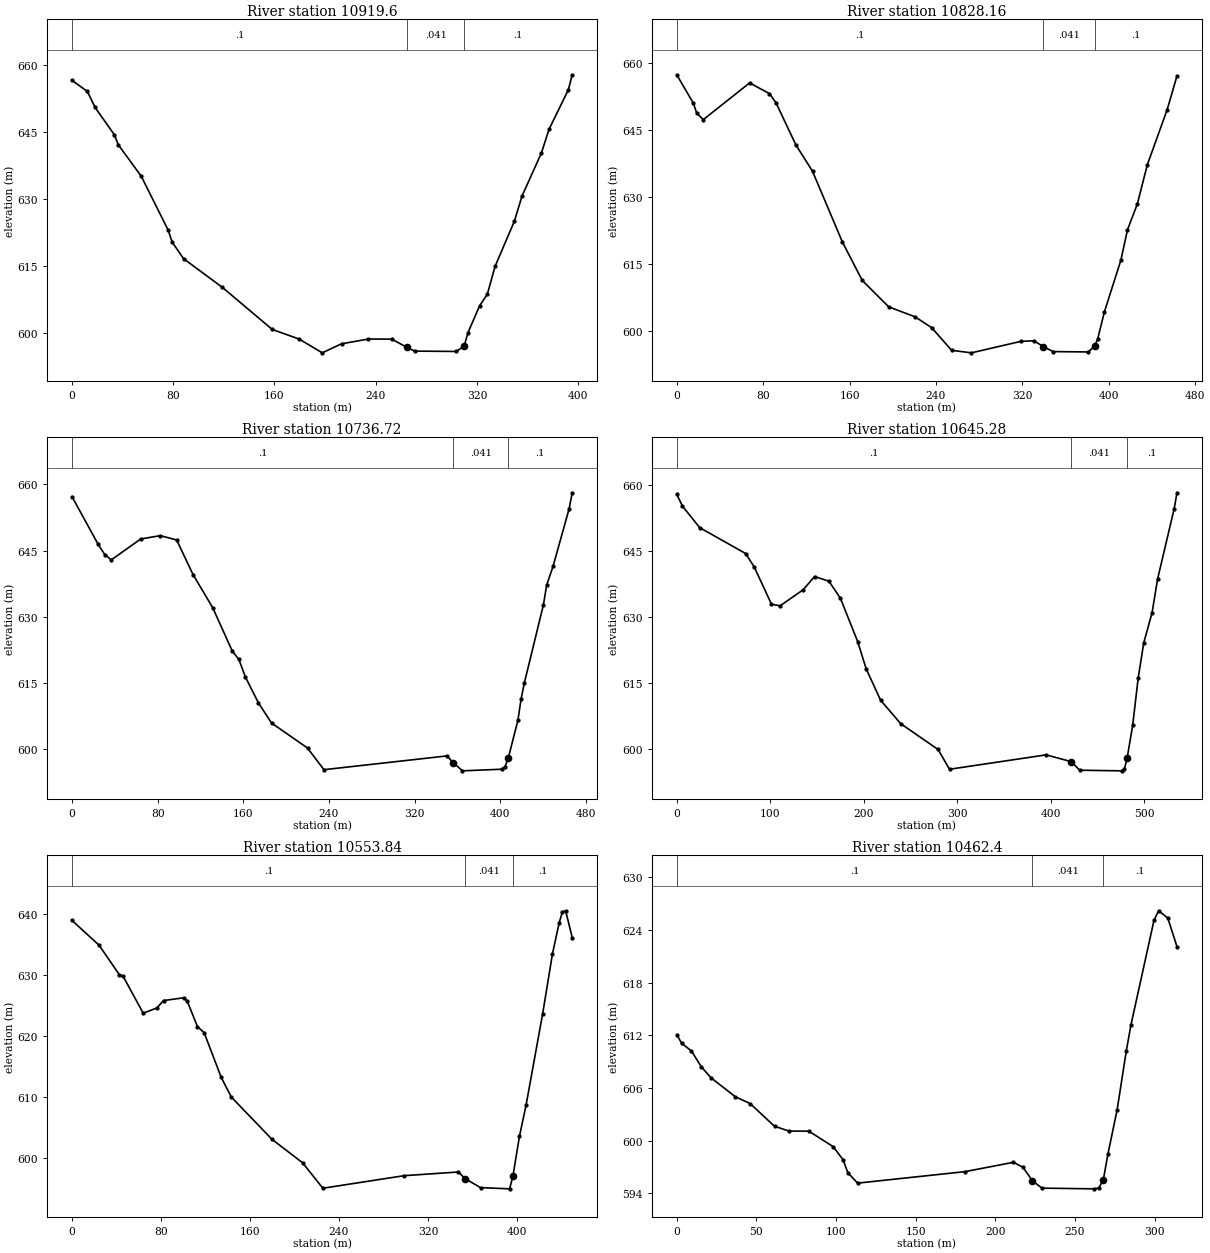
Type RM Length L Ch R = 1 ,10919.6 ,85.21,91.44,91.57
XS GIS Cut Line= 4
     626179.0203    4318075.0066     626433.8757    4318183.1138
     626447.7223    4318188.1637      626543.463    4318227.9341
#Sta/Elev= 30
       0  656.63   12.17  654.13   18.25  650.54   33.46  644.42   36.51   642.2
   54.76  635.08   76.05  622.97    79.1  620.33   88.22  616.57  118.64  610.19
  158.19  600.71  179.49  598.54  197.74  595.45  212.95  597.48  234.25  598.55
   252.5  598.53  264.67  596.69  270.75  595.84  303.77  595.76  309.87  596.99
  312.92     600  322.07  606.02  328.17   608.6  334.26  614.84  349.51  624.98
  355.61  630.68  370.85  640.28  376.95  645.65   392.2  654.52  395.25  657.88
#Mann= 3 , 0 , 0
       0      .1       0  264.67    .041       0  309.87      .1       0
Bank Sta=264.67,309.87
XS Rating Curve= 0 ,0
Exp/Cntr=0.3,0.1

Type RM Length L Ch R = 1 ,10828.16,84.48,91.44,95.18
XS GIS Cut Line= 5
     626094.8826    4318086.1191     626365.8039    4318248.4064
     626415.8921    4318274.3141     626432.4257    4318280.5267
     626498.6945    4318311.8938
#Sta/Elev= 30
       0  657.27   15.33  650.95    18.4  648.77   24.53  647.25   67.45  655.45
   85.85  653.08   91.98  650.97  110.38  641.59  125.71  635.74  153.31  619.98
   171.7  611.39  196.23  605.48  220.76  603.24  236.09  600.81  254.49  595.77
  272.88  595.21  318.78  597.78  330.65   597.9  339.55   596.6  348.46  595.49
  381.03  595.41  386.92  596.69  389.86  598.41  395.97  604.34  411.25  615.91
  417.36  622.68  426.52  628.47  435.69  637.16  454.02  649.43  463.18  657.01
#Mann= 3 , 0 , 0
       0      .1       0  339.55    .041       0  386.92      .1       0
Bank Sta=339.55,386.92
XS Rating Curve= 0 ,0
Exp/Cntr=0.3,0.1

Type RM Length L Ch R = 1 ,10736.72,106.99,91.44,92.72
XS GIS Cut Line= 5
     626074.2451    4318113.1067      626323.374    4318324.8126
     626359.9415    4318348.3632     626390.2103    4318363.8856
     626440.1781     4318401.761
#Sta/Elev= 30
       0  657.21   24.44   646.4   30.55  644.09   36.67  642.87   64.16  647.61
    82.5  648.37   97.77  647.38  113.05  639.54  131.38  632.06  149.72   622.2
  155.83  620.33  161.94  616.34  174.16  610.45  186.38  605.91  219.99  600.24
  235.27  595.34  350.13  598.46  355.93  596.95  364.63  595.08  401.61  595.45
  404.44  596.06  407.43  597.99  416.39   606.5  419.37  611.32  422.36  614.92
  440.27  632.73  443.26  637.15  449.23  641.41  464.16  654.39  467.14  658.08
#Mann= 3 , 0 , 0
       0      .1       0  355.93    .041       0  407.43      .1       0
Bank Sta=355.93,407.43
XS Rating Curve= 0 ,0
Exp/Cntr=0.3,0.1

Type RM Length L Ch R = 1 ,10645.28,44.91,91.44,101.54
XS GIS Cut Line= 6
     626000.7569    4318120.9119     626229.7303    4318390.0064
     626298.7296     4318426.076     626317.6767    4318429.4516
     626335.1558    4318438.4152      626389.992    4318473.6987
#Sta/Elev= 30
       0  657.83    6.14  655.15   24.58  650.25   73.74  644.37   82.96  641.29
  101.39  632.85  110.61  632.48  135.19  636.12  147.48  639.14  162.84  638.08
  175.13   634.2  193.56  624.37  202.78  618.12  218.14  611.02  239.65  605.69
  279.59  599.83  291.88  595.33  395.25   598.6   422.2  597.06  431.19  595.11
     476  594.97  478.97  595.36  481.93  597.83  487.86   605.3  493.79   616.1
  499.71  624.06  508.61  630.89  514.53  638.57  532.32   654.6  535.28  658.18
#Mann= 3 , 0 , 0
       0      .1       0   422.2    .041       0  481.93      .1       0
Bank Sta=422.2,481.93
XS Rating Curve= 0 ,0
Exp/Cntr=0.3,0.1

Type RM Length L Ch R = 1 ,10553.84,86.64,91.44,94.75
XS GIS Cut Line= 4
     626026.1569    4318194.9954     626247.3077    4318466.9894
     626258.2021    4318489.6204     626296.7351    4318552.9085
#Sta/Elev= 30
       0  638.89   24.39  634.82   42.68  629.97   45.72  629.82   64.01  623.69
   76.21  624.53    82.3  625.76  100.59  626.21  103.64  625.65  112.79   621.5
  118.88  620.47  134.13  613.18  143.27  609.94  179.85  603.01  207.28  599.18
  225.57     595  298.73  597.06  347.51  597.66  353.35  596.59   367.3   595.1
  393.45   594.9  396.42  596.95  402.35  603.53  408.27  608.62  423.09  623.49
  431.98  633.39  437.91   638.4  440.88  640.26  443.84  640.47  449.77  636.09
#Mann= 3 , 0 , 0
       0      .1       0  353.35    .041       0  396.42      .1       0
Bank Sta=353.35,396.42
XS Rating Curve= 0 ,0
Exp/Cntr=0.3,0.1

Type RM Length L Ch R = 1 ,10462.4 ,111.65,91.44,85.45
XS GIS Cut Line= 6
     626038.5907    4318347.0071     626162.1999    4318499.6655
     626178.6425    4318534.7801     626192.5932    4318557.6932
     626194.6114    4318566.1422     626218.5539    4318602.2771
#Sta/Elev= 30
       0  612.07    3.07   611.1    9.21  610.22   15.35  608.44   21.48  607.17
   36.83     605   46.04  604.24   61.38  601.65   70.59   601.1   82.87   601.1
   98.21  599.33  104.35  597.86  107.42  596.36  113.56  595.18  181.08  596.49
  211.34  597.55  217.31  596.99  223.27  595.46  229.24  594.61  262.03  594.53
  264.92  594.62  267.82  595.56  270.71  598.49  276.49  603.53  282.27  610.26
  285.16  613.18  299.61  625.07   302.5  626.17  308.28  625.35  314.06  622.09
#Mann= 3 , 0 , 0
       0      .1       0  223.27    .041       0  267.82      .1       0
Bank Sta=223.27,267.82
XS Rating Curve= 0 ,0
Exp/Cntr=0.3,0.1

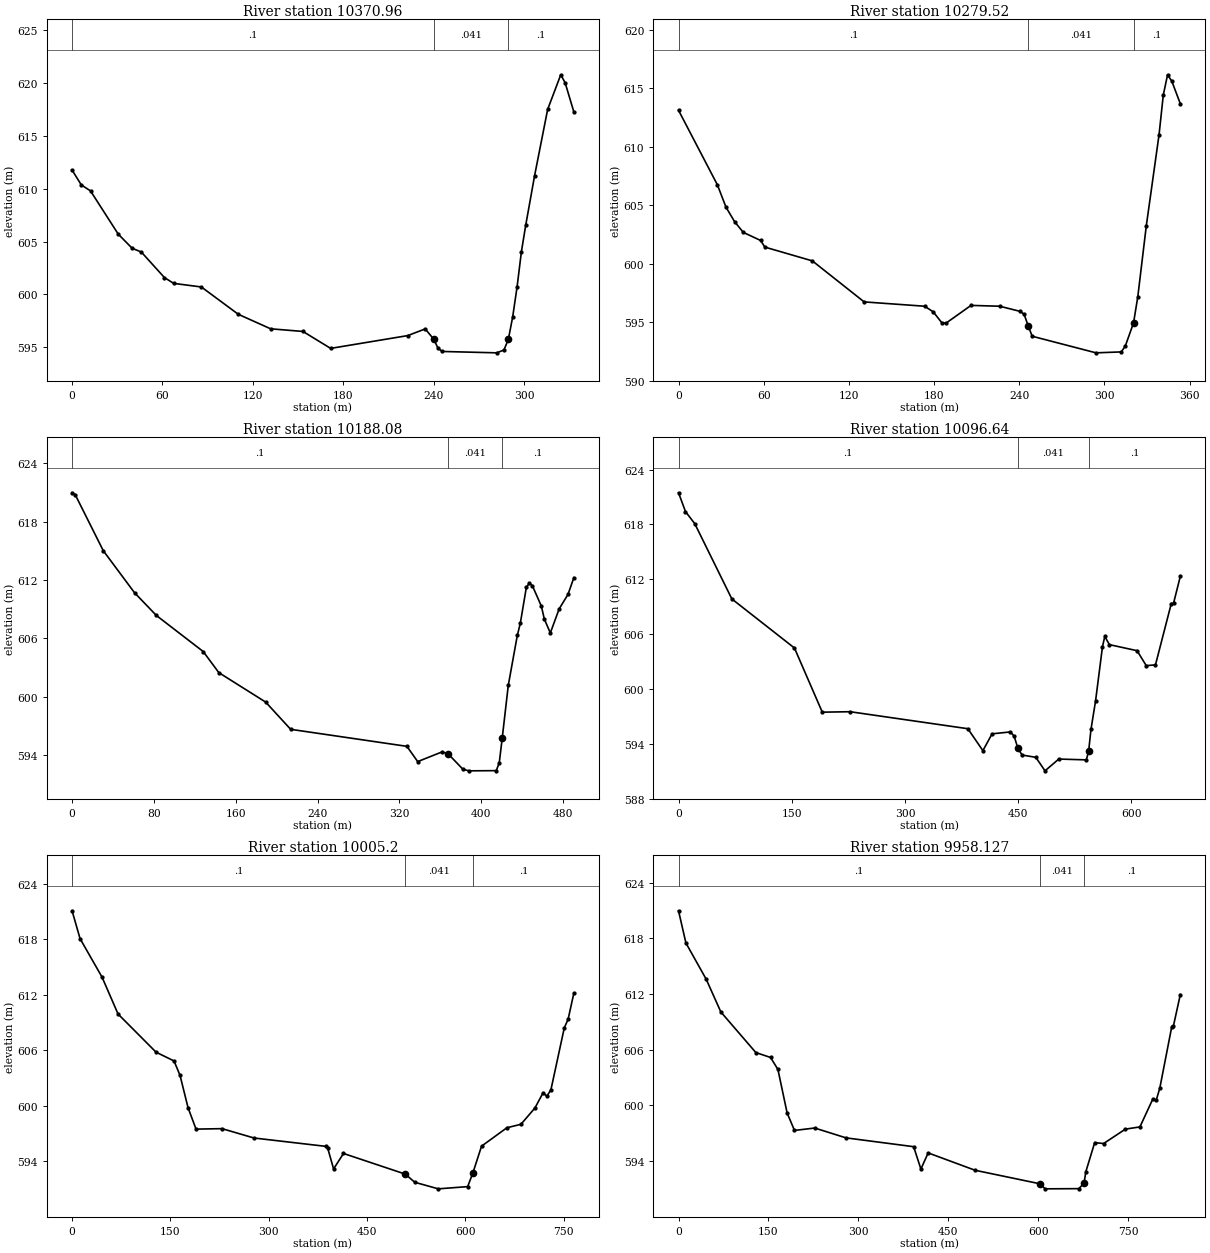
Type RM Length L Ch R = 1 ,10370.96,56.66,91.44,90.36
XS GIS Cut Line= 6
     625949.4627    4318384.3645     626068.6882    4318555.3693
     626086.7514    4318577.8968     626101.1847     4318586.782
     626122.6242    4318611.0582     626145.4708    4318651.4662
#Sta/Elev= 30
       0  611.75    6.13  610.35   12.26  609.78   30.66   605.7   39.85  604.37
   45.98  604.01   61.31   601.6   67.44  601.05   85.84  600.71  110.36  598.13
  131.82  596.76  153.28  596.51  171.68  594.91   222.9  596.12  234.45  596.75
  240.16  595.77  242.99  594.91  245.81  594.62   281.9  594.49  286.72  594.76
  289.63  595.75  292.53  597.89  295.43   600.7  298.33  604.06  301.23  606.58
  307.03  611.19  315.74  617.48  324.44  620.75  327.34     620  333.14  617.24
#Mann= 3 , 0 , 0
       0      .1       0  240.16    .041       0  289.63      .1       0
Bank Sta=240.16,289.63
XS Rating Curve= 0 ,0
Exp/Cntr=0.3,0.1

Type RM Length L Ch R = 1 ,10279.52,125.59,91.44,78.74
XS GIS Cut Line= 6
     625909.1297    4318405.1518     626015.2708    4318564.6302
     626024.5312    4318606.9636     626023.5282    4318626.8236
     626052.2805     4318669.377     626083.6414    4318704.7272
#Sta/Elev= 30
       0  613.13   27.37  606.75   33.45  604.83   39.53  603.59   45.61  602.68
   57.78  601.99   60.82  601.42   94.26  600.24  130.75  596.73  173.33  596.36
  179.41  595.88  185.49  594.94  188.53  594.92  206.02  596.43  226.24  596.36
  240.59  595.92  243.43  595.67  246.27  594.69  249.11  593.79  294.06  592.37
  311.89  592.45  314.76  592.97   320.5  594.93  323.49  597.16  329.49  603.24
  338.48  611.05  341.47  614.44  344.47  616.17  347.47  615.62  353.46  613.69
#Mann= 3 , 0 , 0
       0      .1       0  246.27    .041       0   320.5      .1       0
Bank Sta=246.27,320.5
XS Rating Curve= 0 ,0
Exp/Cntr=0.3,0.1

Type RM Length L Ch R = 1 ,10188.08,159.68,91.44,52.34
XS GIS Cut Line= 6
     625802.4666    4318383.4363     625908.3293    4318633.6193
     625942.8222    4318680.9489     626023.0629    4318746.5866
     626055.1289    4318750.2884     626059.5331    4318727.7295
#Sta/Elev= 30
       0  620.97    3.05  620.78   30.52  615.01   61.05  610.69   82.41  608.35
   128.2  604.64  143.46  602.47  189.25  599.44  213.66  596.64   327.3  594.89
  337.83  593.32  361.47  594.31  367.38  594.14  382.16  592.52  388.07  592.37
  414.63  592.39  417.57   593.2  420.51  595.79  426.39  601.17  435.21   606.3
  438.15  607.55  444.02  611.23  446.95  611.68  449.89  611.42  458.69  609.32
  461.62  607.98  467.49  606.55  476.11  609.03  484.73  610.51  490.48  612.24
#Mann= 3 , 0 , 0
       0      .1       0  367.38    .041       0  420.51      .1       0
Bank Sta=367.38,420.51
XS Rating Curve= 0 ,0
Exp/Cntr=0.3,0.1

Type RM Length L Ch R = 1 ,10096.64,109.43,91.44,47.43
XS GIS Cut Line= 6
     625782.5469    4318375.1384     625808.1777    4318702.7953
     625834.8213     4318757.326     626009.4466    4318792.7803
      626060.289    4318759.0257     626061.9144     4318726.142
#Sta/Elev= 30
       0  621.46    9.21   619.4    21.5  618.08   70.65  609.84  153.58  604.47
  190.44  597.45   227.3   597.5  383.28  595.64  403.21  593.24  415.39  595.08
  439.74  595.29  444.66  594.81  449.58   593.5  455.08  592.76  473.33  592.51
  485.49  591.03  503.74  592.32   540.3  592.23  543.35  593.22   546.4  595.56
  552.51   598.7  561.66  604.63  564.71  605.74  570.82  604.84  607.43  604.18
  619.64  602.54  631.85  602.63   652.8  609.34  655.79  609.37  664.77  612.32
#Mann= 3 , 0 , 0
       0      .1       0  449.58    .041       0  543.35      .1       0
Bank Sta=449.58,543.35
XS Rating Curve= 0 ,0
Exp/Cntr=0.3,0.1

Type RM Length L Ch R = 1 ,10005.2 ,55.52,47.07,11.83
XS GIS Cut Line= 6
     625776.9906    4318375.1384     625801.6954    4318703.7213
     625869.7411    4318858.9286     625994.4668    4318838.1035
     626062.4227    4318760.4848     626063.9318    4318725.4916
#Sta/Elev= 30
       0  621.06    12.2  618.05   45.77  613.89   70.17  609.91  128.14  605.79
   155.6  604.84  164.76  603.28  176.96  599.79  189.16  597.48  228.83  597.53
  277.64  596.52  386.94  595.62  389.97  595.45  399.04  593.18  414.15  594.85
  508.45  592.62  522.88  591.74  558.77  591.03  603.62  591.27  611.58  592.75
  624.82  595.64  663.56  597.63   684.9     598  706.25  599.76  718.44  601.37
  724.54  601.05  730.64  601.72  751.07  608.42  756.91  609.35  765.66  612.17
#Mann= 3 , 0 , 0
       0      .1       0  508.45    .041       0  611.58      .1       0
Bank Sta=508.45,611.58
XS Rating Curve= 0 ,0
Exp/Cntr=0.3,0.1

Type RM Length L Ch R = 1 ,9958.127,119.4,135.81,15.17
XS GIS Cut Line= 6
     625771.5887     4318374.036     625797.4477    4318704.7422
     625849.9676    4318793.4109     625878.5427    4318900.9642
     625998.8221    4318858.6884     626067.1289    4318724.4773
#Sta/Elev= 30
       0  620.97   12.29   617.5   46.07  613.61   70.64  610.07     129   605.7
  153.57  605.17  165.86  603.88  181.22  599.19   193.5  597.31  227.29  597.57
   279.5  596.51  392.34  595.56  404.46  593.15  416.58  594.89  494.92  593.02
  602.72  591.57  611.83  591.02  667.92  591.04  676.71  591.62  679.64  592.85
  694.48     596  709.37   595.9   745.7  597.45  769.95  597.69  791.17  600.65
  797.24  600.58  803.12  601.86  823.12  608.49  825.97  608.59  837.39  611.95
#Mann= 3 , 0 , 0
       0      .1       0  602.72    .041       0  676.71      .1       0
Bank Sta=602.72,676.71
XS Rating Curve= 0 ,0
Exp/Cntr=0.3,0.1

River Reach=Dry Fork        ,6
Reach XY= 30
     625923.9652     4318948.156     625950.9341    4318968.4631
     626000.6826    4318967.2324     626080.3156     4318939.888
     626156.5317    4318892.1024     626237.4784    4318825.5878
     626295.4223     4318799.394     626390.8839    4318732.7367
     626487.5102    4318632.7062     626539.8978    4318620.7999
     626746.2732      4318677.95     626802.6295    4318724.7814
     626847.8734    4318743.8314     626897.8797     4318777.169
     626939.9486    4318814.4753     626985.3317    4318832.0094
     627021.8443    4318869.3157     627039.1675    4318900.9942
     627082.9049    4318911.3416     627188.7934     4318980.574
     627211.4116    4318981.1631     627247.9242    4319000.2132
      627296.343    4319043.8695     627340.2782    4319111.4326
     627366.1932    4319187.5385     627364.6057    4319281.2012
     627333.6493    4319341.5264     627303.6261    4319462.2481
     627240.1739    4319506.6186     627141.3213    4319540.3754

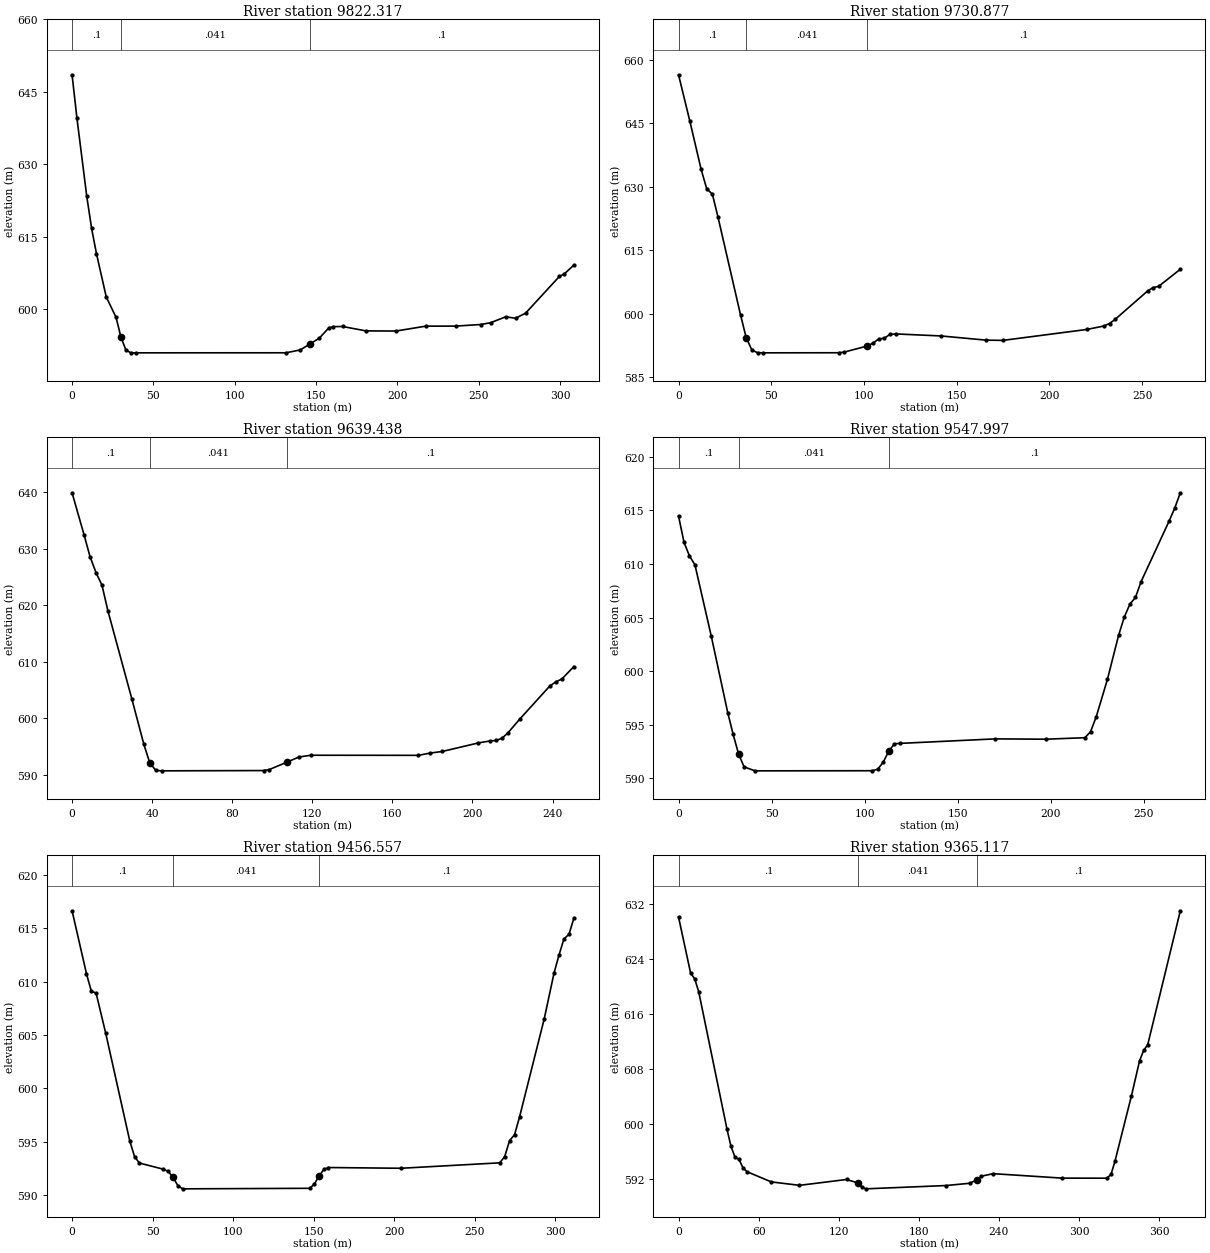
Type RM Length L Ch R = 1 ,9822.317,95.72,91.44,57.85
XS GIS Cut Line= 6
      626010.411    4319009.6594      625986.125    4318907.6469
     626016.4118    4318868.0434     626019.0576    4318845.5537
     626072.6724    4318759.8118     626071.8252    4318730.1122
#Sta/Elev= 30
       0  648.55       3  639.56       9  623.48   12.01  616.76   15.01  611.53
   21.01  602.59   27.01  598.39   30.01  594.32   33.01  591.67   36.02  591.04
   39.02  591.03  131.47  591.04  140.26  591.63  146.13  592.85  151.99  594.07
  157.76  596.19  160.59  596.45  166.25  596.48  180.64  595.57  199.02  595.54
  217.41  596.55   235.8  596.56  251.12  596.89  257.25  597.26  266.44  598.48
  272.57  598.19   278.7  599.22  299.49  606.83  302.47  607.34  308.41  609.18
#Mann= 3 , 0 , 0
       0      .1       0   30.01    .041       0  146.13      .1       0
Bank Sta=30.01,146.13
XS Rating Curve= 0 ,0
Exp/Cntr=0.3,0.1

Type RM Length L Ch R = 1 ,9730.877,97.46,91.44,56.83
XS GIS Cut Line= 6
     626106.4564    4318985.9061     626092.7994    4318942.3717
     626076.3079    4318917.2198     626075.1318    4318848.5876
      626079.044    4318757.8967     626075.0003    4318722.9684
#Sta/Elev= 30
       0  656.41    6.08  645.49   12.17  634.09   15.21  629.45   18.25  628.22
   21.29  622.76   33.46  599.63    36.5  594.28   39.54  591.39   42.58  590.75
   45.63  590.72   86.41  590.74   89.48  590.91  101.73  592.33   104.8     593
  107.86  593.98  110.93  594.19  113.99  595.06  117.05  595.19  141.57  594.71
  165.81  593.72  174.89  593.66  220.28  596.25  229.36  597.06  232.38  597.65
  235.41  598.62  252.99  605.36  255.92  606.14  258.85  606.42  270.57  610.47
#Mann= 3 , 0 , 0
       0      .1       0    36.5    .041       0  101.73      .1       0
Bank Sta=36.5,101.73
XS Rating Curve= 0 ,0
Exp/Cntr=0.3,0.1

Type RM Length L Ch R = 1 ,9639.438,89.46,91.44,87.85
XS GIS Cut Line= 6
     626200.0232    4318938.1952     626172.4244    4318895.5718
     626156.5608    4318876.2662     626137.9054    4318858.8199
     626102.0643    4318814.7831     626078.1753    4318725.3496
#Sta/Elev= 29
       0  639.87    5.97  632.46    8.96  628.59   11.95  625.75   14.93  623.53
   17.92  618.97   29.87   603.4   35.84   595.4   38.83  592.09   41.82  590.77
    44.8  590.69   95.63  590.74   98.47  590.91  107.28  592.22  113.26  593.13
  119.24  593.45  173.02  593.43  178.99  593.84  184.96  594.12  202.88  595.62
  208.85  595.98  211.84  596.06  214.82  596.46  217.81  597.44  223.78   599.9
  238.71  605.72   241.7  606.43  244.68  606.94  250.66  609.13
#Mann= 3 , 0 , 0
       0      .1       0   38.83    .041       0  107.28      .1       0
Bank Sta=38.83,107.28
XS Rating Curve= 0 ,0
Exp/Cntr=0.3,0.1

Type RM Length L Ch R = 1 ,9547.997,85.29,91.44,96.63
XS GIS Cut Line= 6
     626270.4074    4318893.0877     626250.9528    4318847.1092
     626222.3042    4318812.2445     626200.7441    4318795.9647
      626172.169    4318765.0083     626117.9951    4318674.4834
#Sta/Elev= 30
       0  614.48    2.94  612.02    5.87  610.75    8.81  609.93   17.62  603.25
   26.43  596.15   29.37   594.1    32.3  592.26   35.24  591.08   41.11  590.71
  104.09  590.72  107.06  590.86  110.06  591.53  113.06  592.57  116.06  593.23
  119.06  593.27  170.22  593.69  197.35  593.66  218.45   593.8  221.46  594.37
  224.48  595.74  230.51  599.24  236.54  603.37  239.55  605.03  242.56  606.25
  245.58  606.88  248.59  608.35  263.66     614  266.68  615.21  269.69  616.64
#Mann= 3 , 0 , 0
       0      .1       0    32.3    .041       0  113.06      .1       0
Bank Sta=32.3,113.06
XS Rating Curve= 0 ,0
Exp/Cntr=0.3,0.1

Type RM Length L Ch R = 1 ,9456.557,99.41,91.44,114.14
XS GIS Cut Line= 5
     626347.3921    4318891.0869     626332.0896    4318808.9408
     626302.1963    4318766.1297     626272.2888    4318734.2015
     626197.7777     4318625.388
#Sta/Elev= 30
       0  616.65    8.95  610.74   11.94  609.11   14.92  608.92   20.89  605.15
   35.81  595.05    38.8  593.58   41.78  592.98    56.7   592.4   59.69  592.19
   62.67  591.64   65.65  590.86   68.64  590.56  147.44  590.61  150.36  591.01
  153.27  591.76  156.19  592.38  159.11  592.56  204.06  592.49   265.4     593
  268.46  593.58  271.53  595.09   274.6  595.64  277.67  597.29     293   606.5
  299.13  610.83   302.2  612.51  305.27  614.02  308.33  614.43   311.4  615.94
#Mann= 3 , 0 , 0
       0      .1       0   62.67    .041       0  153.27      .1       0
Bank Sta=62.67,153.27
XS Rating Curve= 0 ,0
Exp/Cntr=0.3,0.1

Type RM Length L Ch R = 1 ,9365.117,99.44,91.44,64.26
XS GIS Cut Line= 6
     626452.1678    4318904.8451     626431.7227    4318807.2928
     626411.1098    4318762.3887     626378.3187    4318715.4278
     626370.2069    4318684.2613      626325.167    4318554.5362
#Sta/Elev= 30
       0  630.14    9.06  621.96   12.08  621.16    15.1  619.27   36.24   599.3
   39.26  596.76   42.28  595.18   45.31  594.84   48.33   593.6   51.35  593.05
   69.47  591.57   90.61  591.07  125.83  591.92  134.55  591.41  137.46  590.78
  140.36  590.56  200.33  591.04  218.07  591.37  223.92  591.91  226.85   592.4
  235.63  592.77  287.39  592.12  320.95  592.11  324.01  592.68  327.06  594.68
  339.26   604.1  345.37  609.22  348.42  610.72  351.47  611.56  375.88  631.05
#Mann= 3 , 0 , 0
       0      .1       0  134.55    .041       0  223.92      .1       0
Bank Sta=134.55,223.92
XS Rating Curve= 0 ,0
Exp/Cntr=0.3,0.1