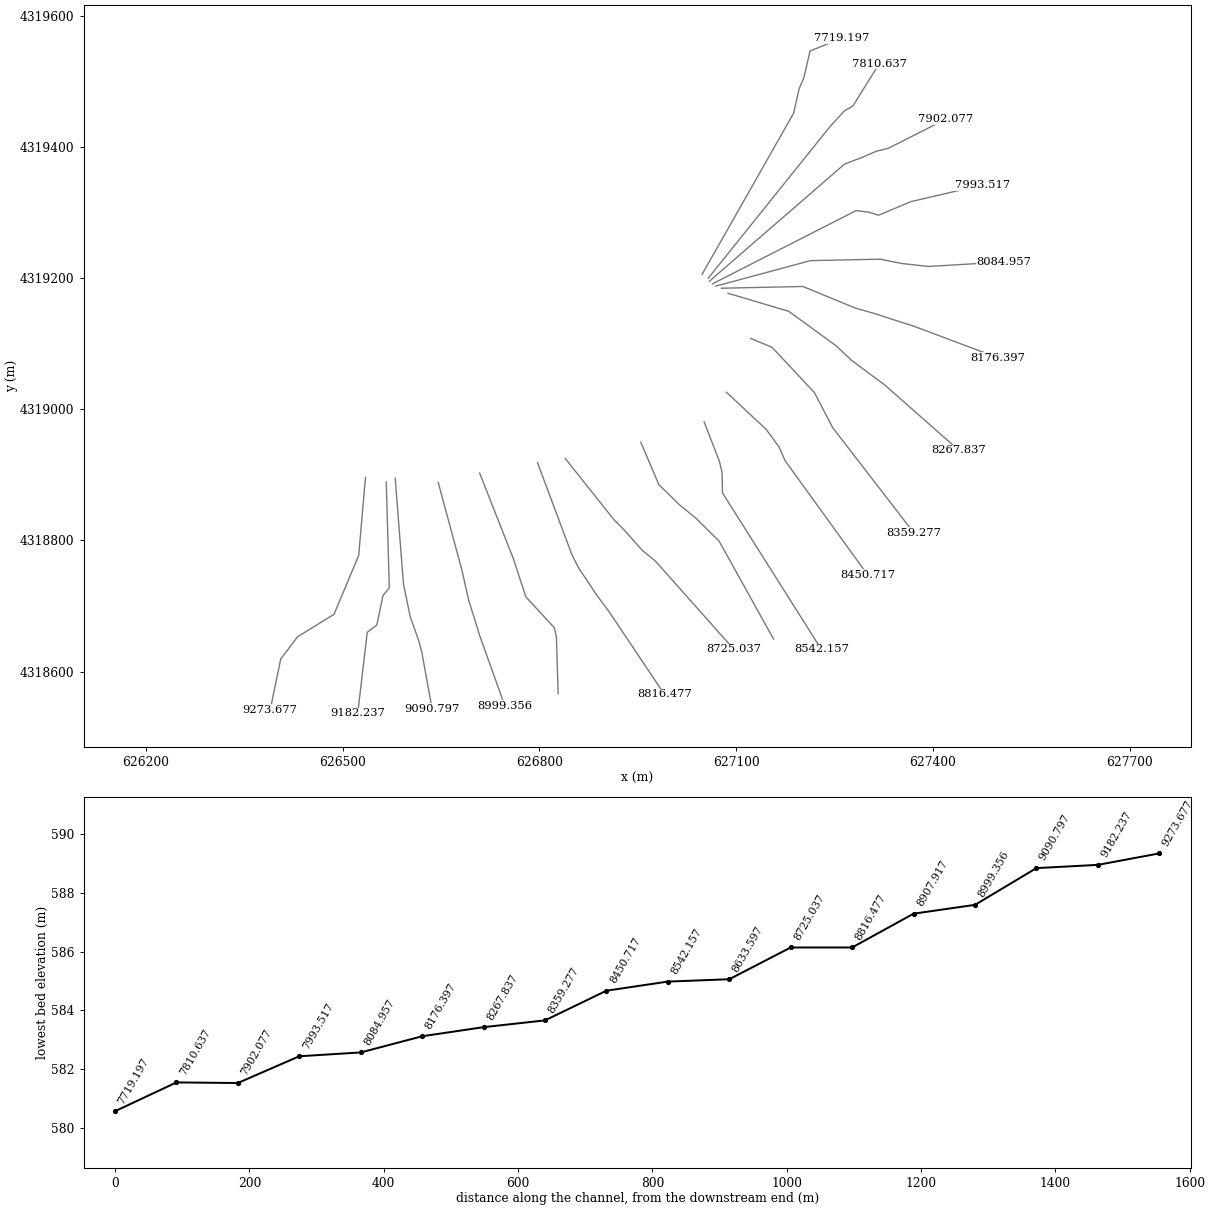
HEC-RAS study RedCreek.prj: RedCreek

--- RedCreek.g01 (geometry) --- (continued)

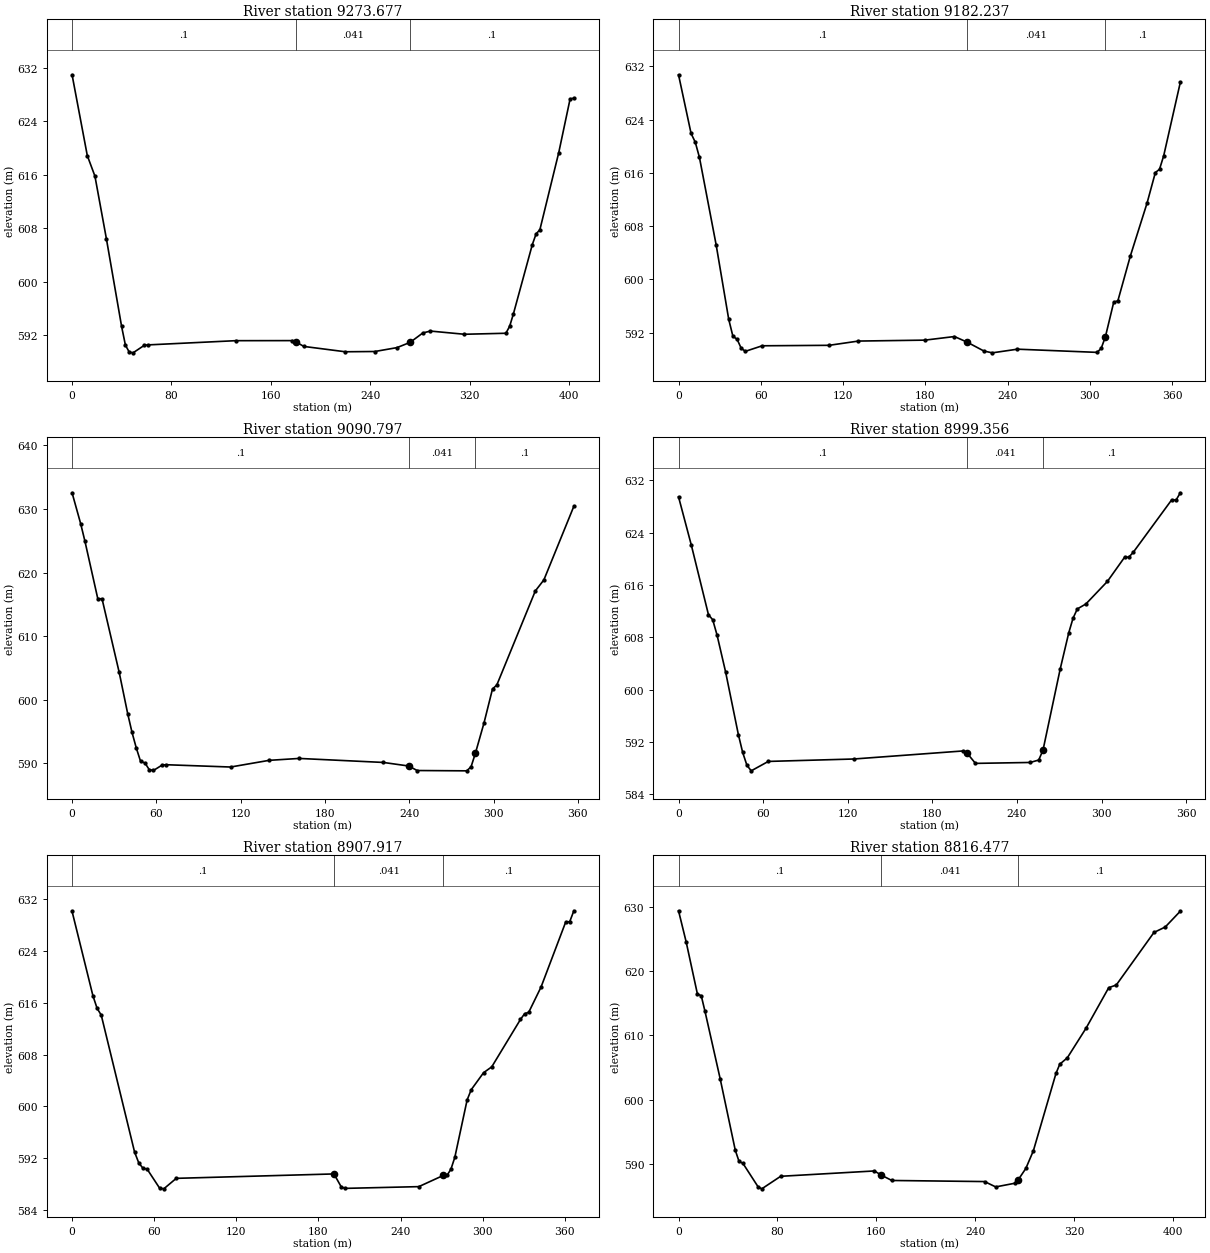
Type RM Length L Ch R = 1 ,9273.677,60.16,91.44,117.68
XS GIS Cut Line= 6
     626534.7174    4318896.3786      626524.327    4318777.1964
     626486.6804    4318687.3956     626431.0472    4318653.1141
     626405.4061     4318619.112     626389.3893    4318541.7167
#Sta/Elev= 30
       0  630.95   12.27  618.85   18.41  615.78   27.61  606.44   39.88  593.29
   42.95  590.49   46.01  589.46   49.08  589.34   58.28  590.48   61.35  590.53
  131.81  591.16  177.45  591.17  180.49  590.95  186.58   590.3  219.98   589.5
  243.74  589.54  261.56  590.12  272.19  590.91  282.35  592.31  288.44   592.6
  315.82  592.12  349.26  592.27   352.3  593.32  355.34  595.19  370.54  605.54
  373.58  607.14  376.62  607.76  391.82  619.31  400.94  627.33  403.98  627.45
#Mann= 3 , 0 , 0
       0      .1       0  180.49    .041       0  272.19      .1       0
Bank Sta=180.49,272.19
XS Rating Curve= 0 ,0
Exp/Cntr=0.3,0.1

Type RM Length L Ch R = 1 ,9182.237,35.89,91.44,98.13
XS GIS Cut Line= 6
     626566.3293    4318889.2462     626571.0261    4318727.6531
     626561.4303    4318716.1371      626551.976    4318671.0321
     626537.3889    4318659.9877     626522.8461    4318536.3234
#Sta/Elev= 30
       0  630.74    9.15  621.92    12.2  620.61   15.25  618.32   27.45  605.16
    36.6  593.99   39.65  591.44    42.7  590.99   45.75  589.62    48.8  589.18
      61  590.01  109.81  590.08  131.16  590.72  179.72  590.86  201.23   591.4
  210.45  590.56  222.74  589.22  228.84  588.95  247.16   589.5  305.23  589.02
  308.26  589.63   311.3  591.35  317.37  596.55  320.41  596.77  329.52  603.51
  341.67  611.44  347.74  616.04  350.78  616.54  353.81  618.55  365.96  629.61
#Mann= 3 , 0 , 0
       0      .1       0  210.45    .041       0   311.3      .1       0
Bank Sta=210.45,311.3
XS Rating Curve= 0 ,0
Exp/Cntr=0.3,0.1

Type RM Length L Ch R = 1 ,9090.797,92,91.44,94.53
XS GIS Cut Line= 6
     626580.0021    4318894.9097      626592.603    4318733.8121
     626602.8213    4318683.9831     626615.9339     4318647.103
     626620.3841    4318630.5637     626636.2194    4318543.6217
#Sta/Elev= 30
       0  632.54     6.1   627.7    9.15  624.93   18.29  615.91   21.34  615.87
   33.54  604.31   39.64  597.77   42.68  594.87   45.73  592.41   48.78  590.31
   51.83  590.09   54.88  589.04   57.93   588.9   64.03  589.74   67.07   589.8
  112.81  589.44  140.25  590.49  161.59  590.79  221.49  590.16  239.55   589.6
  245.58  588.89  280.91  588.84  283.96  589.49  287.01  591.59   293.1  596.32
   299.2  601.71  302.25  602.32  329.67  617.11  335.77  618.85   357.1  630.42
#Mann= 3 , 0 , 0
       0      .1       0  239.55    .041       0  287.01      .1       0
Bank Sta=239.55,287.01
XS Rating Curve= 0 ,0
Exp/Cntr=0.3,0.1

Type RM Length L Ch R = 1 ,8999.356,82.46,91.44,113.79
XS GIS Cut Line= 5
     626645.6399     4318888.536     626681.9992    4318753.9086
     626691.6757    4318710.5638     626709.2494    4318653.8258
     626747.2278    4318547.8011
#Sta/Elev= 30
       0  629.49    9.09  622.09   21.22  611.47   24.25  610.69   27.28  608.38
   33.35  602.74   42.44  593.13   45.47  590.42    48.5  588.44   51.54  587.59
   63.66  589.03  124.29   589.4  201.68  590.63  204.65  590.29  210.59  588.73
  249.35  588.87  255.44  589.24  258.48  590.75  270.65  603.13  276.74  608.69
  279.79  610.93  282.83  612.35  288.92  613.11  304.14  616.55  316.31  620.24
  319.36  620.27   322.4  620.98  349.79  629.04  352.84  628.99  355.88  630.11
#Mann= 3 , 0 , 0
       0      .1       0  204.65    .041       0  258.48      .1       0
Bank Sta=204.65,258.48
XS Rating Curve= 0 ,0
Exp/Cntr=0.3,0.1

Type RM Length L Ch R = 1 ,8907.917,86.8,91.44,91.81
XS GIS Cut Line= 6
     626708.7574    4318902.8428     626760.1308    4318772.5353
     626779.3333    4318713.9384     626822.5256    4318667.1468
     626825.8256    4318653.3645     626828.5378    4318566.4425
#Sta/Elev= 30
       0  630.11   15.22   617.1   18.27  615.15   21.31   614.1   45.67  592.96
   48.72   591.3   51.76  590.47   54.81  590.34   63.94   587.4   66.99  587.29
   76.12  588.91  191.31  589.59  196.53  587.63  199.14  587.36   253.3  587.63
   271.1  589.35  273.93  589.38  276.76  590.32   279.6  592.15  288.59  601.01
  291.59  602.59  300.59  605.21  306.59  606.12  327.58  613.44  330.58  614.31
  333.58  614.53  342.57  618.42  360.57  628.45  363.56  628.53  366.56   630.2
#Mann= 3 , 0 , 0
       0      .1       0  191.31    .041       0   271.1      .1       0
Bank Sta=191.31,271.1
XS Rating Curve= 0 ,0
Exp/Cntr=0.3,0.1

Type RM Length L Ch R = 1 ,8816.477,83.48,91.44,104.55
XS GIS Cut Line= 6
     626796.9818    4318918.7624     626849.4891    4318778.3912
     626859.7131    4318758.2989     626888.1254    4318715.6806
      626905.899    4318691.8386     626990.6572    4318565.2783
#Sta/Elev= 30
       0  629.36    6.12  624.56   15.29   616.4   18.35  616.17   21.41  613.71
   33.64  603.27   45.88  592.14   48.94  590.39      52  590.12   64.23  586.48
   67.29  586.14   82.58  588.09  158.32  588.92  163.96  588.27  172.41  587.44
  247.43  587.27  256.42  586.44  271.65     587   274.7  587.57  280.79  589.31
  286.88  592.06  305.16  604.08  308.21  605.51   314.3   606.5  329.53  611.13
  347.81  617.41   353.9  617.82  384.37  625.99  393.51  626.84  405.69   629.3
#Mann= 3 , 0 , 0
       0      .1       0  163.96    .041       0   274.7      .1       0
Bank Sta=163.96,274.7
XS Rating Curve= 0 ,0
Exp/Cntr=0.3,0.1

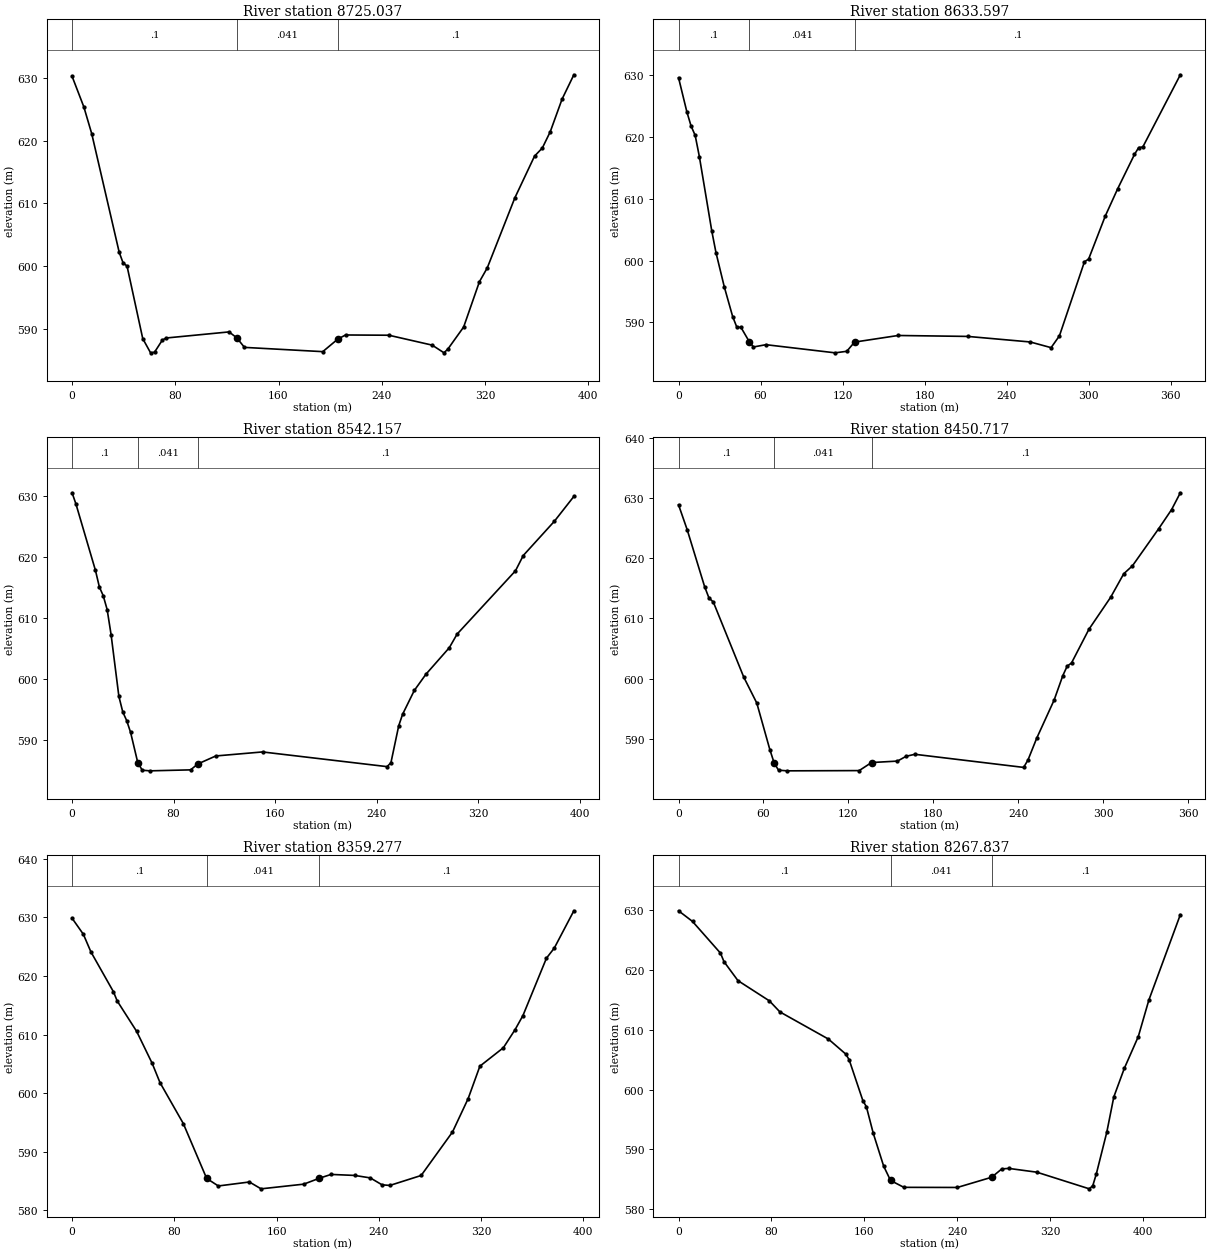
Type RM Length L Ch R = 1 ,8725.037,93.11,91.44,91.02
XS GIS Cut Line= 6
     626839.3152    4318925.1124     626913.2164    4318832.2474
     626929.9419    4318815.1919      626956.511     4318785.231
      626976.847    4318768.5445     627096.4907    4318634.0701
#Sta/Elev= 30
       0  630.27    9.13  625.38   15.22  621.12   36.52  602.19   39.56  600.48
    42.6  599.99   54.78  588.41   60.86  586.14   63.91  586.24   69.99  588.18
   73.03  588.51  121.67  589.48  127.64  588.54  133.61  587.01  194.31  586.33
     206  588.34  211.97  588.99  245.53  588.95  279.09  587.37  288.24  586.15
  291.29  586.75  303.49  590.26   315.7  597.48   321.8   599.7  343.15  610.86
  358.41  617.52  364.51  618.84  370.61  621.42  379.76  626.62  388.91  630.51
#Mann= 3 , 0 , 0
       0      .1       0  127.64    .041       0     206      .1       0
Bank Sta=127.64,206
XS Rating Curve= 0 ,0
Exp/Cntr=0.3,0.1

Type RM Length L Ch R = 1 ,8633.597,100.39,91.44,50.69
XS GIS Cut Line= 6
     626954.6281    4318949.7277     626982.0663    4318885.2649
      627013.901    4318854.1075     627038.1312    4318834.4259
     627074.0865    4318798.9502     627157.0625    4318649.6119
#Sta/Elev= 30
       0  629.62    6.09  624.09    9.14  621.82   12.18  620.27   15.23  616.85
   24.37  604.74   27.41  601.28   33.51  595.72    39.6  590.94   42.64  589.22
   45.69  589.18   51.78  586.86   54.83  586.01   63.97  586.38   114.6  585.06
  123.12  585.31  128.79   586.8  160.68  587.87  211.58  587.72  257.35  586.82
   272.6   585.9   278.7  587.81  297.01  599.81  300.06  600.24  312.26  607.22
  321.41  611.67  333.61  617.18  336.67   618.3  339.72   618.4  367.17  630.09
#Mann= 3 , 0 , 0
       0      .1       0   51.78    .041       0  128.79      .1       0
Bank Sta=51.78,128.79
XS Rating Curve= 0 ,0
Exp/Cntr=0.3,0.1

Type RM Length L Ch R = 1 ,8542.157,78.78,91.44,109.88
XS GIS Cut Line= 5
     627051.1464    4318981.0291     627074.4536    4318920.8497
     627078.4921    4318903.7792     627079.1316    4318872.5986
      627229.841    4318634.0701
#Sta/Elev= 30
       0  630.59    3.07  628.74   18.44  617.85   21.51  615.14   24.58  613.69
   27.66  611.42   30.73  607.34   36.88   597.2   39.95  594.64   43.02  593.23
    46.1   591.3   51.76  586.34   55.32  585.08   61.46  584.98   93.42  585.14
   99.09  586.11  113.26  587.42  150.07  588.08  248.21  585.67  251.27  586.31
  257.41  592.38  260.47  594.26  269.67  598.16  278.87  600.83  297.28  605.18
  303.41  607.41  349.41  617.79  355.55   620.3  380.08  625.92  395.42  629.99
#Mann= 3 , 0 , 0
       0      .1       0   51.76    .041       0   99.09      .1       0
Bank Sta=51.76,99.09
XS Rating Curve= 0 ,0
Exp/Cntr=0.3,0.1

Type RM Length L Ch R = 1 ,8450.717,95.06,91.44,89.73
XS GIS Cut Line= 5
     627085.1136    4319026.1834     627145.6978    4318969.5765
      627165.276    4318942.9992     627174.6794    4318921.6662
     627300.7495     4318747.312
#Sta/Elev= 30
       0  628.89    6.14  624.73   18.43  615.28    21.5   613.4   24.57  612.73
   46.06  600.25   55.28  595.93   64.49   588.2   67.56  585.96   70.63  584.78
   76.77  584.67  127.58  584.71  136.32  586.05  154.61  586.29  160.75  587.09
   166.9  587.42  243.74  585.24  246.82  586.48  252.96  590.09  265.26  596.43
  271.41   600.5  274.48  602.07  277.55   602.6  289.85   608.2  305.22  613.53
  314.44  617.43  320.59  618.75  339.03  624.89  348.25   628.1   354.4  630.89
#Mann= 3 , 0 , 0
       0      .1       0   67.56    .041       0  136.32      .1       0
Bank Sta=67.56,136.32
XS Rating Curve= 0 ,0
Exp/Cntr=0.3,0.1

Type RM Length L Ch R = 1 ,8359.277,71.91,91.44,105.73
XS GIS Cut Line= 5
     627122.1554    4319108.2044     627154.7612    4319094.6207
      627219.243    4319025.8071      627247.351    4318971.9334
     627370.8642    4318811.8705
#Sta/Elev= 30
       0  629.86    8.83  627.12   14.72  624.12   32.38   617.3   35.32  615.73
   50.53  610.54    62.7  605.07   68.78   601.8   87.04   594.8  105.29  585.44
  114.42  584.15  138.74  584.83  147.86  583.66  181.28  584.46  193.45  585.47
  202.64  586.12  221.02  585.95  233.28  585.53  242.47  584.35  248.59  584.24
   273.1  585.94  297.61  593.36  309.86  599.06  319.05   604.6  337.43  607.75
  346.62  610.85  352.75  613.25  371.13  623.04  377.25  624.76  392.57  631.13
#Mann= 3 , 0 , 0
       0      .1       0  105.29    .041       0  193.45      .1       0
Bank Sta=105.29,193.45
XS Rating Curve= 0 ,0
Exp/Cntr=0.3,0.1

Type RM Length L Ch R = 1 ,8267.837,63.3,91.44,105.61
XS GIS Cut Line= 6
     627087.7595    4319176.9962     627180.0609    4319149.6253
     627252.1761    4319097.1779     627276.8846    4319074.0186
     627326.6447    4319037.1875      627439.656    4318937.5478
#Sta/Elev= 30
       0  629.84   12.03  628.06    36.1  622.77   39.11  621.35   51.15  618.18
   78.22   614.8   87.25  612.96  128.97  608.43  143.83  605.94   146.8     605
  158.69  598.13  161.67  597.14  167.61  592.69  176.53  587.23  182.47  584.83
  193.91  583.68  239.95  583.66  269.43  585.36  278.27  586.76  284.23  586.84
  308.34  586.21  353.54  583.43  356.55  583.97  359.56   585.9   368.6  592.89
  374.63  598.77  383.67  603.54  395.72  608.85  404.76  614.92  431.88  629.19
#Mann= 3 , 0 , 0
       0      .1       0  182.47    .041       0  269.43      .1       0
Bank Sta=182.47,269.43
XS Rating Curve= 0 ,0
Exp/Cntr=0.3,0.1

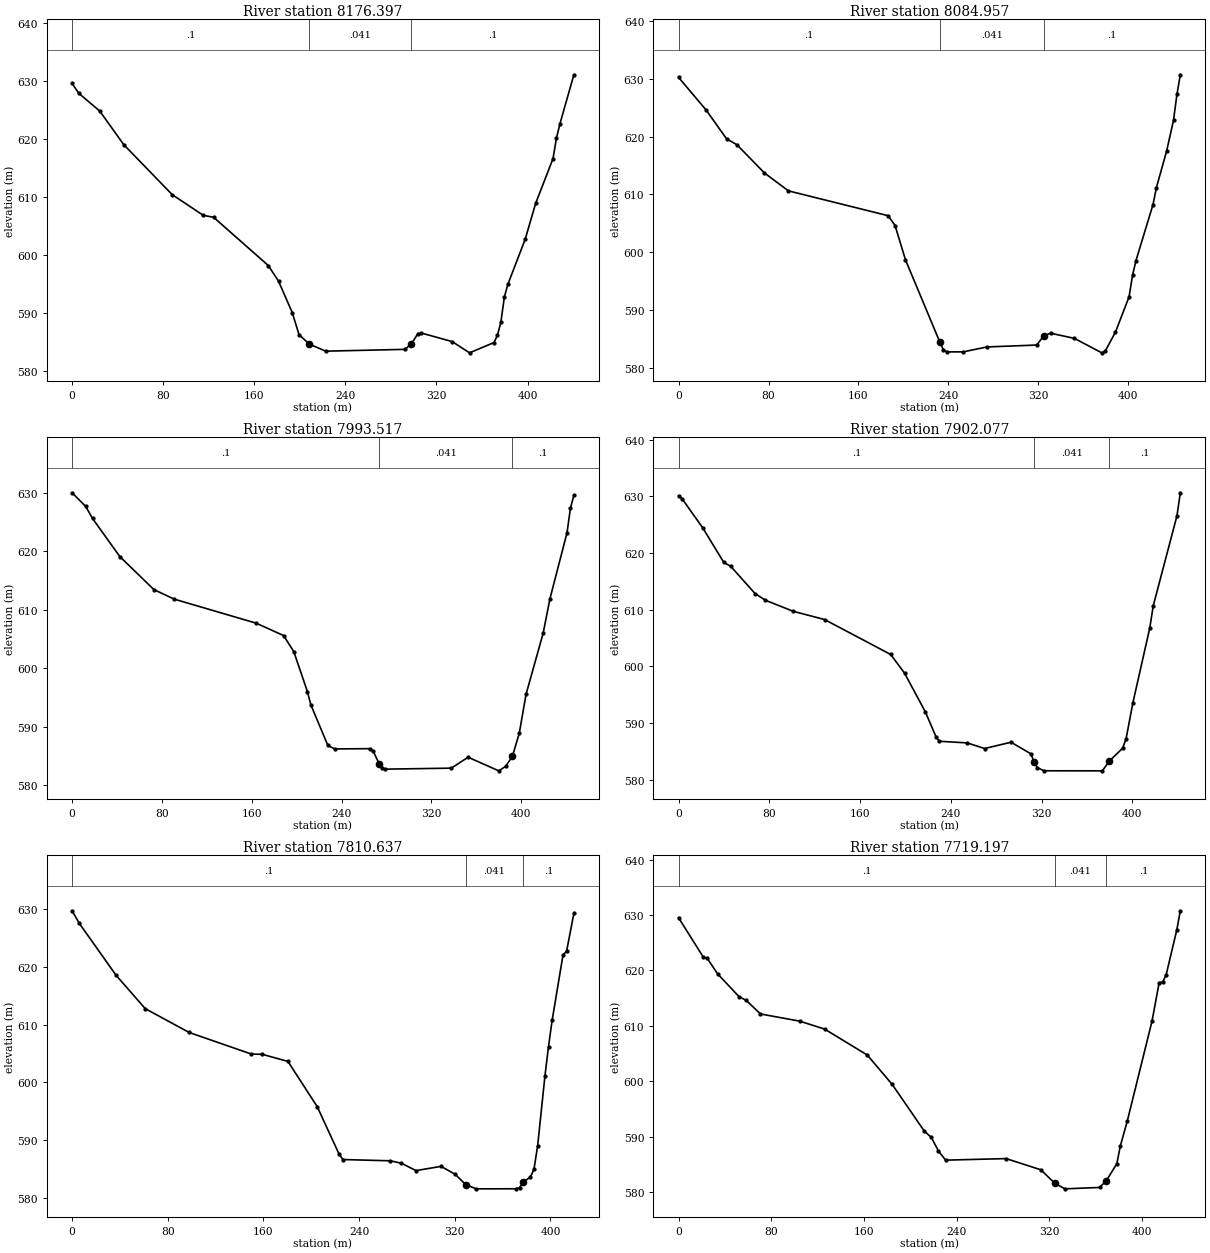
Type RM Length L Ch R = 1 ,8176.397,72.9,91.44,97.33
XS GIS Cut Line= 6
      627077.573    4319184.7353     627201.8422    4319187.4014
     627282.3148    4319154.2779     627309.6666    4319146.5242
     627373.0323    4319126.0827     627498.7422    4319078.8589
#Sta/Elev= 30
       0  629.62    6.06  627.89   24.25  624.87   45.47  619.04   87.92  610.43
   115.2  606.86   124.3  606.52  172.31  598.19  181.31  595.49  193.32  590.08
  199.32  586.26  208.32  584.63  222.69  583.41  292.31  583.72  297.93  584.66
  303.54  586.39  306.35  586.56  333.82  585.06  349.08  583.12  370.44  584.89
   373.5  586.13  376.55  588.42   379.6  592.74  382.65  594.93  397.91  602.73
  407.07  608.91  422.33  616.65  425.38  620.21  428.43  622.67  440.64  631.12
#Mann= 3 , 0 , 0
       0      .1       0  208.32    .041       0  297.93      .1       0
Bank Sta=208.32,297.93
XS Rating Curve= 0 ,0
Exp/Cntr=0.3,0.1

Type RM Length L Ch R = 1 ,8084.957,74.44,91.44,103.73
XS GIS Cut Line= 6
     627068.8417    4319187.9103     627213.3045    4319226.8041
     627319.8566    4319229.0465     627352.1289    4319222.5227
     627393.4109     4319217.934     627508.6018    4319224.8554
#Sta/Elev= 30
       0  630.24   24.43  624.62   42.74   619.6    51.9  618.59   76.33  613.71
    97.7   610.6  186.42   606.3  192.55   604.6  201.75  598.69  232.43  584.39
  235.49  583.12  238.45  582.73  253.25  582.74  274.17  583.59  318.53  583.92
  324.67  585.49   330.8  585.97  352.06  585.07  376.36  582.57  379.39  582.86
   388.5  586.15  400.65  592.28  403.69  595.98  406.72  598.51  421.91  608.23
  424.94  611.17  434.05  617.52  440.13   622.8  443.17  627.28   446.2  630.69
#Mann= 3 , 0 , 0
       0      .1       0  232.43    .041       0  324.67      .1       0
Bank Sta=232.43,324.67
XS Rating Curve= 0 ,0
Exp/Cntr=0.3,0.1

Type RM Length L Ch R = 1 ,7993.517,82.87,91.44,98.06
XS GIS Cut Line= 6
     627063.8411    4319191.4028     627282.9604    4319303.1116
     627302.4073    4319300.7304     627317.2207    4319296.0576
     627366.6608    4319316.8225     627475.7982    4319342.2156
#Sta/Elev= 30
       0  630.05   12.15  627.71   18.22  625.65   42.51  619.13   72.87  613.47
   91.09  611.83  163.97  607.72  188.26  605.61  197.37  602.87  209.51  596.02
  212.55  593.76  227.73  586.79  233.81  586.19  265.54  586.24  268.13  585.82
  273.31  583.68   275.9  582.89  278.49  582.73  337.68   582.9   352.6  584.77
  379.94  582.44  386.01   583.2  392.09  584.94  398.16  588.88  404.23  595.57
  419.42  606.01   425.5  611.93  440.68  623.21  443.72  627.42  446.76   629.6
#Mann= 3 , 0 , 0
       0      .1       0  273.31    .041       0  392.09      .1       0
Bank Sta=273.31,392.09
XS Rating Curve= 0 ,0
Exp/Cntr=0.3,0.1

Type RM Length L Ch R = 1 ,7902.077,71.47,91.44,104.96
XS GIS Cut Line= 6
     627059.0786    4319195.3716     627265.2598    4319373.9936
     627292.2473    4319384.3124     627313.7234    4319393.6514
     627331.7029    4319397.9768     627419.7142    4319442.4659
#Sta/Elev= 30
       0  630.09    3.07  629.58   21.46  624.39   39.85  618.33   45.98  617.64
   67.43  612.83   76.63  611.64  101.15  609.69  128.73  608.24  186.97  602.07
  199.23  598.76  217.62  591.89  226.82  587.58  229.88  586.75   254.4  586.46
  269.73  585.47  293.02  586.58  310.47  584.54   313.4  583.09  316.32  582.07
  322.18  581.54  373.48  581.53  379.46   583.2  391.41  585.54   394.4  587.18
  400.38  593.53  415.32  606.78  418.31  610.64  439.23  626.55  442.21  630.62
#Mann= 3 , 0 , 0
       0      .1       0   313.4    .041       0  379.46      .1       0
Bank Sta=313.4,379.46
XS Rating Curve= 0 ,0
Exp/Cntr=0.3,0.1

Type RM Length L Ch R = 1 ,7810.637,72.34,91.44,98.17
XS GIS Cut Line= 5
     627057.4911    4319200.1341     627243.3434     4319431.502
     627265.1716    4319455.3146     627278.0361    4319462.5661
     627317.9662    4319526.8906
#Sta/Elev= 30
       0  629.76    6.12  627.56   36.71   618.6   61.19  612.79    97.9  608.66
  149.91  604.92  159.09  604.87  180.51  603.64  204.99  595.79  223.34  587.53
   226.4  586.63  266.17  586.41  275.35  585.99  287.59  584.71  308.52  585.45
  320.26  584.08  329.07   582.3  337.83  581.55   371.1  581.56  374.12  581.75
  377.15  582.73  383.21  583.58  386.24  584.99  389.27  589.02  395.32  601.03
  398.35  606.22  401.38  610.76  410.47  622.08  413.49  622.76  419.55   629.3
#Mann= 3 , 0 , 0
       0      .1       0  329.07    .041       0  377.15      .1       0
Bank Sta=329.07,377.15
XS Rating Curve= 0 ,0
Exp/Cntr=0.3,0.1

Type RM Length L Ch R = 1 ,7719.197,88.82,91.44,67.1
XS GIS Cut Line= 6
      627047.966    4319205.6903     627187.6123    4319451.6095
     627196.2034     4319489.512     627203.2962    4319505.8668
     627212.7278    4319546.6343     627260.8501    4319565.8568
#Sta/Elev= 30
       0  629.52   21.52  622.36   24.59  622.24   33.81  619.36   52.26  615.26
    58.4   614.6    70.7  612.14  104.51  610.85  126.03  609.42  162.92  604.73
  184.44  599.42   212.1  591.01  218.25  589.84   224.4   587.4  230.55  585.75
   282.8  586.03   312.7  584.01  324.64  581.61  333.55  580.57   363.4  580.82
  369.38  582.07  378.35  585.11  381.34  588.28  387.43  592.86  408.77  610.89
  414.87  617.78  417.92  617.91  420.96  619.24  430.11  627.32  433.16  630.77
#Mann= 3 , 0 , 0
       0      .1       0  324.64    .041       0  369.38      .1       0
Bank Sta=324.64,369.38
XS Rating Curve= 0 ,0
Exp/Cntr=0.3,0.1