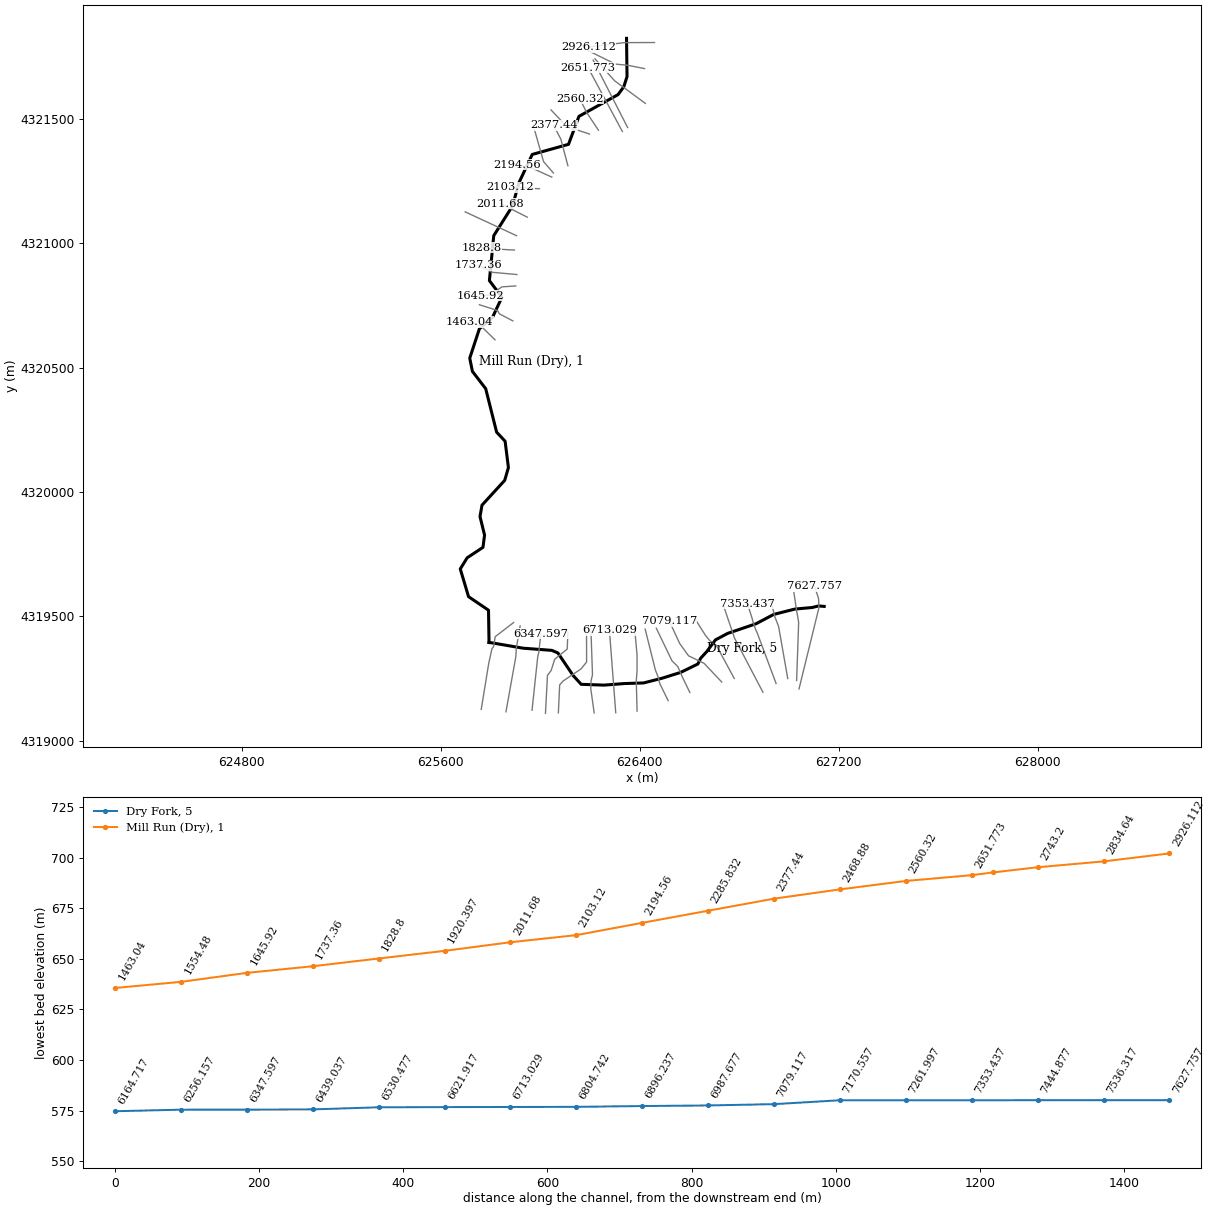
HEC-RAS study RedCreek.prj: RedCreek

--- RedCreek.g01 (geometry) --- (continued)

River Reach=Dry Fork        ,5
Reach XY= 30
     627141.3213    4319540.3754     627118.6247    4319542.3172
     627093.1426    4319535.9955     627023.4318     4319529.717
     626938.3611    4319508.2142     626867.7172    4319470.9079
     626753.4169     4319432.014     626735.2859    4319422.3637
     626722.3353    4319415.4705     626704.2043    4319405.8202
     626691.9806    4319389.4292      626681.503    4319375.3799
     626678.0106    4319370.6967     626671.0255    4319361.3305
     626669.2793    4319358.9889      626644.673    4319332.0013
     626633.5604    4319308.9825     626571.7241    4319278.7326
     626561.3638    4319274.2078     626489.8914    4319251.8324
     626415.2788    4319232.7824     626339.0786    4319230.4011
     626256.5284    4319224.0511     626164.4533    4319227.2261
     626131.9094    4319262.9449     626070.7906    4319353.4326
     626046.1843    4319363.7514     625931.0903    4319372.4827
     625805.6775     4319393.914     625794.0678    4319395.3652

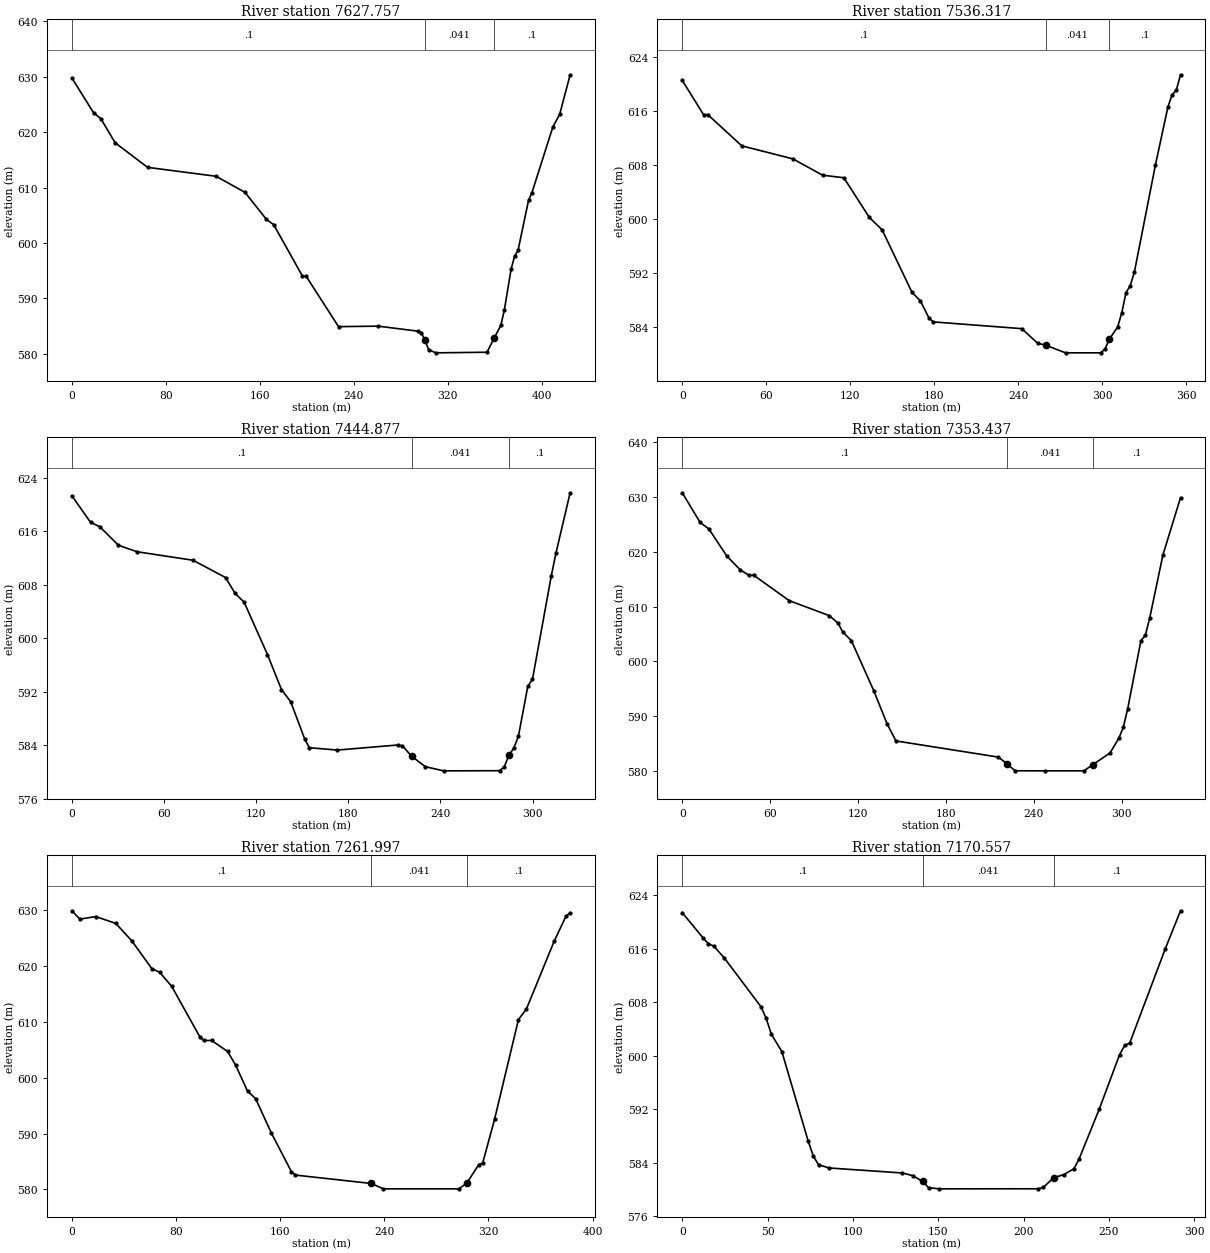
Type RM Length L Ch R = 1 ,7627.757,83.76,91.44,93.08
XS GIS Cut Line= 6
     627040.0021    4319208.5809     627119.6438    4319533.1794
     627119.0667    4319535.6419     627119.9941    4319546.4814
     627118.4743    4319572.8609     627102.7084     4319620.538
#Sta/Elev= 30
       0  629.77   18.41  623.52   24.55  622.46   36.82  618.08   64.43  613.64
  122.73  612.03  147.27  609.15  165.68  604.24  171.82  603.29  196.36  593.99
  199.43  593.99  227.04  584.87  260.79  584.96  294.54  584.06  297.61  583.76
  300.68  582.39  303.74  580.72  309.88  580.14  353.51  580.25  359.38  582.74
  365.25  585.09  368.19   587.8  374.06  595.32  377.01  597.58  379.97  598.69
  388.83  607.67  391.78  609.09  409.51   620.9  415.41  623.25  424.27  630.36
#Mann= 3 , 0 , 0
       0      .1       0  300.68    .041       0  359.38      .1       0
Bank Sta=300.68,359.38
XS Rating Curve= 0 ,0
Exp/Cntr=0.3,0.1

Type RM Length L Ch R = 1 ,7536.317,87.56,91.44,93.3
XS GIS Cut Line= 6
     627030.4771    4319242.7122      627038.647    4319476.3677
     627033.0246    4319510.1022     627029.7899    4319523.9696
     627028.8338     4319534.586     627019.3368    4319596.7212
#Sta/Elev= 30
       0  620.47   15.18   615.4   18.22   615.4   42.51  610.78   78.94  608.86
   100.2  606.44  115.38  606.06   133.6  600.18  142.71  598.35  163.96  589.13
  170.04  587.82  176.11  585.33  179.14  584.73  242.35  583.73  253.75  581.57
  259.45  581.28  273.69  580.15  298.88  580.15  301.88  580.72  304.87  582.17
  310.86  583.97  313.85  586.09  316.84  589.07  319.84  590.08  322.83  592.11
   337.8   607.9  346.77  616.55  349.77  618.35  352.76  619.02  355.75   621.3
#Mann= 3 , 0 , 0
       0      .1       0  259.45    .041       0  304.87      .1       0
Bank Sta=259.45,304.87
XS Rating Curve= 0 ,0
Exp/Cntr=0.3,0.1

Type RM Length L Ch R = 1 ,7444.877,92.74,91.44,90.97
XS GIS Cut Line= 4
     626994.7582    4319250.6497     626958.0415    4319459.7631
     626942.9667    4319498.6571     626925.7012     4319566.964
#Sta/Elev= 30
       0  621.33   12.13  617.36    18.2  616.69   30.33  613.92   42.46  612.95
   78.86  611.68  100.09  609.09  106.16  606.76  112.22  605.38  127.39  597.55
  136.49  592.32  142.55  590.48  151.65  584.89  154.68  583.61  172.88  583.26
  212.31  584.02  215.29  583.89  221.25  582.34  230.19  580.77  242.11  580.15
  278.53  580.17  281.59  580.74  284.66  582.52  287.72  583.52  290.78   585.3
  296.91  592.81  299.97  593.87  312.23  609.36  315.29  612.79  324.48  621.78
#Mann= 3 , 0 , 0
       0      .1       0  221.25    .041       0  284.66      .1       0
Bank Sta=221.25,284.66
XS Rating Curve= 0 ,0
Exp/Cntr=0.3,0.1

Type RM Length L Ch R = 1 ,7353.437,90.5,91.44,92.6
XS GIS Cut Line= 6
     626947.9048    4319230.5414     626872.5099    4319432.8192
     626866.3158    4319445.7611     626854.9595    4319479.1348
     626851.2479    4319493.3825     626833.0384    4319550.6517
#Sta/Elev= 30
       0  630.69   12.16  625.31   18.24  624.09    30.4  619.19   39.53  616.69
   45.61  615.67   48.65  615.72   72.97  611.08  100.33  608.35  106.42  606.98
  109.46  605.43  115.54  603.77  130.74  594.72  139.86  588.67  145.94  585.55
  215.87  582.61  221.61  581.44  227.35  580.12  247.85  580.11  274.31  580.11
   280.2   581.2  292.21  583.37  298.22  586.08  301.23  588.02  304.23  591.43
  313.25  603.79  316.25  604.74  319.26  607.91  328.27  619.37  340.29  629.79
#Mann= 3 , 0 , 0
       0      .1       0  221.61    .041       0   280.2      .1       0
Bank Sta=221.61,280.2
XS Rating Curve= 0 ,0
Exp/Cntr=0.3,0.1

Type RM Length L Ch R = 1 ,7261.997,78.69,91.44,108.96
XS GIS Cut Line= 3
     626894.9881    4319195.6163     626780.9355    4319412.8216
     626736.6732    4319542.8985
#Sta/Elev= 30
       0  629.85    6.13  628.36    18.4  628.81   33.73  627.59      46  624.48
   61.33  619.52   67.47  618.84   76.67  616.34   98.13  607.36   101.2  606.65
  107.33  606.65   119.6  604.68  125.73  602.26  134.93  597.58  141.06  596.27
  153.33  590.04  168.66  583.17  171.73  582.57     230  581.07   239.2  580.11
  297.24  580.11  303.34  581.12   312.5  584.43  315.56  584.72  324.72  592.58
  343.04  610.39  349.14  612.27  370.52  624.43  379.68  628.94  382.73  629.42
#Mann= 3 , 0 , 0
       0      .1       0     230    .041       0  303.34      .1       0
Bank Sta=230,303.34
XS Rating Curve= 0 ,0
Exp/Cntr=0.3,0.1

Type RM Length L Ch R = 1 ,7170.557,77.75,91.44,104.09
XS GIS Cut Line= 5
     626779.7748    4319250.8901     626708.0589    4319383.2088
     626680.1909    4319403.9917      626663.685    4319424.5596
     626620.6488    4319492.3739
#Sta/Elev= 30
       0  621.39   12.29  617.59   15.36  616.75   18.43   616.4   24.57  614.65
   46.07  607.35   49.14  605.62   52.22  603.22   58.36  600.63   73.72   587.3
   76.79  585.01   79.86  583.71      86  583.23     129  582.48  135.15  582.08
  140.88  581.21  144.36  580.29   150.5  580.11  208.71  580.12  211.64  580.34
  217.59  581.77  223.54  582.23  229.49  583.11  232.46  584.53  244.36  592.03
  256.26  600.17  259.24  601.55  262.21  601.91  283.03  615.99  291.96  621.68
#Mann= 3 , 0 , 0
       0      .1       0  140.88    .041       0  217.59      .1       0
Bank Sta=140.88,217.59
XS Rating Curve= 0 ,0
Exp/Cntr=0.3,0.1

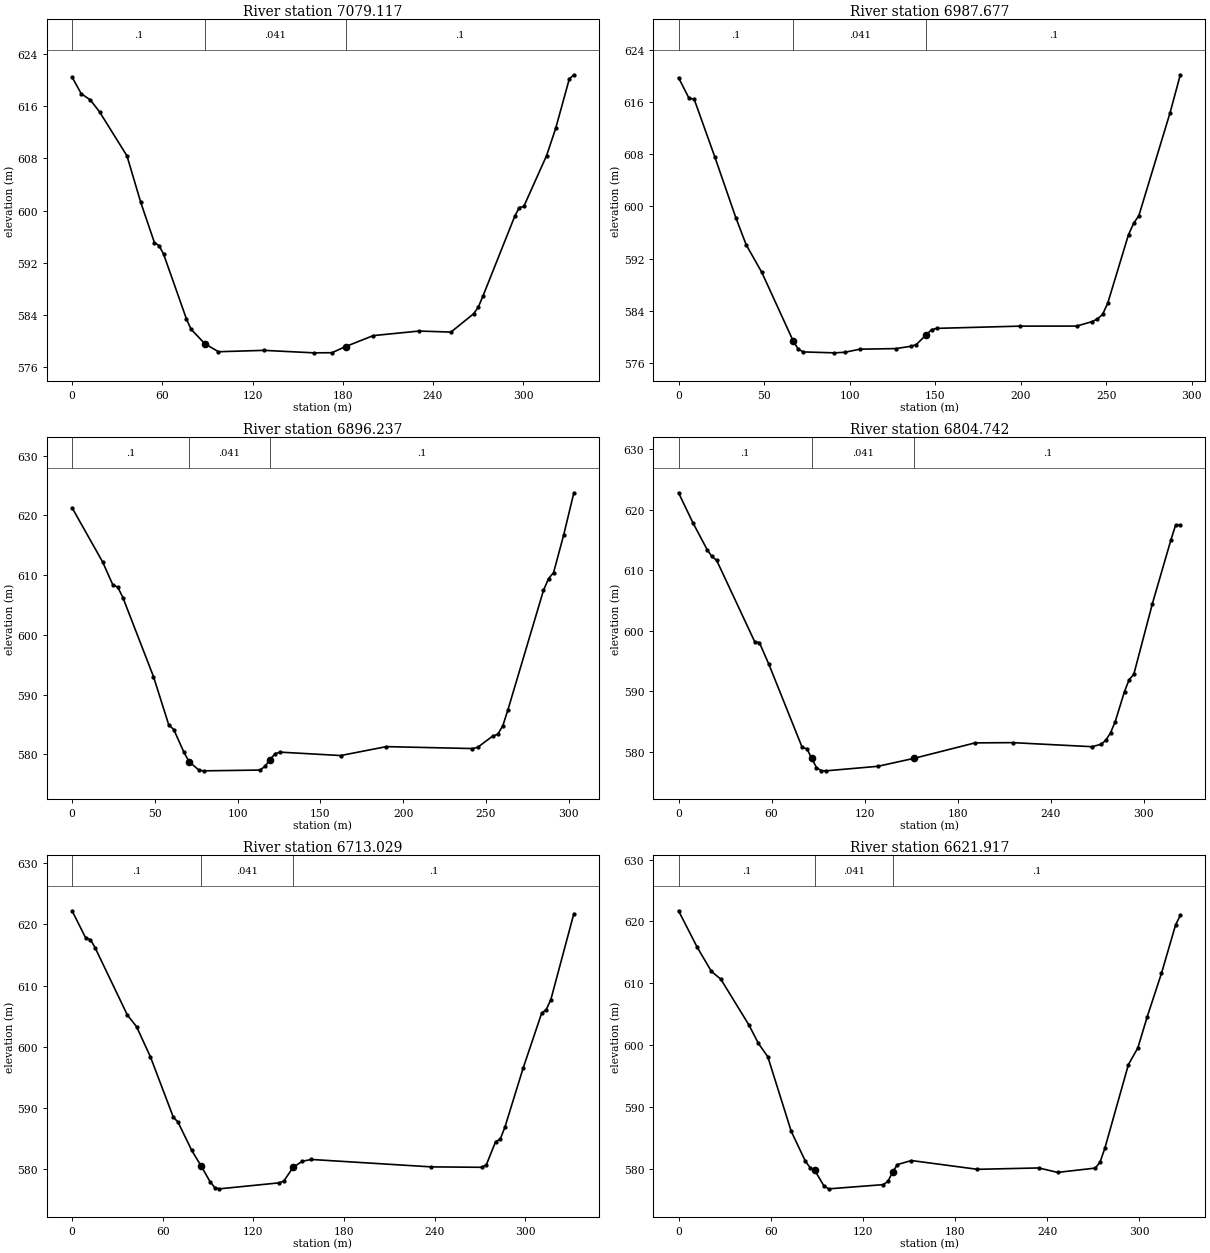
Type RM Length L Ch R = 1 ,7079.117,105.49,91.44,61.84
XS GIS Cut Line= 5
     626729.5213     4319236.427     626658.5202    4319311.6358
      626596.001    4319341.8177     626560.4348     4319391.318
     626518.3854    4319481.9344
#Sta/Elev= 30
       0  620.45    6.08   617.9   12.17  616.94   18.25  615.13    36.5  608.38
   45.63  601.28   54.76  595.08    57.8  594.63   60.84  593.33   76.05  583.39
   79.09  581.82   88.22   579.6   97.34  578.36  127.58  578.57  160.78  578.19
  172.85  578.21     182  579.16  200.28  580.83  230.76  581.53  251.97  581.37
   267.1  584.19  270.13  585.19  273.16  586.84  294.35   599.1  297.38  600.45
   300.4  600.62  315.54   608.4  321.59  612.57  330.68  620.17   333.7   620.8
#Mann= 3 , 0 , 0
       0      .1       0   88.22    .041       0     182      .1       0
Bank Sta=88.22,182
XS Rating Curve= 0 ,0
Exp/Cntr=0.3,0.1

Type RM Length L Ch R = 1 ,6987.677,93.93,91.44,75.04
XS GIS Cut Line= 5
     626601.3175    4319194.3106     626570.8645    4319257.3137
      626552.801     4319298.673     626529.4785    4319321.7325
     626466.3622    4319452.7918
#Sta/Elev= 30
       0  619.71    6.08  616.57    9.13  616.42    21.3   607.5   33.47  598.28
   39.55   594.1   48.68  589.88   66.93  579.43   69.98  578.11   72.99  577.69
   91.04  577.55   97.06  577.63  106.08  578.11  127.04   578.2  135.98  578.56
  138.96  578.81  144.92  580.34  147.91   581.1  150.94   581.3  199.43  581.64
  232.76  581.65  241.85  582.34  244.88  582.74  247.91  583.43  250.94  585.17
  263.07  595.66   266.1  597.39  269.13  598.57  287.31  614.28  293.37  620.15
#Mann= 3 , 0 , 0
       0      .1       0   66.93    .041       0  144.92      .1       0
Bank Sta=66.93,144.92
XS Rating Curve= 0 ,0
Exp/Cntr=0.3,0.1

Type RM Length L Ch R = 1 ,6896.237,100.42,91.5,68.76
XS GIS Cut Line= 5
     626513.9873    4319161.7496     626480.2064    4319230.7387
     626473.3821    4319257.4672     626462.4726    4319285.6719
     626421.6455    4319449.0209
#Sta/Elev= 30
       0  621.28   18.44  612.21   24.58   608.4   27.65  607.97   30.73  606.22
   49.16  593.02   58.38  584.95   61.45  584.14    67.6  580.32   70.67  578.78
   76.82  577.32   79.86  577.25  113.47  577.38   116.5     578  119.52  579.13
  122.55  580.11  125.57  580.38  162.19  579.81  189.75   581.3  241.79  580.98
  244.85  581.17  254.03  583.07   257.1  583.37  260.16  584.83  263.22  587.48
  284.65  607.43  287.71  609.41  290.77  610.42  296.89  616.74  303.02  623.78
#Mann= 3 , 0 , 0
       0      .1       0   70.67    .041       0  119.52      .1       0
Bank Sta=70.67,119.52
XS Rating Curve= 0 ,0
Exp/Cntr=0.3,0.1

Type RM Length L Ch R = 1 ,6804.742,90.15,91.71,99.92
XS GIS Cut Line= 5
     626389.1037    4319119.4161     626385.9392    4319242.0437
     626389.0065    4319280.1156     626389.0065    4319346.7908
     626380.1036     4319442.356
#Sta/Elev= 30
       0  622.81     9.2  617.89    18.4  613.43   21.47  612.28   24.53  611.67
   49.07  598.22   52.13  598.05   58.27  594.45   79.73  580.73    82.8   580.5
   85.87  578.91   88.93  577.41      92  576.89   95.07  576.86  128.54  577.61
  152.05  578.94  191.17  581.48  215.42  581.52  266.53  580.85  272.53  581.25
  275.53  581.93  278.53  583.15  281.53  584.98  287.53  589.97  290.53  591.93
  293.52  592.81  305.52   604.5  317.52  615.08  320.52   617.5  323.52   617.5
#Mann= 3 , 0 , 0
       0      .1       0   85.87    .041       0  152.05      .1       0
Bank Sta=85.87,152.05
XS Rating Curve= 0 ,0
Exp/Cntr=0.3,0.1

Type RM Length L Ch R = 1 ,6713.029,91.33,91.11,80.3
XS GIS Cut Line= 2
     626303.3785    4319113.0661     626277.9785    4319444.3251
#Sta/Elev= 30
       0  622.24    9.14  617.74   12.19  617.52   15.24  616.21   36.58  605.21
   42.67  603.31   51.82   598.4   67.06  588.49    70.1  587.72   79.25  583.06
   85.34  580.58   91.44  577.93   94.49     577   97.54  576.79  137.16  577.77
  140.21  578.07   146.3  580.29   152.4   581.3   158.5  581.59  237.74  580.38
  271.27  580.31  274.32  580.74  280.42  584.51  283.46  584.91  286.51  586.82
   298.7  596.56   310.9  605.49  313.94  606.09  316.99  607.72  332.23  621.77
#Mann= 3 , 0 , 0
       0      .1       0   85.34    .041       0   146.3      .1       0
Bank Sta=85.34,146.3
XS Rating Curve= 0 ,0
Exp/Cntr=0.3,0.1

Type RM Length L Ch R = 1 ,6621.917,138.14,91.44,35.37
XS GIS Cut Line= 5
     626216.6656    4319112.5722     626203.1101    4319209.4839
     626204.2237    4319241.7795     626209.9364    4319265.5775
     626203.9656    4319437.4812
#Sta/Elev= 30
       0  621.73   12.23  615.79   21.41  611.92   27.52  610.66   45.87  603.23
   51.99  600.27    58.1  598.11   73.39  586.02   82.57   581.2   85.62  580.17
   88.68  579.72    94.8  577.14   97.86  576.73  133.23  577.41  136.29  577.93
  139.35  579.42  142.41  580.65  151.58  581.31  194.57  579.89   234.5  580.11
  246.79  579.39  271.36  580.09  274.43  581.08  277.51   583.3  292.86  596.84
  299.01  599.55  305.15  604.62  314.37   611.6  323.58  619.46  326.65     621
#Mann= 3 , 0 , 0
       0      .1       0   88.68    .041       0  139.35      .1       0
Bank Sta=88.68,139.35
XS Rating Curve= 0 ,0
Exp/Cntr=0.3,0.1

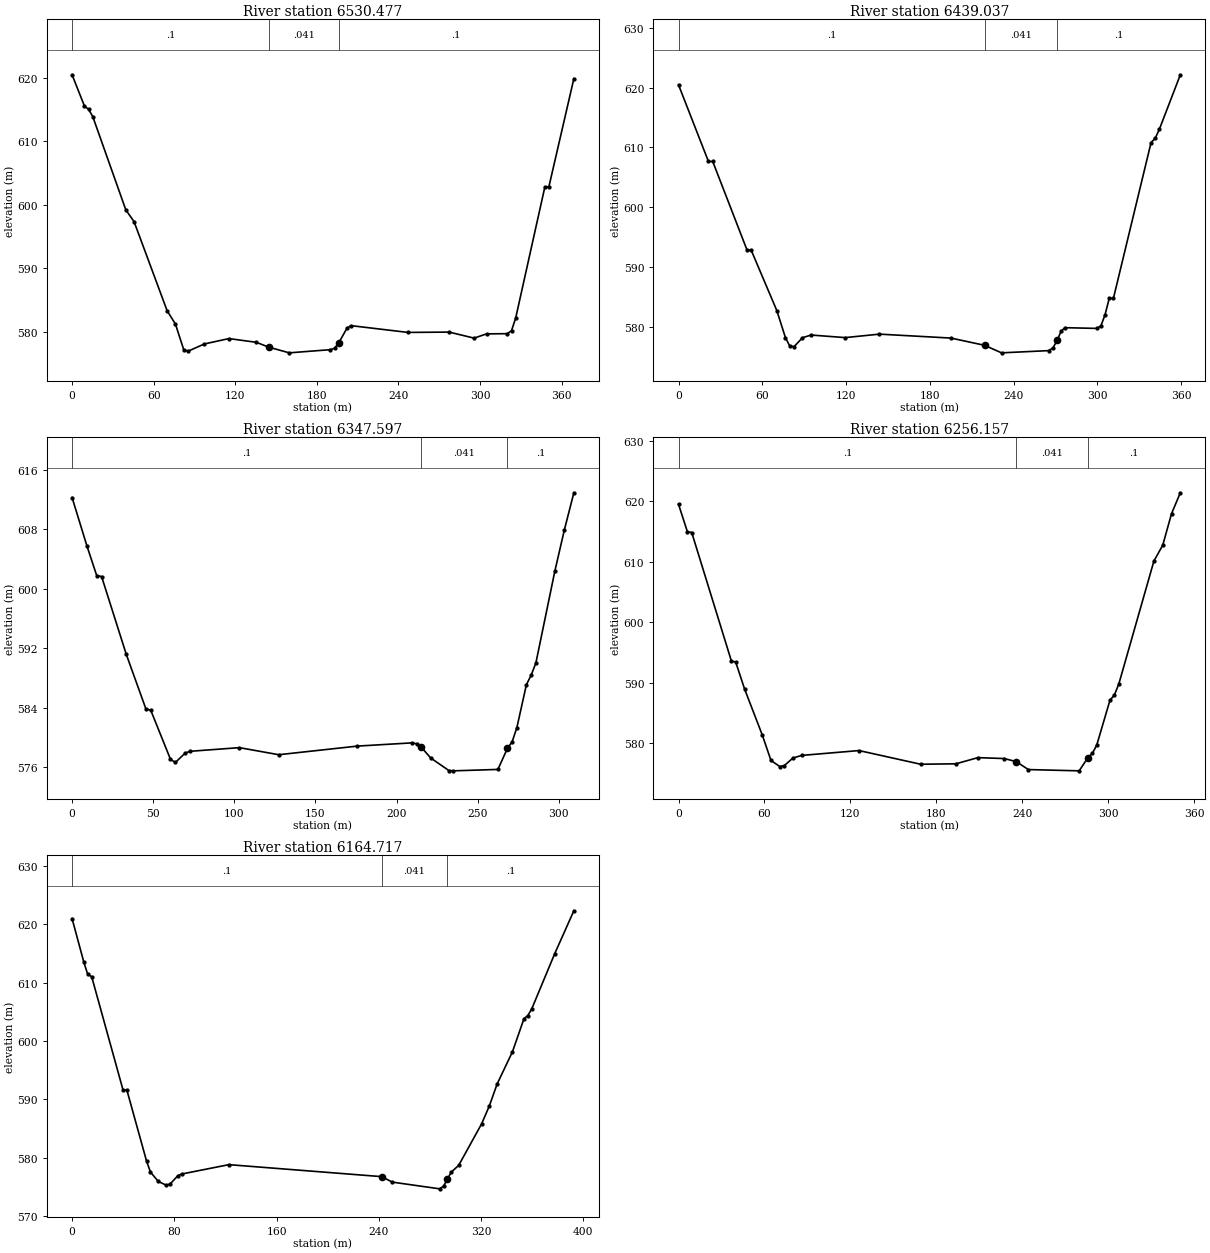
Type RM Length L Ch R = 1 ,6530.477,63.18,91.44,93.51
XS GIS Cut Line= 6
      626072.732    4319112.5722     626078.0238    4319224.9574
     626091.1127    4319240.0636     626163.8407    4319289.1868
     626186.2561    4319316.9509     626185.9739    4319430.0729
#Sta/Elev= 30
       0  620.48    9.12  615.54   12.16  615.03    15.2   613.9   39.53  599.18
   45.61  597.32   69.94  583.26   76.02  581.18    82.1  577.15   85.14  576.88
   97.31  578.04  115.37  578.89  135.52   578.3   144.6  577.54  159.73  576.64
     190  577.14  193.02  577.35  196.05  578.18   202.1  580.49  205.13  580.93
  247.02  579.86  277.35  579.91  295.69  578.96  304.86  579.63  320.15  579.66
  323.21  580.13  326.26  582.11  347.67  602.73  350.72  602.84  369.07  619.87
#Mann= 3 , 0 , 0
       0      .1       0   144.6    .041       0  196.05      .1       0
Bank Sta=144.6,196.05
XS Rating Curve= 0 ,0
Exp/Cntr=0.3,0.1

Type RM Length L Ch R = 1 ,6439.037,56.34,91.44,109.2
XS GIS Cut Line= 6
     626020.8735    4319110.4556     626028.9831    4319263.3065
     626043.5352    4319282.4888     626058.2479    4319328.2096
     626108.3582    4319369.1401     626111.0041    4319437.9319
#Sta/Elev= 30
       0  620.45   21.43  607.63   24.49  607.63   48.98  592.85   52.04  592.78
   70.41  582.66   76.53  578.16   79.59  576.76   82.66  576.62   88.78  578.13
    94.9  578.58  119.39  578.15  143.88  578.73  195.15  578.07  219.17  576.86
  231.31   575.6  265.09  575.97  268.16  576.43  271.23  577.72  273.98  579.22
  276.74  579.81   299.5  579.69   302.5  580.11  305.49  582.01  308.48  584.74
  311.47  584.74  338.41  610.79  341.41  611.52   344.4  613.05  359.37  622.14
#Mann= 3 , 0 , 0
       0      .1       0  219.17    .041       0  271.23      .1       0
Bank Sta=219.17,271.23
XS Rating Curve= 0 ,0
Exp/Cntr=0.3,0.1

Type RM Length L Ch R = 1 ,6347.597,91.45,91.44,90.09
XS GIS Cut Line= 5
     625966.8984    4319123.1556     625989.6924    4319337.3194
     625994.8211    4319359.2603     625996.0186    4319375.0445
     626002.8208    4319430.2109
#Sta/Elev= 30
       0  612.25     9.1  605.78   15.17  601.76    18.2  601.62   33.37  591.18
    45.5  583.82   48.53  583.62   60.67  577.03    63.7  576.61   69.77  577.88
    72.8  578.11  103.14   578.6   127.4  577.65  175.94  578.81  209.31  579.24
  212.34  579.13  215.37  578.64  221.01  577.22  232.27  575.52  235.09  575.48
  262.51  575.67  268.36   578.5  271.29   579.4  274.21  581.31  280.06  587.07
  282.99  588.35  285.92     590  297.62  602.37  303.47   607.9  309.32  612.89
#Mann= 3 , 0 , 0
       0      .1       0  215.37    .041       0  268.36      .1       0
Bank Sta=215.37,268.36
XS Rating Curve= 0 ,0
Exp/Cntr=0.3,0.1

Type RM Length L Ch R = 1 ,6256.157,101.21,91.44,91.44
XS GIS Cut Line= 4
     625862.1232    4319116.8056     625902.1923    4319340.6267
     625903.6197    4319371.3751     625919.1324    4319462.1533
#Sta/Elev= 30
       0  619.48    6.15  614.98    9.22  614.82   36.87  593.62   39.95   593.4
   46.09  588.98   58.38  581.43   64.53  577.17   70.67  576.17   73.74  576.31
   79.89  577.58   86.04  578.01  125.98  578.81     169  576.55  193.58  576.62
  208.94  577.64  227.38  577.49  235.77  576.98  244.17  575.67  279.65  575.46
  285.79  577.65  288.86  578.34  291.93  579.72  301.14  587.12  304.21  587.97
  307.28  589.77  331.84  610.13  337.98  612.72  344.12  617.94  350.26  621.39
#Mann= 3 , 0 , 0
       0      .1       0  235.77    .041       0  285.79      .1       0
Bank Sta=235.77,285.79
XS Rating Curve= 0 ,0
Exp/Cntr=0.3,0.1

Type RM Length L Ch R = 1 ,6164.717,84.38,91.44,73.81
XS GIS Cut Line= 6
     625762.6397    4319126.3306     625792.7339    4319310.9316
     625805.6985    4319370.1984     625812.0181    4319378.1863
     625818.9711    4319418.8744      625892.815    4319475.5813
#Sta/Elev= 30
       0  620.95     9.2   613.5   12.26  611.39   15.33  611.02   39.86  591.62
   42.93  591.56   58.26  579.45   61.32  577.56   67.46  575.96   73.59  575.32
   76.65  575.51   82.79  576.94   85.85  577.23  122.65  578.83  242.12  576.78
  250.54  575.84  287.61  574.69  290.61  575.16  293.56  576.32  296.51  577.52
  302.46  578.71  320.48  585.85  326.49  588.91  332.49  592.62  344.51  598.15
  353.52  603.81  356.52  604.36  359.52  605.45  377.55  614.93  392.56  622.29
#Mann= 3 , 0 , 0
       0      .1       0  242.12    .041       0  293.56      .1       0
Bank Sta=242.12,293.56
XS Rating Curve= 0 ,0
Exp/Cntr=0.3,0.1

River Reach=Mill Run (Dry)  ,1
Reach XY= 30
       626346.77    4321823.8727     626348.7544    4321669.8849
     626335.6575    4321629.0067     626312.6387    4321597.6535
     626155.5219    4321510.3533     626113.5787    4321397.8448
     625967.7536    4321357.1468     625913.7785    4321242.4497
     625888.8931    4321150.8464      625812.972     4321030.518
     625795.5095    4320849.9395     625845.9127    4320783.2644
     625807.5817    4320701.3284      625755.425     4320656.661
     625716.5312     4320538.392     625727.2469    4320485.2107
     625780.7059    4320415.4905     625824.5847    4320240.8307
     625858.7024    4320204.3364     625871.9594    4320098.3365
     625857.0252    4320047.0598     625765.7438     4319947.444
     625757.8063    4319901.4064     625776.0626    4319827.1906
      625769.706    4319777.8237     625706.2124    4319735.9092
     625678.4311    4319691.0622     625711.7687    4319579.5401
     625791.9376    4319525.1681     625794.0678    4319395.3652

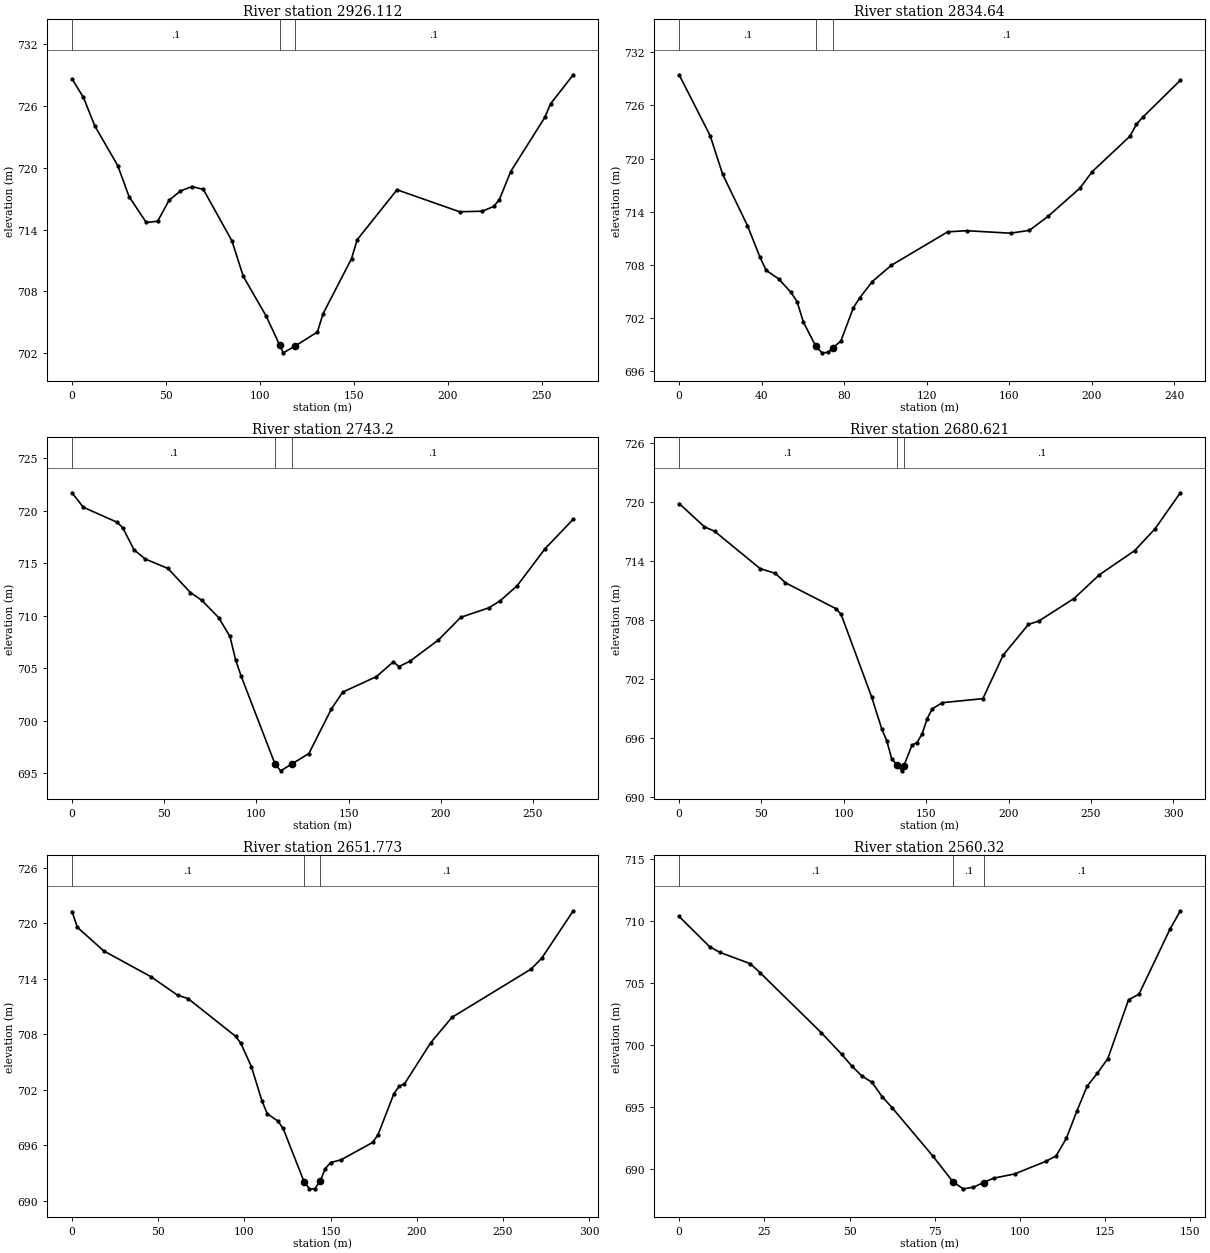
Type RM Length L Ch R = 1 ,2926.112,93.66,91.47,95.5
XS GIS Cut Line= 3
     626459.1832    4321807.0414     626337.6968    4321806.6101
      626193.541    4321789.0497
#Sta/Elev= 30
       0  728.61    6.07  726.81   12.15  724.04    24.3  720.21   30.37  717.19
   39.48  714.69   45.56  714.81   51.63  716.84   57.71  717.75   63.78  718.17
   69.86   717.9   85.04  712.92   91.12  709.47  103.26  705.63  110.41  702.83
  112.38  702.05  118.45  702.68  130.56  704.07  133.59  705.85  148.72  711.18
  151.74  713.02  172.92  717.86   206.2  715.73   218.3  715.78  224.35  716.24
  227.38   716.9  233.43  719.63  251.58  724.88  254.61  726.19  266.71  729.01
#Mann= 3 , 0 , 0
       0      .1       0  110.41      .1       0  118.45      .1       0
Bank Sta=110.41,118.45
XS Rating Curve= 0 ,0
Exp/Cntr=0.3,0.1

Type RM Length L Ch R = 1 ,2834.64 ,93.78,91.44,91.24
XS GIS Cut Line= 4
     626418.9664    4321702.2662     626351.0668    4321715.7484
     626302.5483    4321720.2451      626190.366    4321775.2913
#Sta/Elev= 30
       0  729.44   15.05  722.57   21.07  718.23   33.11  712.44   39.13   708.9
   42.14   707.4   48.16  706.44   54.18  704.92   57.19  703.85    60.2  701.57
   66.22  698.84   69.23  698.09   72.27  698.14   74.56  698.68   78.36  699.41
   84.45  703.18    87.5  704.28   93.59  706.12  102.72  707.94  130.14  711.73
  139.29  711.86  160.62  711.58  169.76   711.9  178.91   713.5  194.15  716.64
  200.24  718.53  218.53  722.52  221.58  723.84  224.62  724.64  242.91  728.82
#Mann= 3 , 0 , 0
       0      .1       0   66.22      .1       0   74.56      .1       0
Bank Sta=66.22,74.56
XS Rating Curve= 0 ,0
Exp/Cntr=0.3,0.1

Type RM Length L Ch R = 1 ,2743.2  ,64.93,62.58,60.22
XS GIS Cut Line= 3
     626422.5605     4321562.331     626299.3095    4321652.8191
     626219.9994    4321741.4246
#Sta/Elev= 30
       0   721.7    6.12  720.32   24.46  718.89   27.52  718.36   33.64  716.26
   39.75  715.39   51.99  714.49   64.22  712.19   70.33  711.46   79.51  709.81
   85.62  708.02   88.68   705.8   91.74  704.22  110.09  695.85  113.15  695.21
  119.26  695.87  128.44  696.86  140.67  701.11  146.79  702.71   165.1  704.19
  174.25   705.6  177.29  705.14  183.39  705.67  198.64  707.67  210.84  709.84
  226.08  710.74  232.18  711.41  241.33  712.83  256.57  716.38  271.82  719.18
#Mann= 3 , 0 , 0
       0      .1       0  110.09      .1       0  119.26      .1       0
Bank Sta=110.09,119.26
XS Rating Curve= 0 ,0
Exp/Cntr=0.3,0.1

Type RM Length L Ch R = 1 ,2680.621,28.75,28.85,28.95
XS GIS Cut Line= 2
      626351.233     4321465.199      626212.591    4321736.1329
#Sta/Elev= 30
       0  719.81   15.37  717.44   21.52  716.99   49.19  713.19   58.41  712.71
   64.56  711.75    95.3  709.11   98.37  708.53  116.82  700.18  122.97  696.93
  126.04   695.7  129.12  693.84  132.19  693.27  135.27  692.63  136.52  693.17
  141.41  695.24  144.49  695.51  147.56  696.39  150.64  697.95  153.71  698.94
  159.86  699.56  184.45  699.97  196.75  704.39  212.12  707.52  218.27  707.85
  239.79  710.15  255.16  712.56  276.68  715.03  288.98  717.24  304.35   720.9
#Mann= 3 , 0 , 0
       0      .1       0  132.19      .1       0  136.52      .1       0
Bank Sta=132.19,136.52
XS Rating Curve= 0 ,0
Exp/Cntr=0.3,0.1

Type RM Length L Ch R = 1 ,2651.773,91.87,91.45,91.95
XS GIS Cut Line= 2
     626330.0662     4321449.324     626192.4826    4321705.4412
#Sta/Elev= 30
       0  721.26    3.06  719.56   18.36  717.01   45.91   714.2   61.21  712.22
   67.33  711.85   94.87  707.78   97.93  707.02  104.05  704.48  110.17   700.8
  113.23  699.41  119.35  698.63  122.41  697.84  134.65  692.04  137.72   691.3
  140.78   691.3  143.84  692.11   146.9  693.49  149.96  694.14  156.08  694.44
  174.44  696.32   177.5  697.16  186.68  701.57  189.74   702.4   192.8  702.63
   208.1   707.1  220.34  709.82  266.25  715.04  272.37   716.2  290.73  721.34
#Mann= 3 , 0 , 0
       0      .1       0  134.65      .1       0  143.84      .1       0
Bank Sta=134.65,143.84
XS Rating Curve= 0 ,0
Exp/Cntr=0.3,0.1

Type RM Length L Ch R = 1 ,2560.32 ,87.18,91.44,98.75
XS GIS Cut Line= 4
     626233.7577    4321454.6157     626182.6824    4321531.5282
     626179.5538    4321540.1466     626158.4375    4321580.5597
#Sta/Elev= 30
       0  710.39    8.93  707.96   11.91   707.5   20.85  706.59   23.83  705.84
    41.7  701.03   47.65   699.3   50.63  698.35   53.61  697.54   56.59  697.03
   59.57  695.87   62.54  694.97   74.46  691.08   80.41  688.99   83.39  688.44
   86.37  688.57   89.35  688.95   92.33   689.3   98.44  689.64  107.58  690.65
  110.61  691.09  113.65  692.52  116.69  694.69  119.73  696.71  122.77  697.77
  125.81  698.94  131.89  703.68  134.93  704.12  144.05  709.37  147.09  710.85
#Mann= 3 , 0 , 0
       0      .1       0   80.41      .1       0   89.35      .1       0
Bank Sta=80.41,89.35
XS Rating Curve= 0 ,0
Exp/Cntr=0.3,0.1

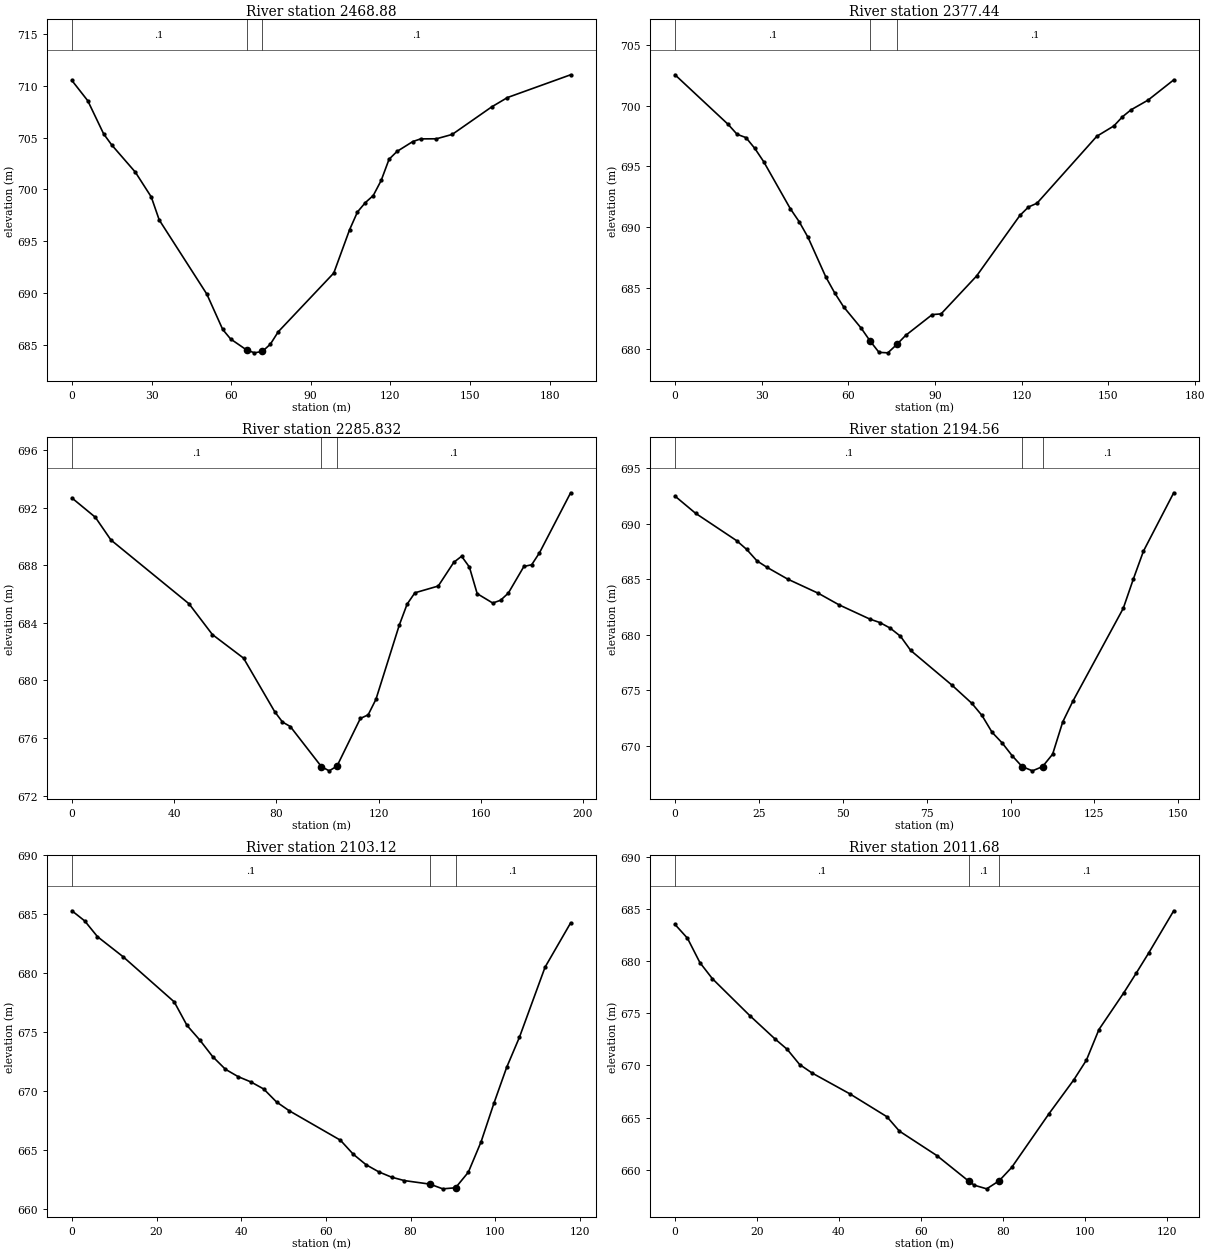
Type RM Length L Ch R = 1 ,2468.88 ,96.61,91.44,86.27
XS GIS Cut Line= 3
     626197.6007      4321439.27     626106.6529    4321469.1136
     626043.2573    4321536.1075
#Sta/Elev= 30
       0  710.49    5.98  708.54   11.96  705.35   14.96   704.3   23.93  701.66
   29.91  699.28    32.9  697.07   50.85  689.93   56.83  686.53   59.82  685.61
   65.81  684.56    68.8  684.28   71.79  684.42   74.78  685.11   77.77  686.31
   98.69  691.96  104.65  696.13  107.62  697.84   110.6  698.74  113.57  699.42
  116.55  700.87  119.52  702.91   122.5  703.66  128.45  704.61  131.42  704.87
  137.37  704.88  143.32   705.3   158.2  707.95  164.15  708.85  187.95  711.04
#Mann= 3 , 0 , 0
       0      .1       0   65.81      .1       0   71.79      .1       0
Bank Sta=65.81,71.79
XS Rating Curve= 0 ,0
Exp/Cntr=0.3,0.1

Type RM Length L Ch R = 1 ,2377.44 ,91.53,91.61,91.69
XS GIS Cut Line= 3
     626111.0501    4321311.8966     626082.7714    4321418.7264
     626053.8407    4321473.6657
#Sta/Elev= 30
       0  702.53   18.42  698.45   21.49  697.64   24.56  697.37   27.63  696.48
    30.7  695.39   39.91  691.53   42.98  690.46   46.05  689.17   52.18  685.93
   55.25  684.62   58.32  683.48   64.46  681.71   67.53  680.66    70.6  679.73
   73.67  679.69   76.77  680.38   79.81  681.12   89.02  682.83   92.09  682.89
  104.37     686  119.38  690.98  122.34  691.67  125.29  691.98  145.99  697.48
   151.9  698.33  154.86  699.08  157.82  699.65  163.73  700.45   172.6  702.11
#Mann= 3 , 0 , 0
       0      .1       0   67.53      .1       0   76.77      .1       0
Bank Sta=67.53,76.77
XS Rating Curve= 0 ,0
Exp/Cntr=0.3,0.1

Type RM Length L Ch R = 1 ,2285.832,85.69,91.27,96.85
XS GIS Cut Line= 3
      626052.888    4321282.4933     626012.9915    4321328.7375
     625976.5822    4321457.7907
#Sta/Elev= 30
       0  692.68    9.16  691.34   15.27  689.76   45.81  685.33   54.97  683.19
   67.17  681.55   79.36  677.83   82.41  677.11   85.46   676.8   97.65  674.01
  100.69  673.72  103.74  674.05  112.88  677.36  115.93  677.61  118.98  678.69
  128.12  683.85  131.17   685.3  134.22  686.09  143.36  686.56  149.45  688.21
   152.5  688.63  155.55  687.88   158.6  686.03  164.69  685.38  167.74  685.57
  170.79  686.07  176.88  687.92  179.93  688.04  182.98  688.87  195.17  693.04
#Mann= 3 , 0 , 0
       0      .1       0   97.65      .1       0  103.74      .1       0
Bank Sta=97.65,103.74
XS Rating Curve= 0 ,0
Exp/Cntr=0.3,0.1

Type RM Length L Ch R = 1 ,2194.56 ,90.49,91.44,92.39
XS GIS Cut Line= 3
     626046.3441    4321266.0556     625971.2641     4321300.187
     625906.8257    4321315.2134
#Sta/Elev= 30
       0  692.48    6.11  690.94   18.33  688.48   21.38  687.68   24.44  686.65
   27.49  686.06    33.6  685.01   42.76  683.73   48.87   682.7   58.04  681.42
   61.09   681.1   64.15   680.6    67.2  679.87   70.26  678.59   82.47  675.49
   88.49  673.83    91.5  672.74    94.5  671.23   97.51  670.27  100.52  669.11
  103.43  668.15  106.53  667.76  109.54  668.14  112.55  669.26  115.56  672.16
  118.57  674.02   133.6  682.38  136.61  685.02  139.62  687.53  148.64  692.78
#Mann= 3 , 0 , 0
       0      .1       0  103.43      .1       0  109.54      .1       0
Bank Sta=103.43,109.54
XS Rating Curve= 0 ,0
Exp/Cntr=0.3,0.1

Type RM Length L Ch R = 1 ,2103.12 ,93.54,91.44,89.34
XS GIS Cut Line= 2
     625996.6481    4321219.3295     625878.9927    4321225.3119
#Sta/Elev= 30
       0   685.3    3.02  684.44    6.04   683.1   12.08   681.4   24.17  677.56
   27.19  675.56   30.21  674.32   33.23  672.92   36.25  671.84   39.27  671.21
   42.29  670.76   45.31  670.16   48.33  669.06   51.35  668.31   63.43  665.81
   66.46  664.62   69.48  663.73    72.5  663.12   75.52  662.67   78.54  662.38
   84.58  662.08    87.6  661.68   90.62  661.77   93.64  663.09   96.66  665.68
   99.68  668.94   102.7     672  105.72  674.56  111.77  680.51  117.81  684.27
#Mann= 3 , 0 , 0
       0      .1       0   84.58      .1       0   90.62      .1       0
Bank Sta=84.58,90.62
XS Rating Curve= 0 ,0
Exp/Cntr=0.3,0.1

Type RM Length L Ch R = 1 ,2011.68 ,91.04,91.28,91.47
XS GIS Cut Line= 2
     625947.8429    4321105.0183     625839.2363     4321159.829
#Sta/Elev= 26
       0  683.51    3.04  682.19    6.08  679.85    9.12  678.31   18.25  674.77
   24.33  672.56   27.37  671.54   30.41  670.08   33.45  669.27   42.58  667.29
    51.7  665.08   54.74   663.7   63.87  661.36   71.67   658.9   72.99  658.52
   76.03  658.17   79.07  658.94   82.12  660.22   91.24  665.38   97.32  668.64
  100.36  670.51  103.41  673.44  109.49  676.97  112.53  678.86  115.57  680.79
  121.65  684.82
#Mann= 3 , 0 , 0
       0      .1       0   71.67      .1       0   79.07      .1       0
Bank Sta=71.67,79.07
XS Rating Curve= 0 ,0
Exp/Cntr=0.3,0.1

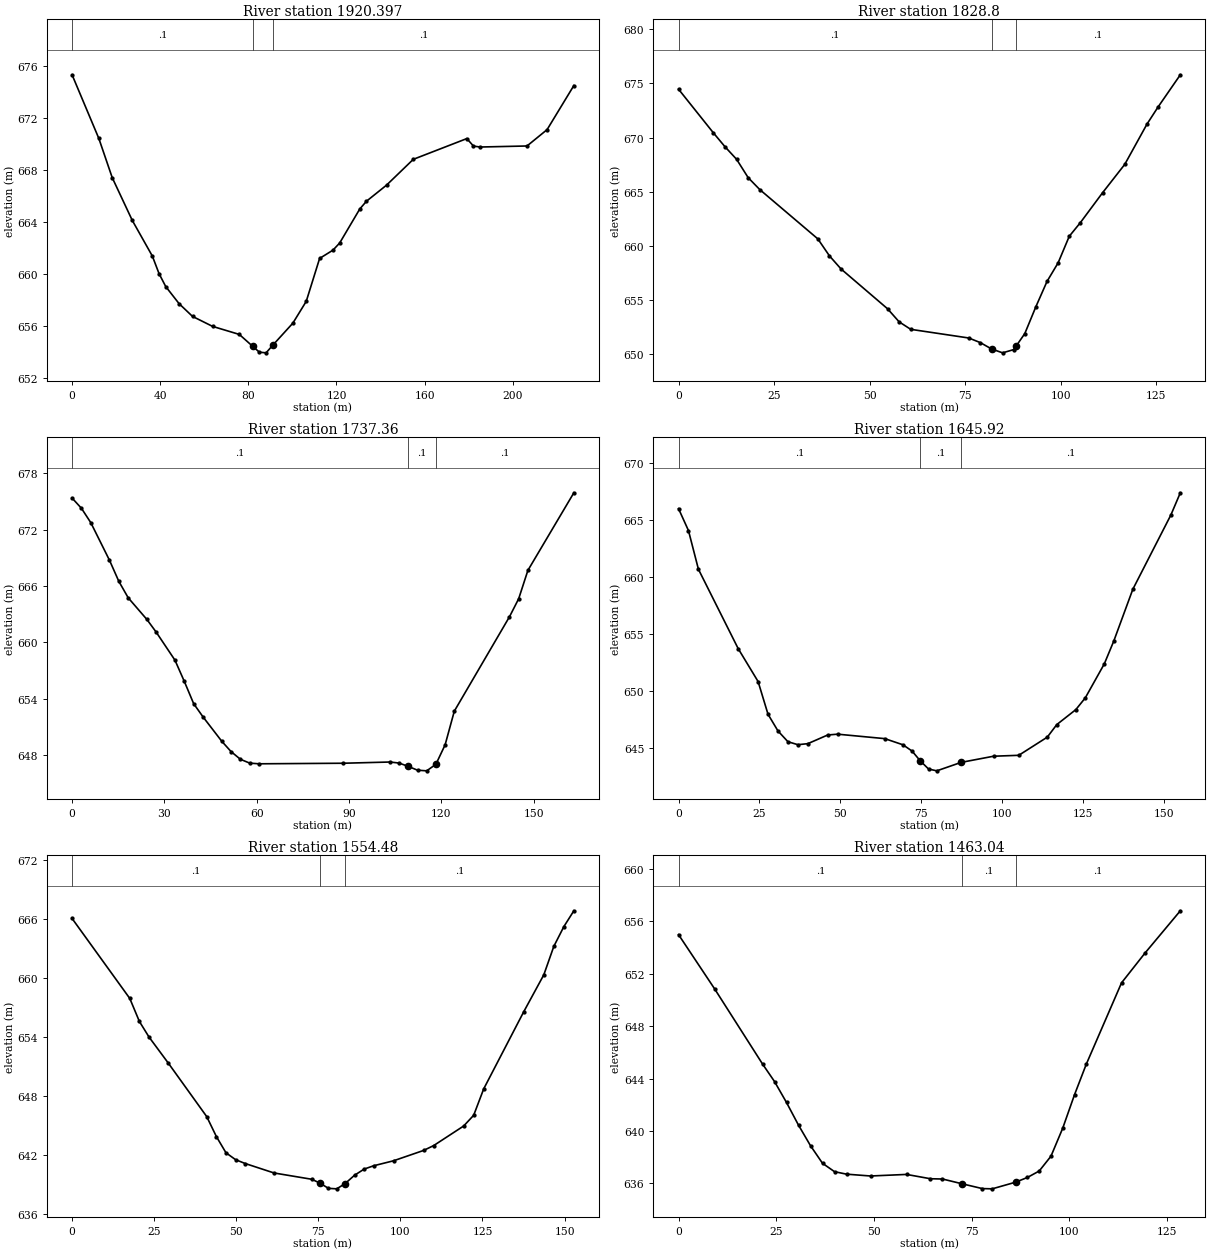
Type RM Length L Ch R = 1 ,1920.397,90.57,91.6,93.33
XS GIS Cut Line= 2
     625904.7585    4321030.5479     625698.1518    4321126.3553
#Sta/Elev= 30
       0  675.36   12.15  670.45   18.22  667.43   27.33  664.13   36.44  661.38
   39.47  660.03   42.51  659.03   48.58  657.71   54.66  656.73   63.77  655.96
   75.91  655.34   81.99  654.42   85.02  653.97   88.06  653.92    91.1  654.51
  100.21  656.21  106.28  657.89  112.35   661.2  118.42  661.84  121.46  662.39
  130.57  665.01  133.61  665.61  142.72  666.85  154.86  668.84  179.16  670.44
  182.19  669.86  185.23  669.79  206.48  669.87  215.59  671.13  227.74  674.53
#Mann= 3 , 0 , 0
       0      .1       0   81.99      .1       0    91.1      .1       0
Bank Sta=81.99,91.1
XS Rating Curve= 0 ,0
Exp/Cntr=0.3,0.1

Type RM Length L Ch R = 1 ,1828.8  ,94.61,91.44,96.17
XS GIS Cut Line= 3
     625896.0605    4320972.8967     625817.1658    4320977.1079
     625765.0533    4320981.7746
#Sta/Elev= 29
       0  674.47    9.12  670.44   12.15  669.16   15.19     668   18.23   666.3
   21.27   665.2   36.46  660.65    39.5  659.08   42.54  657.87    54.7   654.2
   57.74  652.99   60.77   652.3   75.97   651.5   79.01  651.07   81.91  650.49
   84.82  650.13   87.73  650.43   88.37  650.76   90.63  651.91   93.54   654.4
   96.45  656.73   99.35  658.44  102.26  660.89  105.17  662.15  110.98  664.91
  116.79  667.53  122.61  671.25  125.51  672.83  131.33   675.8
#Mann= 3 , 0 , 0
       0      .1       0   81.91      .1       0   88.37      .1       0
Bank Sta=81.91,88.37
XS Rating Curve= 0 ,0
Exp/Cntr=0.3,0.1

Type RM Length L Ch R = 1 ,1737.36 ,68.82,91.44,101.19
XS GIS Cut Line= 3
     625905.9559    4320874.4009     625806.0654    4320883.5296
      625749.929    4320911.5977
#Sta/Elev= 30
       0  675.38    3.04  674.29    6.08  672.76   12.16  668.75    15.2   666.5
   18.24  664.75   24.32  662.44   27.36  661.08   33.44   658.1   36.48  655.84
   39.51  653.47   42.55  652.06   48.63  649.47   51.67  648.36   54.71  647.54
   57.75  647.13   60.79  647.06   88.15  647.12   103.3  647.25  106.28  647.14
  109.27  646.78  112.26  646.38  115.25  646.31  118.24  647.01  121.23  649.08
  124.22  652.67  142.15  662.73  145.14  664.65  148.13  667.67  163.07  675.94
#Mann= 3 , 0 , 0
       0      .1       0  109.27      .1       0  118.24      .1       0
Bank Sta=109.27,118.24
XS Rating Curve= 0 ,0
Exp/Cntr=0.3,0.1

Type RM Length L Ch R = 1 ,1645.92 ,112.23,91.44,66.46
XS GIS Cut Line= 6
     625901.4449    4320828.6076     625846.2436    4320824.8801
     625832.0503     4320815.792     625820.3143    4320800.0092
     625809.5246    4320792.7921     625759.7246    4320789.1613
#Sta/Elev= 30
       0     666    3.07  664.08    6.15  660.69   18.44  653.74   24.59  650.86
   27.66  647.99   30.74  646.53   33.81  645.59   36.88  645.33   39.96  645.42
   46.11  646.18   49.18  646.25   63.75  645.86   69.37  645.32   72.18  644.77
   74.72  643.91   77.27   643.2   79.81  643.04   87.33  643.78   97.36  644.32
  105.15   644.4  113.96  645.99   116.9  647.09  122.78   648.4  125.71  649.43
  131.59  652.41  134.52  654.41   140.4  658.94  152.15  665.44  155.08  667.39
#Mann= 3 , 0 , 0
       0      .1       0   74.72      .1       0   87.33      .1       0
Bank Sta=74.72,87.33
XS Rating Curve= 0 ,0
Exp/Cntr=0.3,0.1

Type RM Length L Ch R = 1 ,1554.48 ,94.84,91.44,93.94
XS GIS Cut Line= 6
     625889.8258     4320688.102     625835.3427    4320716.6918
     625831.5327    4320723.6768     625830.5869    4320727.0905
     625821.6699    4320731.8775     625755.2796    4320753.0456
#Sta/Elev= 30
       0  666.05   17.58  657.93   20.51  655.59   23.44  654.01    29.3  651.37
   41.02  645.93   43.95  643.91   46.88  642.26   49.81  641.56   52.74  641.17
   61.53  640.21   73.03  639.57   75.56  639.17   78.09  638.65   80.62   638.6
   83.15  639.13   86.04  639.98   88.94   640.6   91.83  640.94   97.93  641.45
  107.08   642.5  110.13  642.99  119.28  644.98  122.33  646.07  125.38  648.75
  137.59  656.59  143.69  660.33  146.74  663.22  149.79  665.22  152.84  666.83
#Mann= 3 , 0 , 0
       0      .1       0   75.56      .1       0   83.15      .1       0
Bank Sta=75.56,83.15
XS Rating Curve= 0 ,0
Exp/Cntr=0.3,0.1

Type RM Length L Ch R = 1 ,1463.04 ,78.63,91.44,94.64
XS GIS Cut Line= 4
     625818.0632    4320612.1547     625769.6738    4320659.2499
     625759.8403    4320667.2955     625714.6618    4320683.9005
#Sta/Elev= 27
       0  654.98    9.21  650.85   21.48  645.11   24.55  643.77   27.62  642.17
   30.69  640.44   33.76  638.87   36.83  637.53    39.9  636.89   42.97   636.7
   49.11  636.56   58.32  636.68   64.45  636.35   67.52  636.33   72.61  635.96
   77.69   635.6   80.23  635.58   86.25  636.09   89.25  636.45   92.26  636.94
   95.27  638.07   98.28  640.21  101.29  642.76   104.3  645.09  113.32   651.3
  119.34  653.58  128.36   656.8
#Mann= 3 , 0 , 0
       0      .1       0   72.61      .1       0   86.25      .1       0
Bank Sta=72.61,86.25
XS Rating Curve= 0 ,0
Exp/Cntr=0.3,0.1