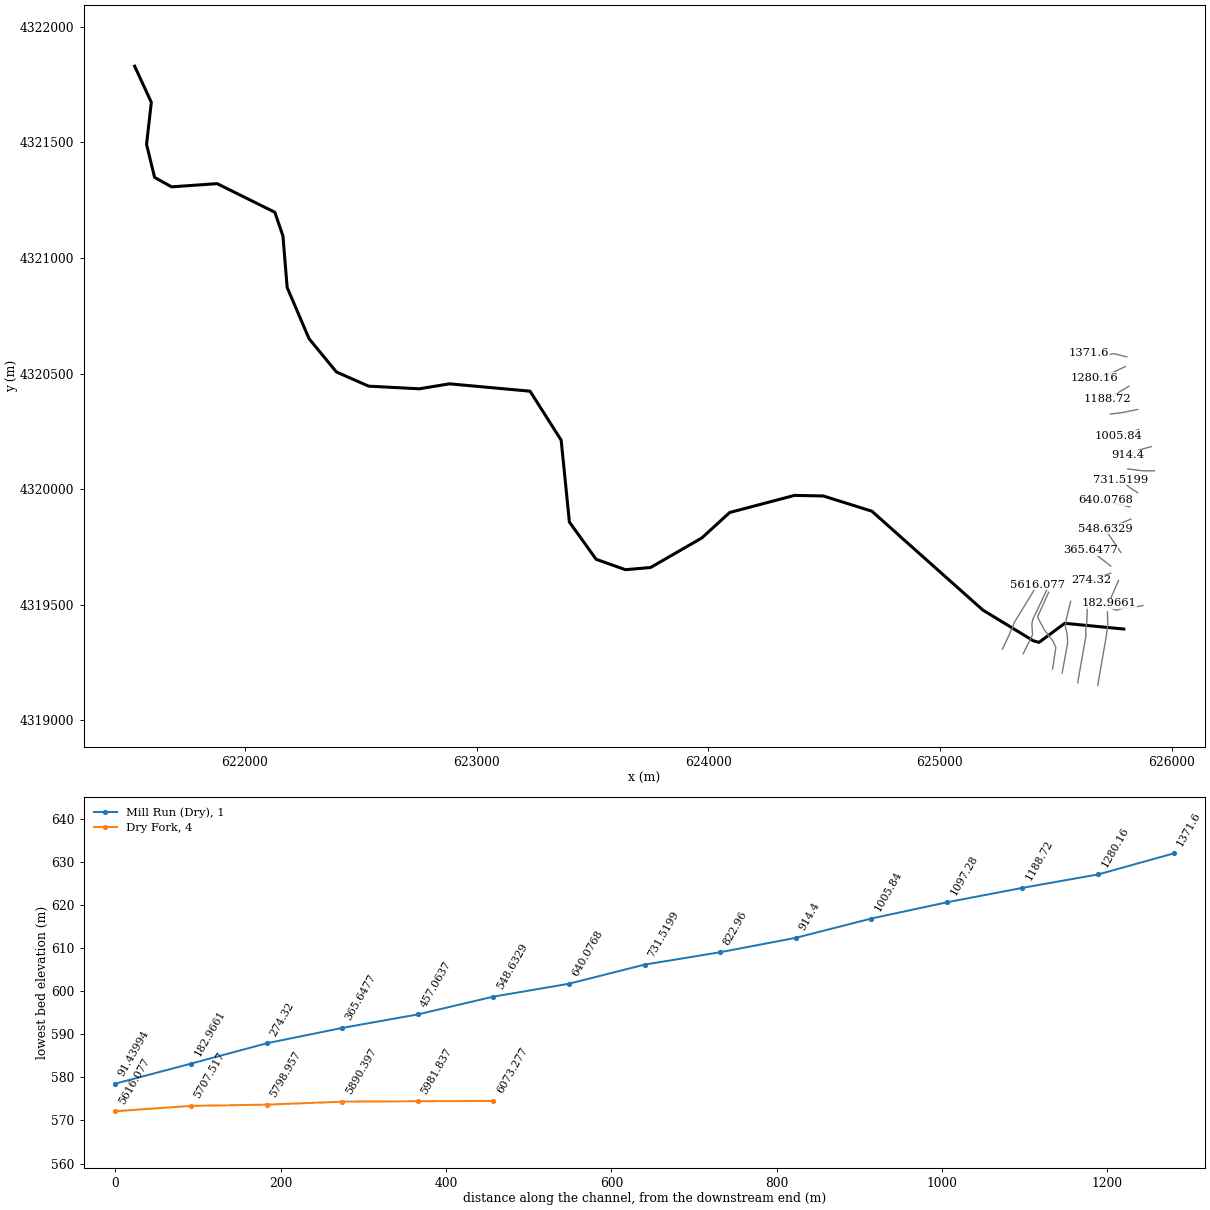
HEC-RAS study RedCreek.prj: RedCreek

--- RedCreek.g01 (geometry) --- (continued)

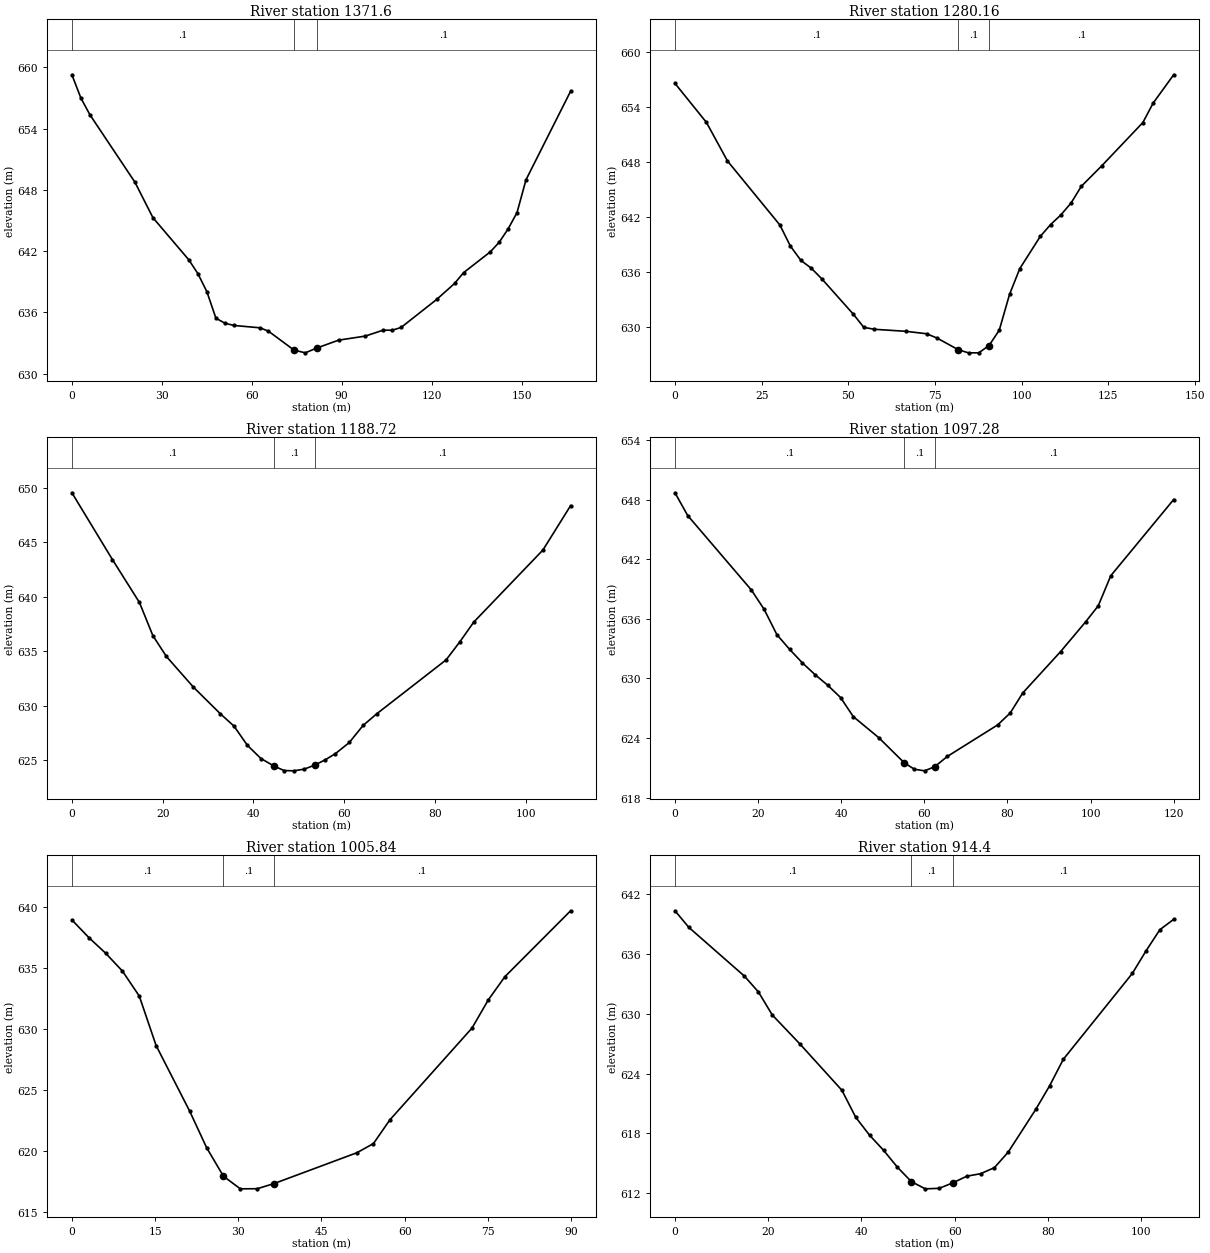
Type RM Length L Ch R = 1 ,1371.6  ,101.01,91.44,92.32
XS GIS Cut Line= 6
     625807.0388    4320572.5774     625751.7408    4320586.5783
     625734.9397    4320583.6678     625732.1498    4320581.1442
      625724.037    4320581.4945     625644.0179    4320589.2456
#Sta/Elev= 30
       0  659.26       3  656.98       6  655.35   21.02  648.75   27.02  645.28
   39.03  641.14   42.03   639.8   45.03  638.03   48.04  635.44   51.04  634.95
   54.04  634.73   62.73   634.5   65.57  634.17   74.09  632.32   77.86  632.05
    81.6  632.51   88.95  633.29   97.89  633.69  103.84  634.27  106.82  634.26
   109.8  634.53  121.71  637.28  127.66  638.84  130.64  639.89  139.57  641.93
  142.55  642.87  145.53  644.18   148.5  645.78  151.48  648.98  166.37  657.65
#Mann= 3 , 0 , 0
       0      .1       0   74.09      .1       0    81.6      .1       0
Bank Sta=74.09,81.6
XS Rating Curve= 0 ,0
Exp/Cntr=0.3,0.1

Type RM Length L Ch R = 1 ,1280.16 ,89.07,91.44,97.17
XS GIS Cut Line= 3
      625800.387     4320530.508     625726.4951    4320495.6829
     625666.0387    4320481.3643
#Sta/Elev= 30
       0  656.56    9.08   652.3   15.13   648.1   30.25  641.11   33.28  638.81
   36.31  637.25   39.33  636.39   42.36  635.23   51.43  631.38   54.46  629.94
   57.48  629.73   66.56  629.51   72.61  629.24   75.64  628.76   81.69   627.5
   84.65  627.16    87.6  627.16   90.56  627.95   93.52  629.63   96.48  633.53
   99.44  636.35  105.36  639.87  108.31  641.15  111.27   642.2  114.23  643.51
  117.19  645.33  123.11  647.58  134.94  652.29   137.9  654.41  143.82   657.5
#Mann= 3 , 0 , 0
       0      .1       0   81.69      .1       0   90.56      .1       0
Bank Sta=81.69,90.56
XS Rating Curve= 0 ,0
Exp/Cntr=0.3,0.1

Type RM Length L Ch R = 1 ,1188.72 ,93.06,91.44,91.71
XS GIS Cut Line= 5
     625816.1973    4320445.6847     625777.9064    4320422.7517
     625774.2283    4320420.6744     625767.4494    4320414.3992
     625722.2527    4320389.0443
#Sta/Elev= 25
       0  649.56    8.93  643.43   14.88   639.5   17.85  636.45   20.83  634.54
   26.78  631.73   32.73  629.28   35.71  628.16   38.68  626.39   41.66  625.18
   44.63  624.47   46.75  624.08   48.86  624.05   51.17   624.2   53.48  624.57
   55.79  625.05   58.09  625.63   61.14  626.65   64.19  628.22   67.24   629.3
   82.48  634.23   85.53   635.9   88.58   637.7  103.82  644.31  109.92  648.38
#Mann= 3 , 0 , 0
       0      .1       0   44.63      .1       0   53.48      .1       0
Bank Sta=44.63,53.48
XS Rating Curve= 0 ,0
Exp/Cntr=0.3,0.1

Type RM Length L Ch R = 1 ,1097.28 ,90.8,91.44,92.78
XS GIS Cut Line= 4
     625854.2701    4320345.2283     625800.1885    4320334.3685
     625793.0713    4320332.5609     625736.0592    4320325.1883
#Sta/Elev= 25
       0  648.68    3.06  646.39   18.39  638.89   21.45  636.95   24.52   634.4
   27.58  632.92   30.65  631.56   33.71  630.37   36.77   629.3   39.84  628.07
    42.9  626.15   49.03  624.03   55.16   621.5   57.61  620.85   60.06  620.69
    62.5  621.11   65.53  622.14   77.63  625.31   80.66  626.51   83.68  628.53
   92.76  632.68   98.81  635.69  101.84   637.3  104.86  640.33  119.99     648
#Mann= 3 , 0 , 0
       0      .1       0   55.16      .1       0    62.5      .1       0
Bank Sta=55.16,62.5
XS Rating Curve= 0 ,0
Exp/Cntr=0.3,0.1

Type RM Length L Ch R = 1 ,1005.84 ,91.75,91.44,88.63
XS GIS Cut Line= 3
     625857.5059    4320258.3391     625817.4468    4320244.0967
     625771.7535    4320231.4752
#Sta/Elev= 19
       0  638.95    3.04  637.51    6.07  636.23    9.11  634.76   12.15  632.71
   15.18  628.66   21.26  623.26   24.29  620.29   27.33  617.95   30.37  616.92
   33.41  616.93   36.44  617.35    51.4  619.88   54.37  620.63   57.33  622.57
   72.14  630.09   75.11  632.42   78.07   634.3   89.92   639.7
#Mann= 3 , 0 , 0
       0      .1       0   27.33      .1       0   36.44      .1       0
Bank Sta=27.33,36.44
XS Rating Curve= 0 ,0
Exp/Cntr=0.3,0.1

Type RM Length L Ch R = 1 ,914.4   ,93.22,91.44,87.47
XS GIS Cut Line= 3
     625912.1818    4320184.3247     625854.7337    4320168.2881
     625812.2425    4320147.4571
#Sta/Elev= 26
       0  640.36    2.98  638.69   14.91  633.79   17.89  632.21   20.88  629.89
   26.84  626.96   35.79  622.34   38.77  619.62   41.75  617.81   44.73  616.31
   47.72   614.6    50.7  613.16   53.68  612.43   56.66  612.48   59.64  613.04
    62.6   613.7   65.56  613.95   68.52  614.56   71.48  616.12   77.39  620.41
   80.35  622.77   83.31  625.45   98.09  634.06  101.05  636.34  104.01  638.46
  106.97   639.5
#Mann= 3 , 0 , 0
       0      .1       0    50.7      .1       0   59.64      .1       0
Bank Sta=50.7,59.64
XS Rating Curve= 0 ,0
Exp/Cntr=0.3,0.1

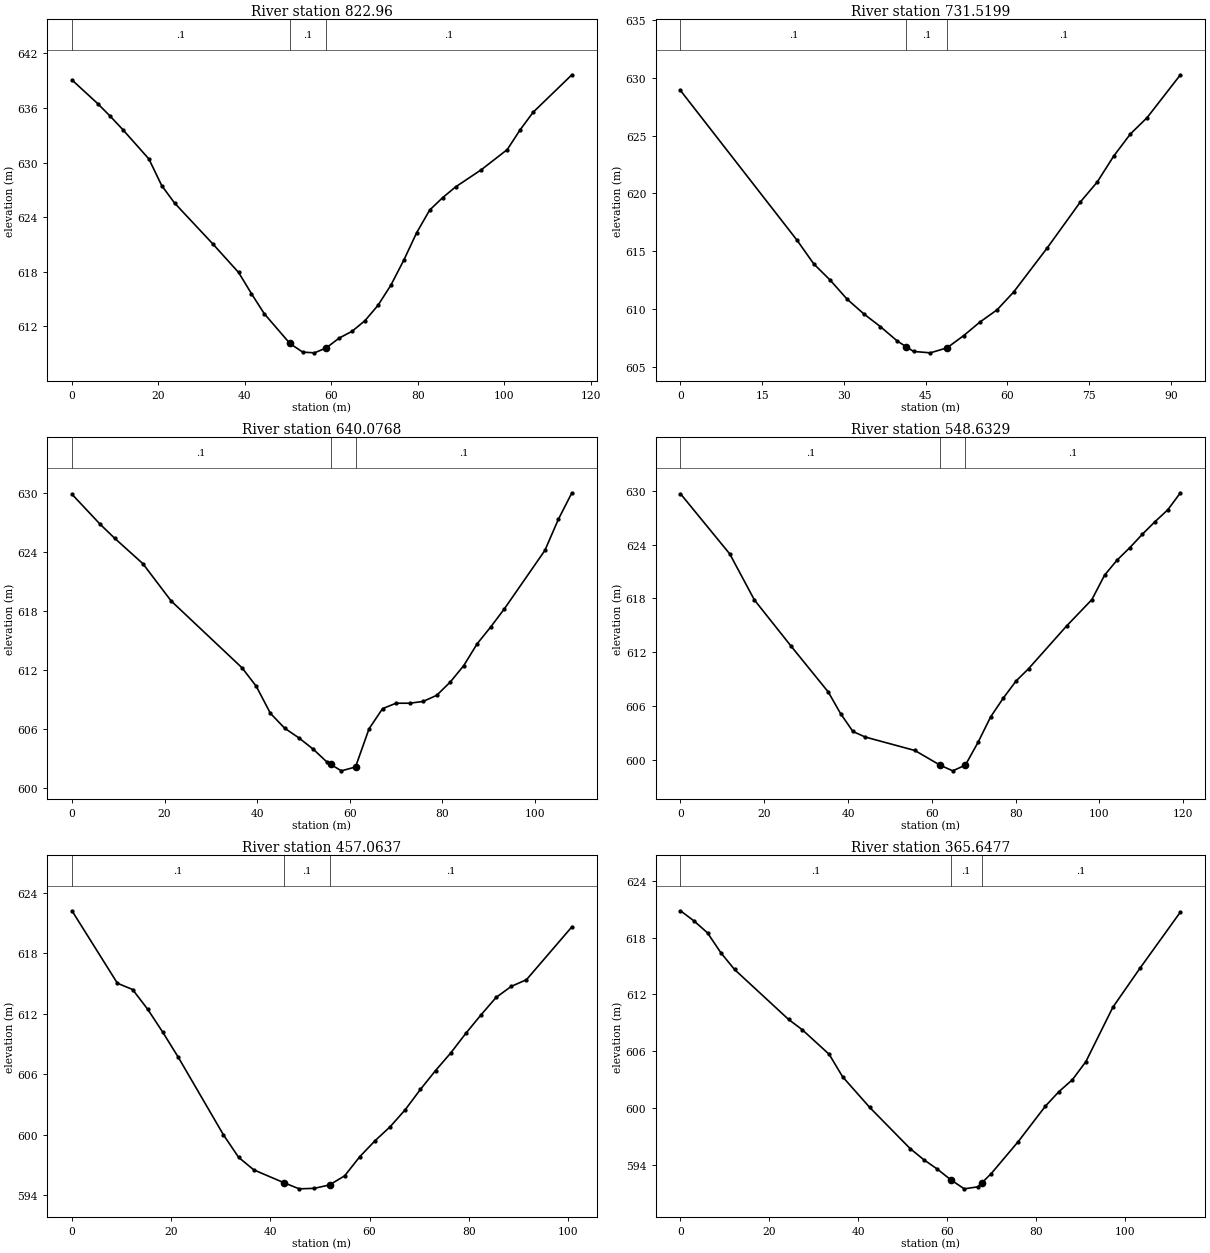
Type RM Length L Ch R = 1 ,822.96  ,96.78,91.44,89.26
XS GIS Cut Line= 4
      625926.233    4320079.5376      625872.862    4320079.8528
     625867.4984    4320080.7421     625811.1467    4320088.1238
#Sta/Elev= 30
       0  639.08    5.93  636.49     8.9  635.07   11.86  633.57   17.79   630.4
   20.76  627.47   23.72  625.56   32.62  621.04   38.55  617.92   41.51   615.6
   44.48  613.39   50.41  610.12   53.37  609.17   56.09  609.09   58.81  609.63
    61.8  610.71   64.79  611.46   67.78  612.63   70.77   614.3   73.76  616.52
   76.76  619.28   79.75  622.31   82.74  624.78   85.73  626.14   88.72  627.32
    94.7  629.22  100.69  631.43  103.68  633.61  106.67  635.53  115.64  639.65
#Mann= 3 , 0 , 0
       0      .1       0   50.41      .1       0   58.81      .1       0
Bank Sta=50.41,58.81
XS Rating Curve= 0 ,0
Exp/Cntr=0.3,0.1

Type RM Length L Ch R = 1 ,731.5199,90.36,91.44,94.9
XS GIS Cut Line= 3
     625854.5147    4319984.8561     625818.4905    4320007.9728
     625781.7735    4320040.3702
#Sta/Elev= 23
       0  628.91    21.4  615.95   24.46  613.91   27.52  612.48   30.57  610.86
   33.63  609.59   36.69  608.48   39.75  607.25   41.45  606.73    42.8  606.33
   45.86  606.21   48.92  606.64   51.98   607.7   55.04   608.9   58.11  609.93
   61.17  611.48   67.29  615.27   73.41  619.27   76.47  620.97   79.53  623.24
   82.59  625.15   85.65  626.56   91.77  630.27
#Mann= 3 , 0 , 0
       0      .1       0   41.45      .1       0   48.92      .1       0
Bank Sta=41.45,48.92
XS Rating Curve= 0 ,0
Exp/Cntr=0.3,0.1

Type RM Length L Ch R = 1 ,640.0768,93.19,91.44,103.86
XS GIS Cut Line= 3
     625819.7457    4319924.0818     625760.0897    4319937.9087
     625715.8489    4319953.0009
#Sta/Elev= 29
       0  629.83    6.12  626.77    9.19  625.38   15.31  622.79   21.43     619
   36.74  612.22    39.8  610.35   42.87   607.6   45.93   606.1   48.99  605.12
   52.05  603.99   55.11  602.65   55.87  602.43   58.18  601.77   61.24  602.16
   64.16  606.03   67.08  608.08      70  608.63   72.92  608.63   75.84  608.81
   78.77  609.43   81.69  610.77   84.61  612.44   87.53  614.67   90.45  616.37
   93.37  618.19  102.14  624.13  105.06  627.29  107.98  629.98
#Mann= 3 , 0 , 0
       0      .1       0   55.87      .1       0   61.24      .1       0
Bank Sta=55.87,61.24
XS Rating Curve= 0 ,0
Exp/Cntr=0.3,0.1

Type RM Length L Ch R = 1 ,548.6329,102.96,91.57,84.98
XS GIS Cut Line= 3
     625824.6846    4319871.0769     625776.0106    4319850.3336
     625713.0302    4319829.2726
#Sta/Elev= 26
       0  629.66   11.76  622.95   17.64  617.82   26.45  612.64   35.27  607.56
   38.21  605.15   41.15  603.16   44.09  602.54   55.93  601.04   61.97   599.4
   64.98  598.77      68  599.41   71.02  601.95   74.04   604.8   77.06  606.89
   80.08  608.78    83.1  610.17   92.15  614.92   98.19  617.86  101.21  620.58
  104.23  622.28  107.24  623.65  110.26  625.16  113.28  626.56   116.3  627.87
  119.32  629.77
#Mann= 3 , 0 , 0
       0      .1       0   61.97      .1       0      68      .1       0
Bank Sta=61.97,68
XS Rating Curve= 0 ,0
Exp/Cntr=0.3,0.1

Type RM Length L Ch R = 1 ,457.0637,89.83,91.42,93
XS GIS Cut Line= 2
     625781.3836    4319726.9002     625724.6719    4319810.2226
#Sta/Elev= 27
       0  622.19    9.16  615.01   12.22  614.39   15.27  612.43   18.33  610.14
   21.38  607.72   30.54  599.99    33.6  597.76   36.65  596.52   42.76  595.24
   45.81  594.64   48.87  594.69   51.92  595.03   54.98  595.93   58.03  597.83
   61.09   599.4   64.14  600.79   67.19  602.48   70.25  604.49    73.3  606.36
   76.36   608.1   79.41  610.05   82.47  611.88   85.52  613.61   88.57   614.7
   91.63  615.36  100.79   620.6
#Mann= 3 , 0 , 0
       0      .1       0   42.76      .1       0   51.92      .1       0
Bank Sta=42.76,51.92
XS Rating Curve= 0 ,0
Exp/Cntr=0.3,0.1

Type RM Length L Ch R = 1 ,365.6477,86.18,91.33,96.47
XS GIS Cut Line= 2
     625737.9011    4319667.8764     625649.0444    4319736.8801
#Sta/Elev= 26
       0  620.82    3.04  619.75    6.08  618.49    9.12  616.37   12.16  614.63
   24.33  609.36   27.37  608.29   33.45  605.69   36.49  603.31   42.57  600.09
   51.69  595.74   54.73  594.58   57.77  593.59   60.81  592.46   63.85   591.5
   66.89  591.71   67.77  592.11   69.93  593.11   76.02  596.49    82.1  600.21
   85.14  601.74   88.18     603   91.22  604.91    97.3  610.65  103.38  614.75
   112.5  620.69
#Mann= 3 , 0 , 0
       0      .1       0   60.81      .1       0   67.77      .1       0
Bank Sta=60.81,67.77
XS Rating Curve= 0 ,0
Exp/Cntr=0.3,0.1

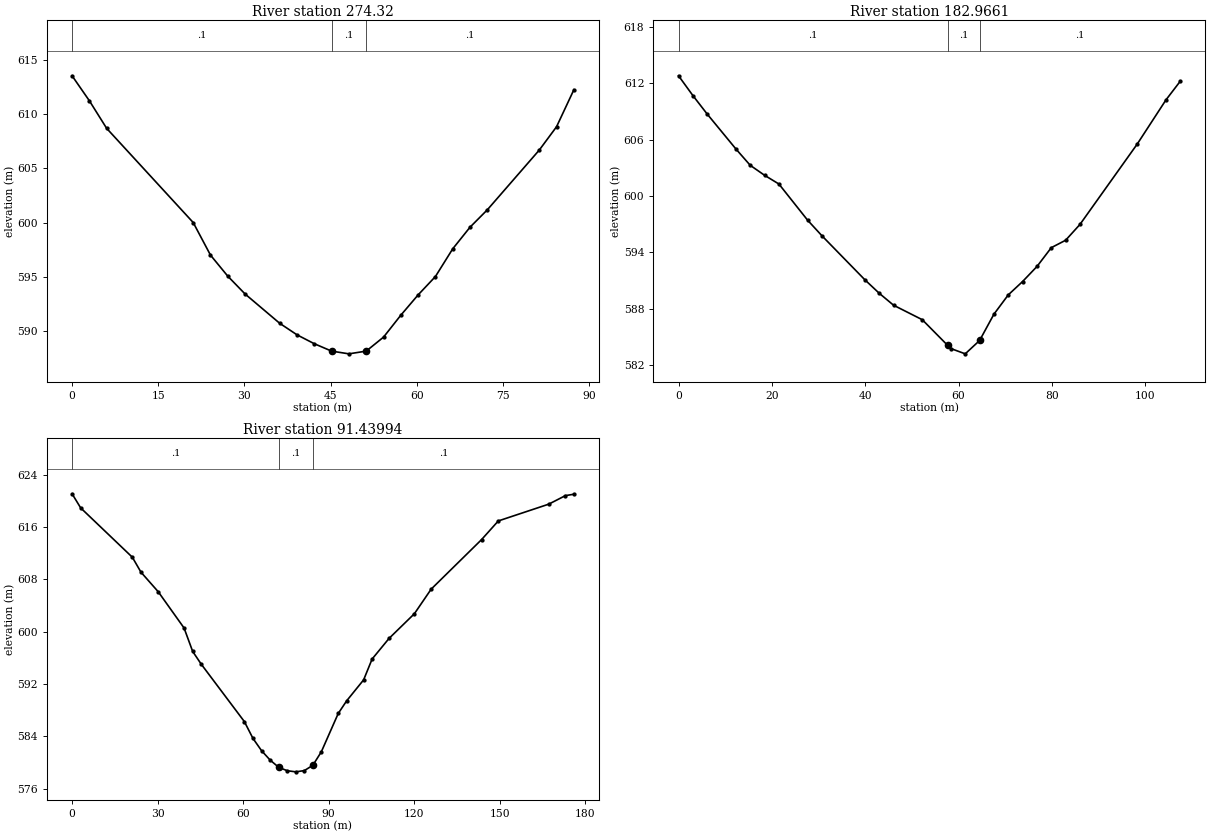
Type RM Length L Ch R = 1 ,274.32  ,86.69,91.35,97.88
XS GIS Cut Line= 2
     625737.2736    4319637.1996     625655.5518    4319606.4062
#Sta/Elev= 23
       0  613.53    3.01  611.23    6.02  608.69   21.08  600.02   24.09  597.02
    27.1  595.08   30.11  593.44   36.14  590.74   39.15  589.68   42.16  588.86
   45.17  588.18   48.18  587.93   51.19  588.18   54.21  589.47   57.22  591.49
   60.23  593.36   63.24  595.05   66.25   597.6   69.26  599.59   72.27  601.19
   81.31  606.69   84.32  608.84   87.33  612.24
#Mann= 3 , 0 , 0
       0      .1       0   45.17      .1       0   51.19      .1       0
Bank Sta=45.17,51.19
XS Rating Curve= 0 ,0
Exp/Cntr=0.3,0.1

Type RM Length L Ch R = 1 ,182.9661,104.26,91.53,76.11
XS GIS Cut Line= 2
     625771.3842    4319605.5405     625728.3893     4319506.983
#Sta/Elev= 27
       0  612.78    3.07  610.68    6.14  608.71   12.29     605   15.36  603.26
   18.43   602.2   21.51  601.27   27.65  597.43   30.72  595.77   39.94  591.08
   43.01  589.65   46.08  588.38   52.23  586.84   57.69   584.1   58.37  583.77
   61.44  583.21   64.52  584.63   67.59  587.43   70.66  589.48   73.73   590.9
   76.81   592.5   79.88   594.5   82.95  595.29   86.02  596.97   98.31  605.53
  104.46  610.22  107.53  612.21
#Mann= 3 , 0 , 0
       0      .1       0   57.69      .1       0   64.52      .1       0
Bank Sta=57.69,64.52
XS Rating Curve= 0 ,0
Exp/Cntr=0.3,0.1

Type RM Length L Ch R = 1 ,91.43994,75.42,91.44,65.83
XS GIS Cut Line= 5
     625876.0202     4319496.789     625813.5551    4319485.7558
     625795.5724    4319486.8814     625761.4111    4319476.7282
     625707.2226    4319499.7069
#Sta/Elev= 30
       0  621.06    3.02   618.9   21.14  611.36   24.16  609.08   30.21  606.09
   39.27  600.55   42.29  596.97   45.31  595.01   60.41  586.25   63.43  583.68
   66.43  581.81   69.44  580.37   72.44  579.27   75.44  578.74   78.45  578.57
   81.45  578.76   84.42  579.57   87.39  581.62   93.33  587.49    96.3  589.43
  102.24  592.63  105.21  595.81  111.15  598.96  120.03  602.73  125.92  606.49
  143.57  614.05  149.46  616.91  167.12  619.47     173  620.78  175.95  620.99
#Mann= 3 , 0 , 0
       0      .1       0   72.44      .1       0   84.42      .1       0
Bank Sta=72.44,84.42
XS Rating Curve= 0 ,0
Exp/Cntr=0.3,0.1

River Reach=Dry Fork        ,4
Reach XY= 30
     625794.0678    4319395.3652      625538.977    4319420.1078
     625427.8518    4319337.5576     625403.2455    4319344.7014
     625185.7576    4319477.2579      624706.282    4319905.1653
     624496.7812    4319970.9714     624372.2054    4319973.4222
     624092.7616    4319899.5337     623972.1114    4319789.2022
     623750.9748    4319661.4872     623642.5004     4319652.086
     623516.1022    4319697.0141     623400.6102    4319858.2586
     623365.0307    4320212.3434     623230.7474    4320424.2035
     622882.4298    4320456.0251     622752.9089    4320434.5223
      622533.878    4320445.9312     622394.6697    4320507.4025
      622276.658    4320651.2165     622182.2015    4320872.6732
     622163.8986    4321095.8849     622129.0202    4321198.1113
     621879.7822    4321321.9366     621683.1681    4321308.0669
     621609.9067    4321348.9241     621575.1209    4321491.8709
     621595.7584      4321673.64      621523.791    4321829.9594

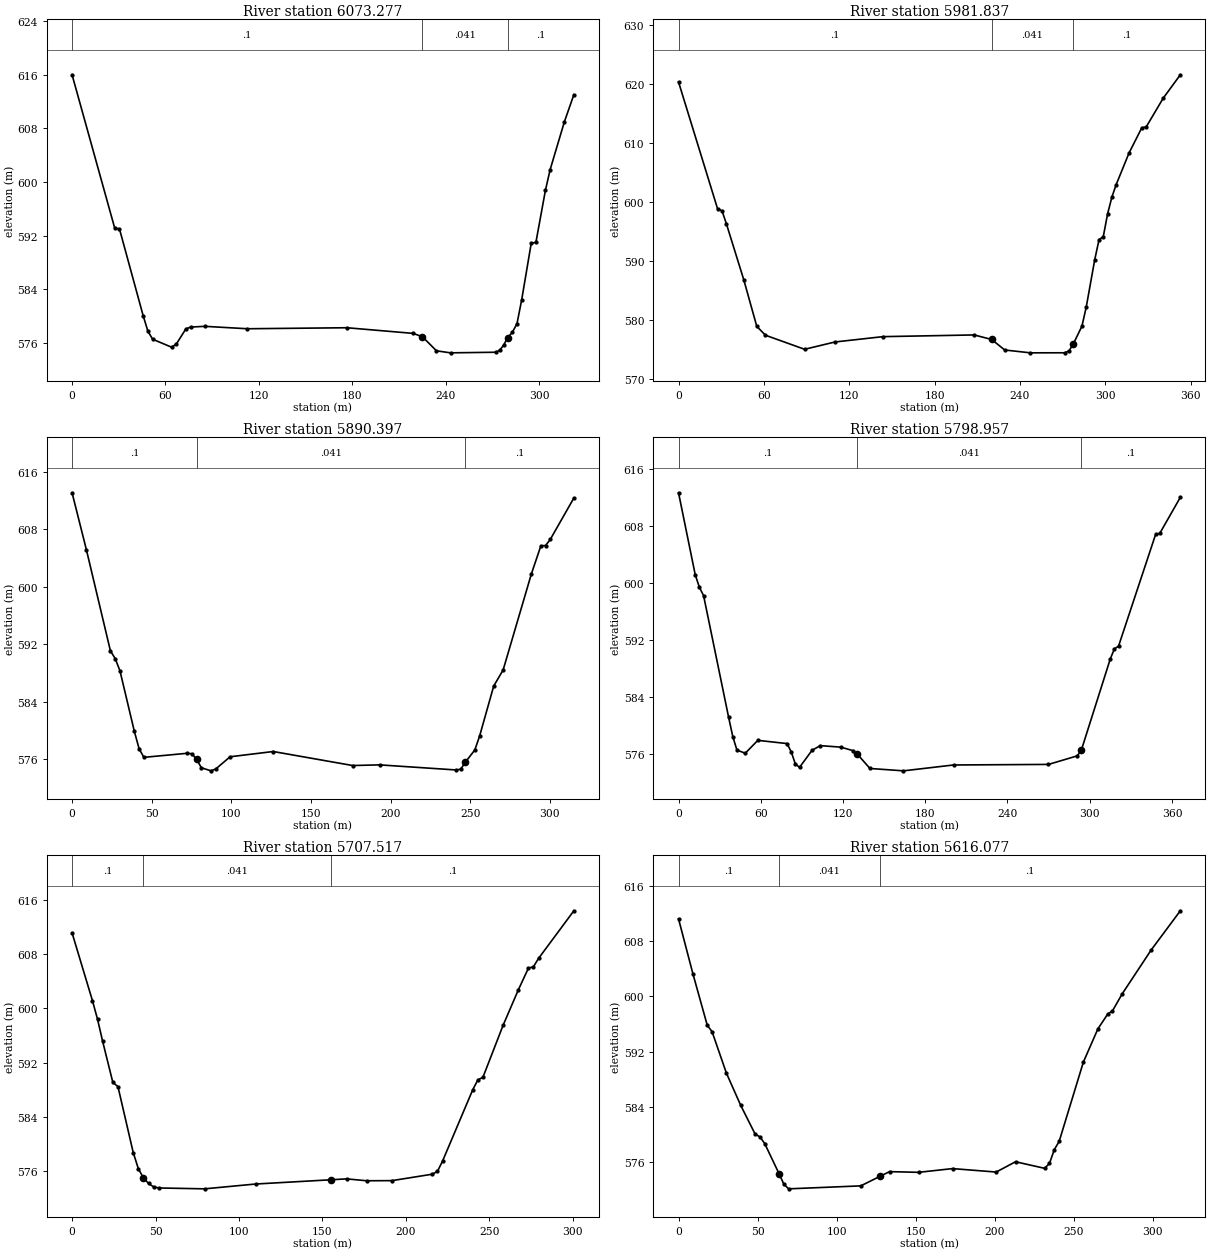
Type RM Length L Ch R = 1 ,6073.277,86.87,91.44,91.25
XS GIS Cut Line= 5
     625681.4257    4319151.0648     625716.8129    4319355.0256
     625725.6597    4319417.5434     625724.5422    4319427.0167
     625723.3576    4319469.6231
#Sta/Elev= 30
       0  615.98    27.4  593.12   30.44  593.01   45.66  580.08   48.71  577.76
   51.75  576.57   63.93  575.38   66.97  575.85   73.06   578.1   76.11  578.38
   85.24  578.49  112.64  578.13  176.57  578.28  219.03  577.44  225.05  576.94
  234.07  574.84  243.09  574.54  272.53  574.63  274.92     575   277.3  575.71
  279.69  576.79  282.73  577.58  285.78  578.88  288.82  582.47  294.91  590.85
  297.95  591.02  304.04  598.76  307.09  601.86  316.22  608.97  322.31  613.01
#Mann= 3 , 0 , 0
       0      .1       0  225.05    .041       0  279.69      .1       0
Bank Sta=225.05,279.69
XS Rating Curve= 0 ,0
Exp/Cntr=0.3,0.1

Type RM Length L Ch R = 1 ,5981.837,80.38,91.44,85.8
XS GIS Cut Line= 5
     625594.9068    4319162.9711     625630.4225    4319364.6439
     625629.2956    4319389.1838     625634.3677    4319425.0273
     625637.2402    4319512.2218
#Sta/Elev= 30
       0  620.32   27.51  598.81   30.56  598.53   33.62  596.34   45.85  586.86
   55.01  578.96   61.13  577.46   88.63  575.08  110.03  576.32  143.65  577.22
  207.85  577.51  220.13  576.74  229.34  574.96  247.44  574.48  271.56  574.49
  274.57  574.82  277.58  576.01  283.59  578.98   286.6  582.18  292.62  590.27
  295.63  593.63  298.63  594.16  301.64  597.99  304.65  600.83  307.66  602.94
  316.68  608.28  325.71  612.58  328.72  612.69  340.75  617.58  352.78  621.54
#Mann= 3 , 0 , 0
       0      .1       0  220.13    .041       0  277.58      .1       0
Bank Sta=220.13,277.58
XS Rating Curve= 0 ,0
Exp/Cntr=0.3,0.1

Type RM Length L Ch R = 1 ,5890.397,63.76,91.44,130.01
XS GIS Cut Line= 6
     625527.9095    4319205.4967     625551.7221     4319335.672
     625549.3408     4319373.772     625541.8154    4319403.9742
     625544.7828    4319432.5614     625564.4796    4319514.8676
#Sta/Elev= 30
       0  613.08    9.02  605.13   24.06  591.09   27.07     590   30.08  588.29
    39.1  579.87   42.11  577.43   45.11  576.25   72.18  576.81   75.19  576.75
    78.2  575.97   81.21   574.8   87.22  574.37   90.23  574.63   99.25  576.33
  126.32  577.06  176.17  575.11  193.15   575.2  241.31  574.49  244.05   574.6
  247.01  575.59  252.93  577.29  255.89   579.2  264.77  586.18  270.69  588.42
  288.45  601.81  294.37  605.69  297.33  605.74  300.29  606.59  315.09  612.35
#Mann= 3 , 0 , 0
       0      .1       0    78.2    .041       0  247.01      .1       0
Bank Sta=78.2,247.01
XS Rating Curve= 0 ,0
Exp/Cntr=0.3,0.1

Type RM Length L Ch R = 1 ,5798.957,119.94,91.44,32.32
XS GIS Cut Line= 6
     625486.4274    4319222.5024     625500.6904    4319315.7951
     625486.6381    4319345.7031     625451.0247    4319391.6439
     625421.3153    4319447.5579     625469.6068    4319554.3846
#Sta/Elev= 30
       0  612.63   12.18  601.15   15.22  599.38   18.27  598.23   36.53  581.19
   39.58  578.48   42.62  576.58   48.71  576.15   57.84  577.95   79.15   577.5
    82.2  576.35   85.24  574.64   88.29  574.17   97.38  576.55  103.39  577.21
  118.41     577  127.42   576.5  130.48  576.01  139.66  574.01  164.13  573.68
  200.62   574.5  269.91  574.58  290.95  575.78  293.96  576.62     315  589.36
     318  590.77  321.01  591.14  348.06  606.79  351.07  606.93   366.1  611.99
#Mann= 3 , 0 , 0
       0      .1       0  130.48    .041       0  293.96      .1       0
Bank Sta=130.48,293.96
XS Rating Curve= 0 ,0
Exp/Cntr=0.3,0.1

Type RM Length L Ch R = 1 ,5707.517,90.48,91.44,66.7
XS GIS Cut Line= 5
     625359.8172    4319288.4289       625400.08    4319370.7418
     625397.1059    4319416.5575     625401.0746    4319437.0627
     625462.0943    4319565.6064
#Sta/Elev= 30
       0  611.11   12.22  601.12   15.27  598.37   18.33  595.12   24.44  589.07
   27.49  588.46   36.65  578.74   39.71  576.36   42.76     575   45.82  574.19
   48.87  573.67   51.93  573.52   79.41  573.39     110   574.1  155.45  574.73
  164.49  574.86   176.6  574.58  191.73   574.6  215.95  575.55  218.98  575.97
  222.01  577.47  240.17  588.02   243.2  589.45  246.23  589.83  258.34  597.51
  267.42   602.7  273.47  605.91   276.5  606.12  279.53  607.34  300.72  614.37
#Mann= 3 , 0 , 0
       0      .1       0   42.76    .041       0  155.45      .1       0
Bank Sta=42.76,155.45
XS Rating Curve= 0 ,0
Exp/Cntr=0.3,0.1

Type RM Length L Ch R = 1 ,5616.077,100.39,91.44,82.89
XS GIS Cut Line= 6
     625270.4063    4319308.7693     625301.2489    4319374.5473
     625306.4441    4319388.6348     625314.5418    4319402.1118
     625318.6389    4319419.4314     625420.9147    4319586.8128
#Sta/Elev= 30
       0  611.23    9.08  603.29   18.16  595.83   21.19  594.91   30.27   588.9
   39.35  584.22   48.43  580.08   51.46  579.67   54.49  578.71   63.57  574.34
    66.6  572.83   69.62  572.15  115.25  572.58  127.31  573.95  133.44  574.64
  151.83  574.54  173.29  575.08  200.87  574.58  213.13  576.07  231.52  575.12
  234.59  575.83  237.65  577.83  240.72  579.02  256.04  590.51  265.24  595.32
  271.37  597.43  274.43  597.91  280.56  600.37  298.95  606.74  317.34   612.4
#Mann= 3 , 0 , 0
       0      .1       0   63.57    .041       0  127.31      .1       0
Bank Sta=63.57,127.31
XS Rating Curve= 0 ,0
Exp/Cntr=0.3,0.1