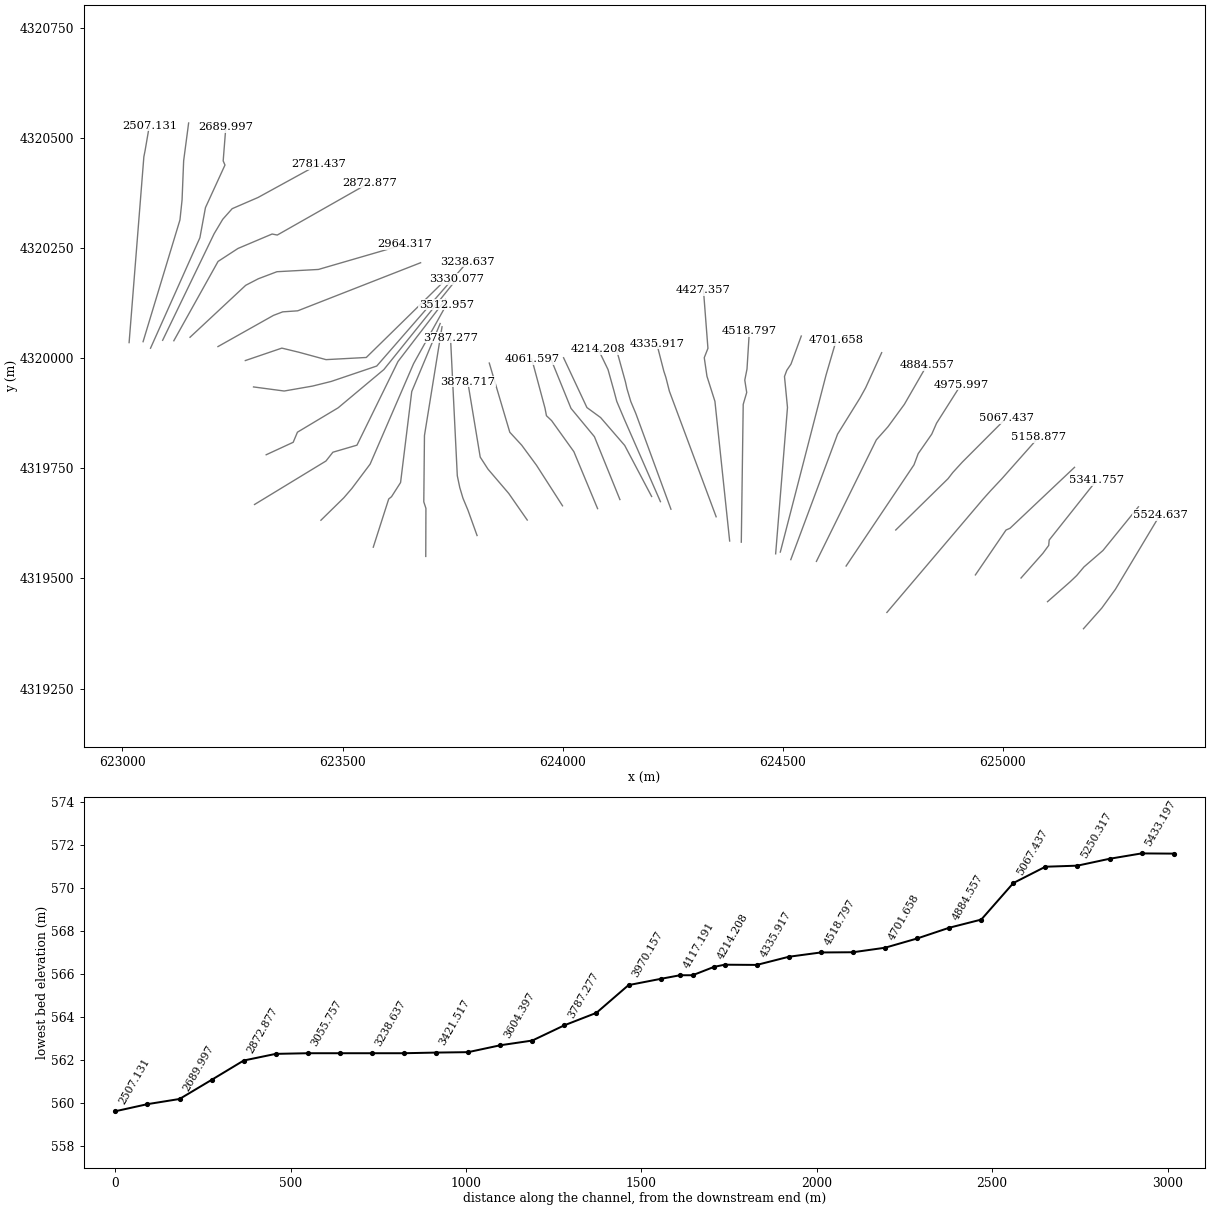
HEC-RAS study RedCreek.prj: RedCreek

--- RedCreek.g01 (geometry) --- (continued)

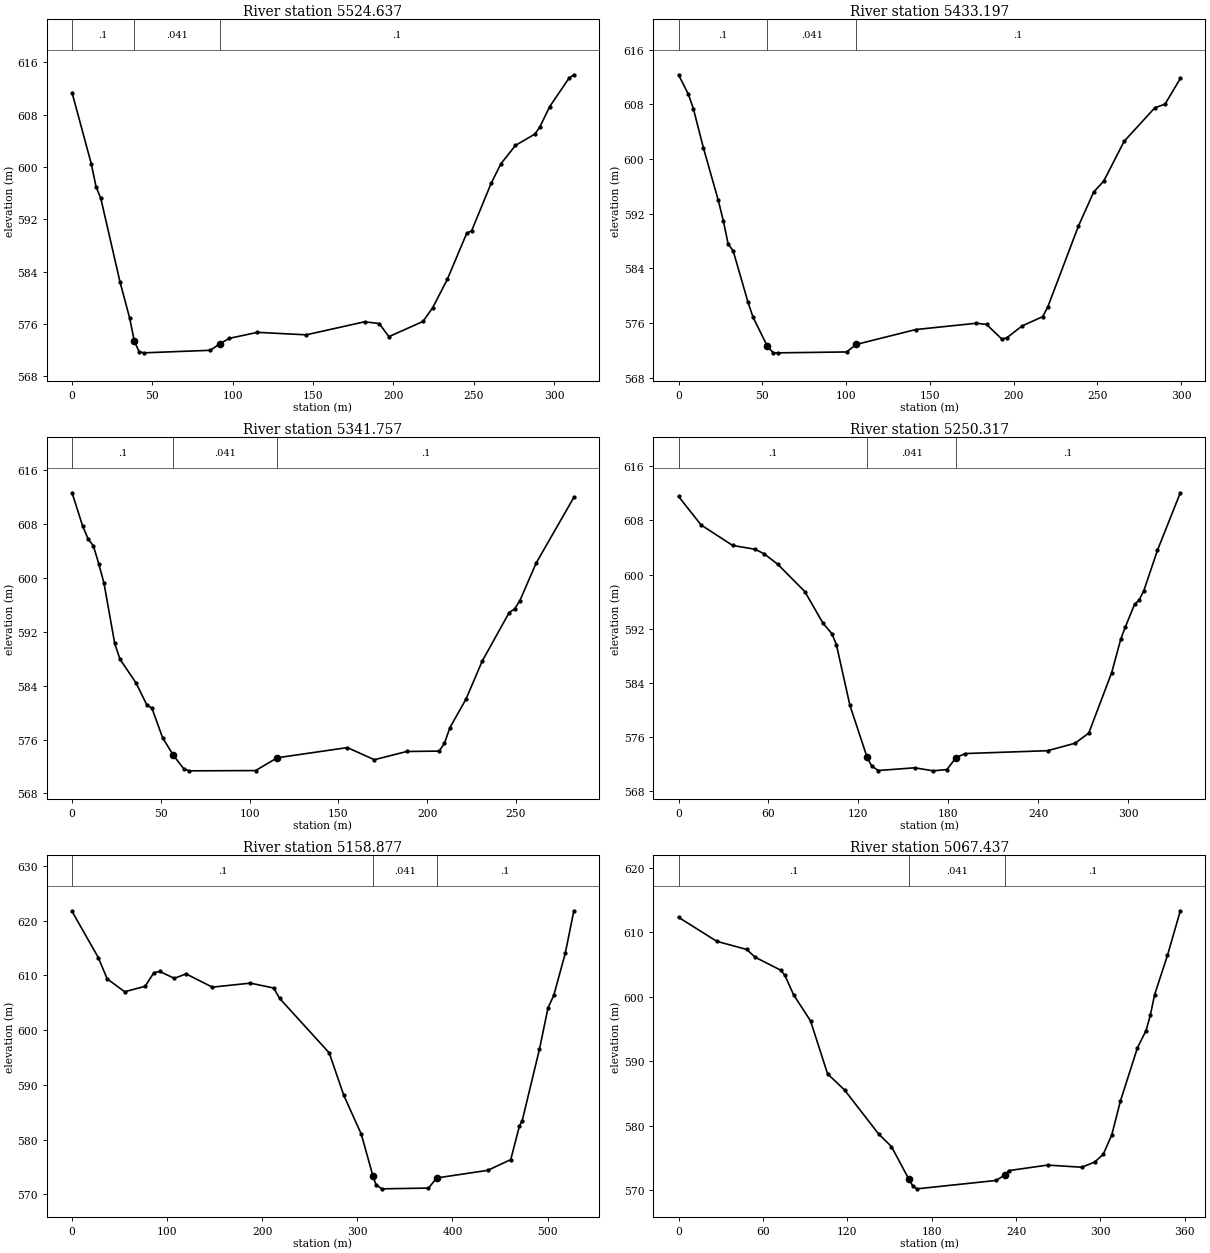
Type RM Length L Ch R = 1 ,5524.637,100.54,91.44,80.95
XS GIS Cut Line= 4
     625183.4032    4319385.8691     625224.9719     4319432.748
     625255.9556    4319475.4559     625357.2222    4319644.4034
#Sta/Elev= 30
       0  611.33   11.93   600.5   14.92  596.98    17.9  595.18   29.84  582.43
    35.8  576.96   38.79  573.35   41.77  571.77   44.75   571.6    86.1  571.99
   91.97  572.98   97.83  573.81  115.42  574.73  145.72  574.35  182.09  576.34
  191.18  576.08  197.24  574.07  218.45  576.39  224.51  578.49   233.6  582.82
  245.72  589.88  248.75  590.24  260.87  597.48  266.94  600.46  276.03  603.28
  288.15  605.02  291.18  606.09  297.24  609.16  309.36  613.56  312.39  614.07
#Mann= 3 , 0 , 0
       0      .1       0   38.79    .041       0   91.97      .1       0
Bank Sta=38.79,91.97
XS Rating Curve= 0 ,0
Exp/Cntr=0.3,0.1

Type RM Length L Ch R = 1 ,5433.197,86,91.44,105.31
XS GIS Cut Line= 6
     625101.7498    4319447.3331     625153.4117    4319492.7843
     625168.0273    4319506.7279     625184.5015    4319526.2593
     625227.6615    4319563.6204     625308.2742    4319662.9243
#Sta/Elev= 30
       0  612.31    5.93  609.43     8.9   607.3   14.83  601.63   23.72  593.94
   26.69  590.98   29.65  587.52   32.62  586.53   41.51  578.99   44.48  576.83
   53.02  572.58   56.56  571.62   59.63  571.61  100.41  571.74  106.09  572.84
  141.64  575.02  177.78  575.94  183.87  575.77  193.01  573.63  196.05  573.82
  205.19  575.56  217.37   576.9  220.41  578.29  238.69  590.13  247.82  595.13
  253.91  596.77  266.09  602.59  284.37  607.48  290.46  608.01  299.59  611.77
#Mann= 3 , 0 , 0
       0      .1       0   53.02    .041       0  106.09      .1       0
Bank Sta=53.02,106.09
XS Rating Curve= 0 ,0
Exp/Cntr=0.3,0.1

Type RM Length L Ch R = 1 ,5341.757,97.53,91.44,75.9
XS GIS Cut Line= 5
     625041.5293    4319501.0992     625091.2244    4319557.2514
      625104.396    4319575.1531     625105.5232    4319587.3782
     625213.1409      4319722.95
#Sta/Elev= 30
       0  612.62       6  607.65       9   605.8      12  604.74      15  602.12
      18  599.17      24  590.28   26.99  587.91   35.99  584.42   41.99   581.2
   44.99  580.64   50.99  576.27   56.99  573.69   62.99  571.63   65.99  571.36
  103.35   571.4  115.56   573.3  155.04  574.81  170.22  573.01  188.44  574.23
  206.66  574.29   209.7  575.42  212.74  577.76  221.85  582.01  230.96  587.64
  246.14  594.84  249.18  595.37  252.21  596.63  261.32  602.18  282.58  611.94
#Mann= 3 , 0 , 0
       0      .1       0   56.99    .041       0  115.56      .1       0
Bank Sta=56.99,115.56
XS Rating Curve= 0 ,0
Exp/Cntr=0.3,0.1

Type RM Length L Ch R = 1 ,5250.317,85.75,91.44,96.56
XS GIS Cut Line= 4
     624937.8568    4319508.1428     625007.4331    4319610.1324
     625016.4487    4319614.0803     625163.0627     4319752.555
#Sta/Elev= 30
       0  611.52   15.06  607.31   36.14  604.29   51.19  603.72   57.21  603.05
   66.25  601.51   84.32  597.48   96.36  592.85  102.38  591.27  105.39  589.64
  114.43  580.68  125.92  573.01  128.87  571.77   133.3  571.09  157.75  571.49
  169.97  571.04  179.14  571.23  185.25  572.99  191.36  573.59  246.36  574.01
  264.69  575.11  273.86  576.61  289.14  585.52  295.25   590.5  298.31  592.29
  304.42   595.6  307.47  596.24  310.53  597.57   319.7  603.58  334.97  612.06
#Mann= 3 , 0 , 0
       0      .1       0  125.92    .041       0  185.25      .1       0
Bank Sta=125.92,185.25
XS Rating Curve= 0 ,0
Exp/Cntr=0.3,0.1

Type RM Length L Ch R = 1 ,5158.877,111.52,91.44,89.65
XS GIS Cut Line= 5
     624736.7907    4319422.8762     624955.5048     4319680.538
      624972.271    4319699.2639     624998.1118    4319726.8588
     625082.2156    4319821.6261
#Sta/Elev= 30
       0  621.67   27.65  613.22   36.87  609.36    55.3     607   76.81  607.99
   86.03  610.48   92.17   610.7  107.54  609.45  119.83  610.26  147.48  607.84
  187.42  608.57     212  607.68  218.15   605.8  270.38  595.83  285.74  588.06
  304.17  580.95  316.46  573.26  319.54  571.75  325.68  570.99  374.74  571.13
  383.46  572.98  437.11  574.37  461.25  576.33   470.3  582.41  473.32  583.45
  491.42  596.49  500.47  604.06   506.5  606.34  518.57  614.01  527.62  621.79
#Mann= 3 , 0 , 0
       0      .1       0  316.46    .041       0  383.46      .1       0
Bank Sta=316.46,383.46
XS Rating Curve= 0 ,0
Exp/Cntr=0.3,0.1

Type RM Length L Ch R = 1 ,5067.437,97.26,91.44,107.4
XS GIS Cut Line= 5
     624756.8991    4319610.2016     624875.7635    4319726.8553
     624886.6658    4319740.9817     624908.4602    4319764.7915
       625007.46    4319863.9375
#Sta/Elev= 30
       0  612.32   27.25  608.59   48.45  607.34   54.51  606.13   72.67  604.12
    75.7   603.3   81.76  600.33   93.87  596.25  105.98  588.05  118.09  585.54
  142.32  578.72   151.4  576.78  163.52  571.83  166.54  570.68  169.52  570.23
   225.8  571.53   231.9  572.36  234.94  573.06  262.35  573.91  286.72  573.58
  295.86  574.38  301.95  575.57  308.04  578.59  314.13   583.8  326.32  592.11
  332.41  594.77  335.46  597.14   338.5  600.33  347.64  606.42  356.78  613.33
#Mann= 3 , 0 , 0
       0      .1       0  163.52    .041       0   231.9      .1       0
Bank Sta=163.52,231.9
XS Rating Curve= 0 ,0
Exp/Cntr=0.3,0.1

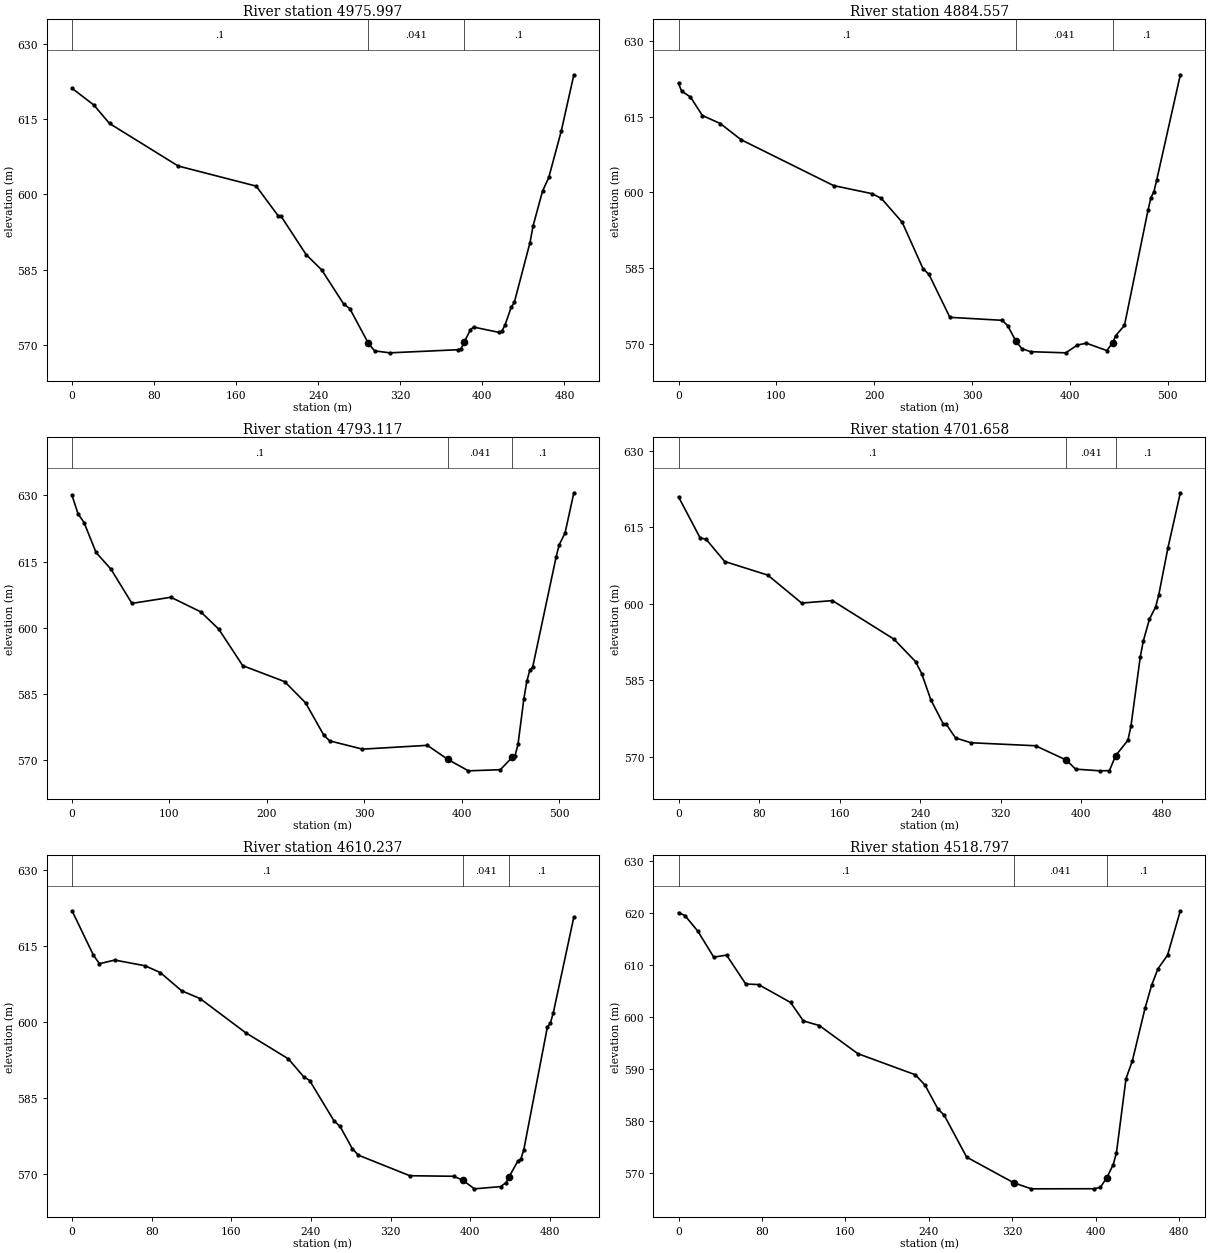
Type RM Length L Ch R = 1 ,4975.997,95.79,91.44,85.26
XS GIS Cut Line= 6
     624644.1202    4319528.3129     624798.3607    4319758.2535
     624807.8911    4319783.6495     624838.7266    4319828.0039
       624849.69    4319852.9745     624905.3383    4319940.6811
#Sta/Elev= 30
       0   621.1    21.3  617.77   36.51  614.11  103.45  605.66  179.52  601.66
  200.81  595.79  203.86  595.64   228.2  588.05  243.41     585  264.71  578.25
   270.8   577.3  288.94  570.39  294.96  568.92  309.67  568.53  376.22  569.15
  379.25  569.36  382.28  570.66  388.37  573.13  391.42  573.65  415.86  572.61
  418.92   572.8  421.97     574  428.08  577.58  431.14  578.56  446.41  590.43
  449.47  593.79  458.63  600.66  464.74  603.39  476.96  612.66  489.18  623.79
#Mann= 3 , 0 , 0
       0      .1       0  288.94    .041       0  382.28      .1       0
Bank Sta=288.94,382.28
XS Rating Curve= 0 ,0
Exp/Cntr=0.3,0.1

Type RM Length L Ch R = 1 ,4884.557,87.24,91.44,97.59
XS GIS Cut Line= 5
     624576.6513    4319538.8962     624712.8119    4319814.9979
     624739.3446    4319844.8874     624776.5024     4319895.735
     624827.5128    4319984.2418
#Sta/Elev= 30
       0  621.65    3.05  620.14   12.19  618.94   24.38  615.27   42.67  613.68
   64.01  610.46   158.5  601.36  198.12  599.74  207.27  598.82   228.6  594.09
  249.94  584.85  256.03  583.71  277.37   575.2  330.69  574.61   336.4  573.57
  344.96  570.45  350.82  568.99  359.81  568.38   395.8  568.15   407.8   569.7
   416.8  570.07  437.84   568.6  443.85  570.17  446.85  571.55  455.86   573.6
   479.9  596.45   482.9  598.97  485.91  600.12  488.91  602.56  512.95  623.36
#Mann= 3 , 0 , 0
       0      .1       0  344.96    .041       0  443.85      .1       0
Bank Sta=344.96,443.85
XS Rating Curve= 0 ,0
Exp/Cntr=0.3,0.1

Type RM Length L Ch R = 1 ,4793.117,80.58,91.46,98.34
XS GIS Cut Line= 5
     624518.4429     4319542.865     624624.7276    4319827.9736
     624675.6693    4319910.0899     624688.5595    4319933.4419
     624724.9094    4320013.0637
#Sta/Elev= 30
       0  629.96    6.15  625.79   12.29  623.84   24.59  617.08   39.96  613.27
   61.47  605.54  101.43  606.93  132.16  603.62   150.6  599.71  175.19  591.45
  218.22  587.84  239.73  583.03  258.17  575.81  264.32  574.44  298.13  572.56
  364.67  573.42  385.81  570.23  406.84  567.65  439.66  567.91  451.73  570.69
  454.75  571.09  457.76  573.62   463.8  583.97  466.82   587.9  469.84  590.37
  472.86  591.14     497  616.13  500.02  618.78  506.06  621.47  515.11  630.57
#Mann= 3 , 0 , 0
       0      .1       0  385.81    .041       0  451.73      .1       0
Bank Sta=385.81,451.73
XS Rating Curve= 0 ,0
Exp/Cntr=0.3,0.1

Type RM Length L Ch R = 1 ,4701.658,77.77,91.42,88.79
XS GIS Cut Line= 3
     624494.6303    4319560.0629      624598.587    4319962.4588
      624621.808    4320041.7798
#Sta/Elev= 30
       0  620.95   21.39  612.93    27.5  612.62   45.84  608.28   88.62  605.61
  122.24  600.13   152.8  600.61  213.92  593.05  235.31  588.65  241.42  586.31
  250.59  581.12  262.81  576.45  265.87  576.35  275.03  573.68  290.31  572.73
  354.49  572.14  385.05  569.33  394.22  567.56  418.67  567.22  427.85  567.26
  433.97  570.18  446.22  573.21  449.28  576.05  458.46  589.54  461.52  592.71
  467.65  596.99  473.77  599.38  476.83  601.73  486.01     611  498.26  621.76
#Mann= 3 , 0 , 0
       0      .1       0  385.05    .041       0  433.97      .1       0
Bank Sta=385.05,433.97
XS Rating Curve= 0 ,0
Exp/Cntr=0.3,0.1

Type RM Length L Ch R = 1 ,4610.237,156.01,91.44,101.75
XS GIS Cut Line= 6
      624484.047    4319556.0942     624510.9107    4319888.5798
     624504.1229    4319958.9428     624509.4006    4319973.0855
     624518.8483     4319987.005     624542.2554     4320050.866
#Sta/Elev= 30
       0  621.91   21.42  613.15   27.54  611.46   42.84  612.18   73.45  611.05
   88.75   609.7  110.17   606.1  128.53  604.59  174.44  597.83  217.28  592.68
  232.58  589.18   238.7   588.4  263.18  580.44   269.3  579.33  281.54  574.95
  287.67  573.66  339.37   569.6  383.37  569.49  392.33  568.75  404.27  567.01
  430.58  567.45  436.19  568.25  439.15   569.4  448.02  572.53  450.97  572.89
  453.93  574.77  477.59  598.95  480.55  599.71   483.5  601.73   504.2  620.69
#Mann= 3 , 0 , 0
       0      .1       0  392.33    .041       0  439.15      .1       0
Bank Sta=392.33,439.15
XS Rating Curve= 0 ,0
Exp/Cntr=0.3,0.1

Type RM Length L Ch R = 1 ,4518.797,75.32,91.44,97.29
XS GIS Cut Line= 6
     624405.9948    4319582.5526     624410.3424    4319895.6221
     624418.2799    4319922.6097     624413.9212    4319950.6806
      624418.953    4319975.9214     624424.2938    4320061.5457
#Sta/Elev= 30
       0  620.02    6.14  619.45   18.42  616.48   33.77  611.47   46.04  611.86
   64.46  606.31   76.74  606.21  107.44  602.77  119.71  599.23  135.06  598.34
   171.9  592.95  227.15  588.89  236.36   586.9  248.64  582.36  254.78  581.12
  276.26  573.09  321.54  568.15  338.42     567  398.44  567.02  404.57   567.3
  410.69  569.15  416.82  571.66  419.89   573.9  429.08  588.14  435.21   591.6
  447.46  601.77  453.59  606.04  459.72  609.24  468.91  611.85  481.17  620.37
#Mann= 3 , 0 , 0
       0      .1       0  321.54    .041       0  410.69      .1       0
Bank Sta=321.54,410.69
XS Rating Curve= 0 ,0
Exp/Cntr=0.3,0.1

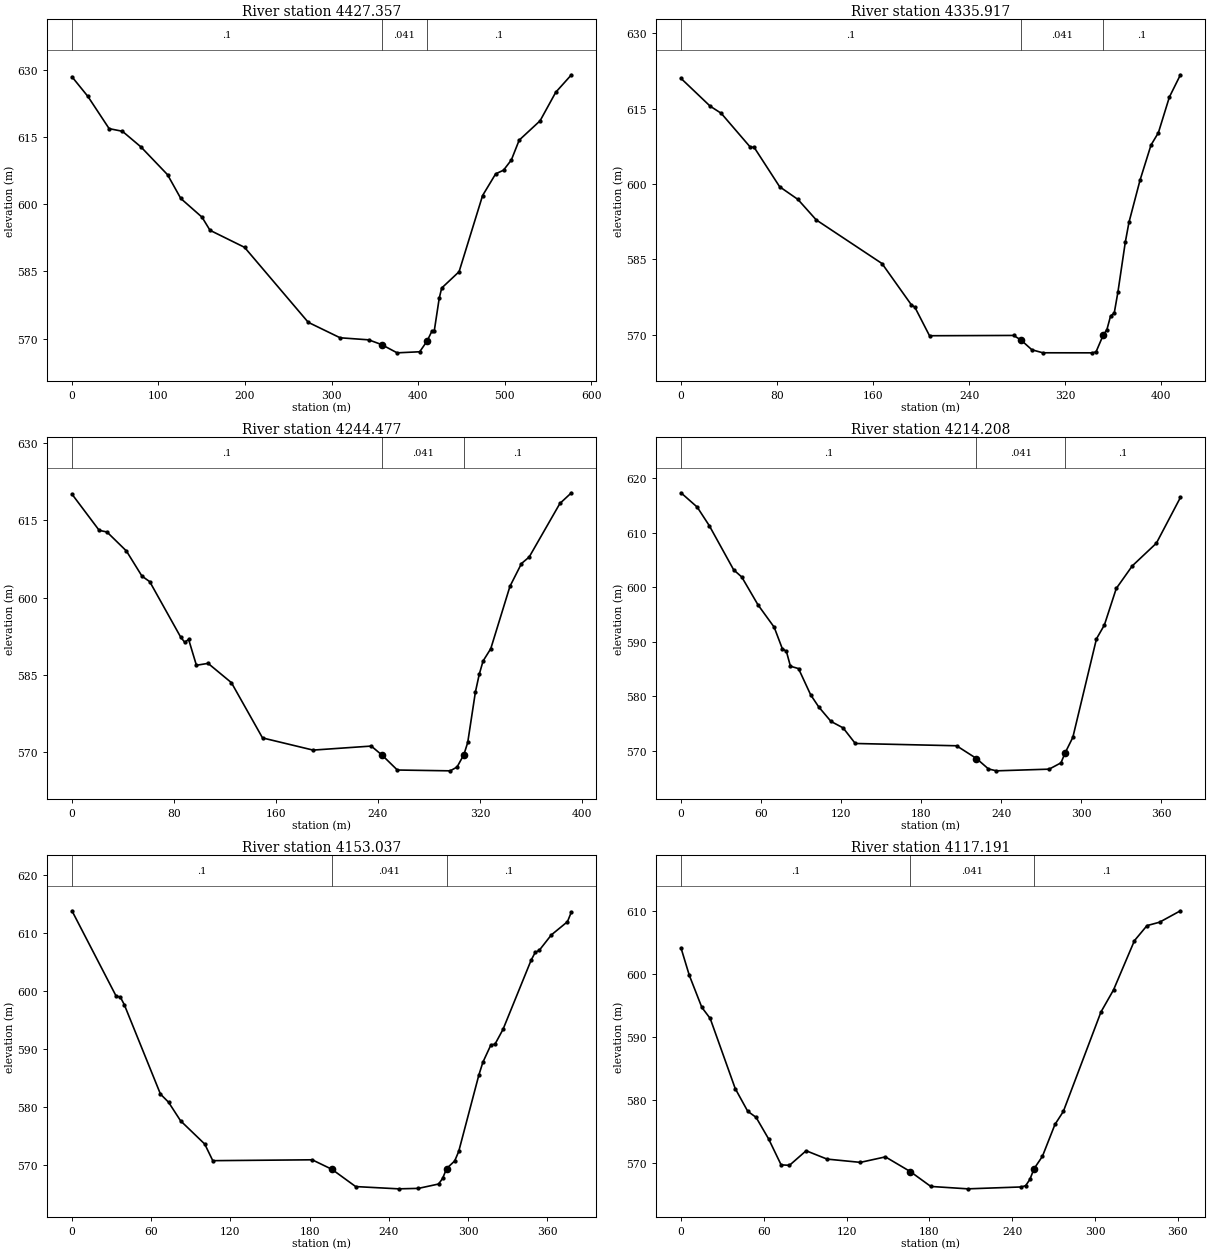
Type RM Length L Ch R = 1 ,4427.357,89.69,91.44,106.18
XS GIS Cut Line= 6
     624379.5364    4319585.1984     624346.0644    4319902.5278
     624327.9854    4319959.3708      624321.851    4320001.7019
     624330.1894    4320022.9134      624320.005    4320155.3766
#Sta/Elev= 30
       0  628.42   18.41  624.03   42.95  616.84    58.3  616.25   79.77  612.75
  110.45  606.56  125.79  601.25  150.34  597.07  159.54  594.15  199.43  590.35
  273.07  573.61  309.89  570.16  342.95   569.7  357.86  568.64  375.76   566.8
  401.87  567.04   410.3  569.41  415.92  571.62  418.73  571.76  424.39  578.96
  427.24  581.26  447.36  584.91  474.53  601.91  489.63  606.75  498.69  607.56
  507.74  609.84   516.8  614.27  540.96  618.59  559.07  624.96  577.19  628.86
#Mann= 3 , 0 , 0
       0      .1       0  357.86    .041       0   410.3      .1       0
Bank Sta=357.86,410.3
XS Rating Curve= 0 ,0
Exp/Cntr=0.3,0.1

Type RM Length L Ch R = 1 ,4335.917,90.37,91.44,90.66
XS GIS Cut Line= 5
     624348.8446    4319640.2318     624242.6149    4319925.4921
     624234.6544    4319956.8332     624229.9914      4319970.98
     624213.9659    4320033.2583
#Sta/Elev= 30
       0  621.01   24.35  615.47   33.48  614.07   57.84   607.3   60.88  607.31
   82.19  599.45   97.41  596.93  112.63  592.86  167.42  584.18  191.77     576
  194.81  575.48  206.99  569.82     277  569.88  283.09  568.98  292.22  567.03
  301.35  566.43  342.69  566.42  345.67  566.62  351.63  569.95  354.69  571.03
  357.75  573.74  360.82  574.34  363.88  578.51     370   588.4  373.07  592.37
  382.25  600.73  391.44  607.75  397.56  610.19  406.75   617.3  415.94  621.72
#Mann= 3 , 0 , 0
       0      .1       0  283.09    .041       0  351.63      .1       0
Bank Sta=283.09,351.63
XS Rating Curve= 0 ,0
Exp/Cntr=0.3,0.1

Type RM Length L Ch R = 1 ,4244.477,28.23,30.27,30.63
XS GIS Cut Line= 6
     624246.1663    4319657.4122     624166.2797    4319875.0728
     624154.9576    4319901.9977     624146.2751    4319931.0374
     624142.7744    4319946.6974     624120.2421    4320028.0023
#Sta/Elev= 30
       0  620.06   21.36  613.04   27.46  612.72   42.71  609.04   54.91  604.17
   61.02  603.09   85.42  592.29   88.47  591.35   91.52   591.9   97.62  586.89
  106.78  587.26  125.08  583.52  149.49  572.81  189.15  570.45  234.78  571.23
  243.54  569.41  255.22  566.59  296.73  566.43  302.07  567.17  307.42  569.57
  310.44  571.93  316.46   581.7  319.48  585.14  322.49  587.72  328.52  590.11
  343.58   602.2  352.62  606.61  358.65  607.87  382.75  618.25  391.79  620.32
#Mann= 3 , 0 , 0
       0      .1       0  243.54    .041       0  307.42      .1       0
Bank Sta=243.54,307.42
XS Rating Curve= 0 ,0
Exp/Cntr=0.3,0.1

Type RM Length L Ch R = 1 ,4214.208,34.11,61.17,75.5
XS GIS Cut Line= 6
     624222.2768    4319674.5957     624140.5204    4319861.1273
     624123.0579    4319902.4024     624116.7079     4319926.215
     624103.2141    4319974.6338      624080.989    4320020.6714
#Sta/Elev= 30
       0  617.35   12.16  614.73   21.28   611.3   39.52  603.21    45.6  601.89
   57.75  596.79   69.91  592.68   75.99  588.74   79.03  588.27   82.07  585.53
   88.15  585.09   97.27  580.27  103.35  578.04  112.47   575.4  121.59  574.21
  130.71  571.35  206.65  570.93  221.59  568.59  230.55  566.68  236.53  566.33
  276.08  566.64  284.95   567.8  287.91  569.56  293.82  572.47  311.56  590.56
  317.47  593.08  326.39  599.79  338.42  603.94  356.47   608.1  374.51   616.5
#Mann= 3 , 0 , 0
       0      .1       0  221.59    .041       0  287.91      .1       0
Bank Sta=221.59,287.91
XS Rating Curve= 0 ,0
Exp/Cntr=0.3,0.1

Type RM Length L Ch R = 1 ,4153.037,47.12,35.85,32.46
XS GIS Cut Line= 5
     624202.2245     4319686.408     624141.1056    4319802.2957
     624086.2729    4319865.7083     624055.2583    4319888.3539
     624002.1991    4320001.5273
#Sta/Elev= 30
       0  613.81   33.52  599.09   36.56  598.98   39.61  597.66   67.03  582.25
   73.13  580.86   82.27  577.65  100.55  573.65  106.64  570.79  181.91  570.94
  196.88   569.3  214.85  566.33  247.34  565.94   262.4  566.02  277.64  566.77
  280.69  567.74  283.74  569.44  289.83  570.74  292.88  572.38  308.13  585.53
  311.17  587.73  317.27  590.73  320.32  590.83  326.42  593.39  347.76  605.33
  350.81  606.64  353.86     607     363  609.65   375.2  611.92  378.24  613.62
#Mann= 3 , 0 , 0
       0      .1       0  196.88    .041       0  283.74      .1       0
Bank Sta=196.88,283.74
XS Rating Curve= 0 ,0
Exp/Cntr=0.3,0.1

Type RM Length L Ch R = 1 ,4117.191,55.98,55.59,57.5
XS GIS Cut Line= 4
     624130.2016    4319679.3582     624072.2578    4319822.2335
     624019.0764    4319886.5274     623972.2451    4320001.6214
#Sta/Elev= 30
       0   604.1    6.05  599.74   15.12  594.67   21.16  592.92    39.3  581.82
   48.37  578.22   54.42  577.26   63.49  573.85   72.55  569.74    78.6  569.66
   90.69  571.97  105.81  570.65  129.99  570.13  148.13     571   166.1  568.68
     181  566.32  207.82  565.94  246.71  566.24  249.74  566.45  252.77  567.42
   255.8  569.12  261.86  571.08  270.95  576.13  277.02  578.19  304.29  593.94
  313.38  597.43  328.54  605.23  337.63  607.61  346.72  608.15  361.87  609.96
#Mann= 3 , 0 , 0
       0      .1       0   166.1    .041       0   255.8      .1       0
Bank Sta=166.1,255.8
XS Rating Curve= 0 ,0
Exp/Cntr=0.3,0.1

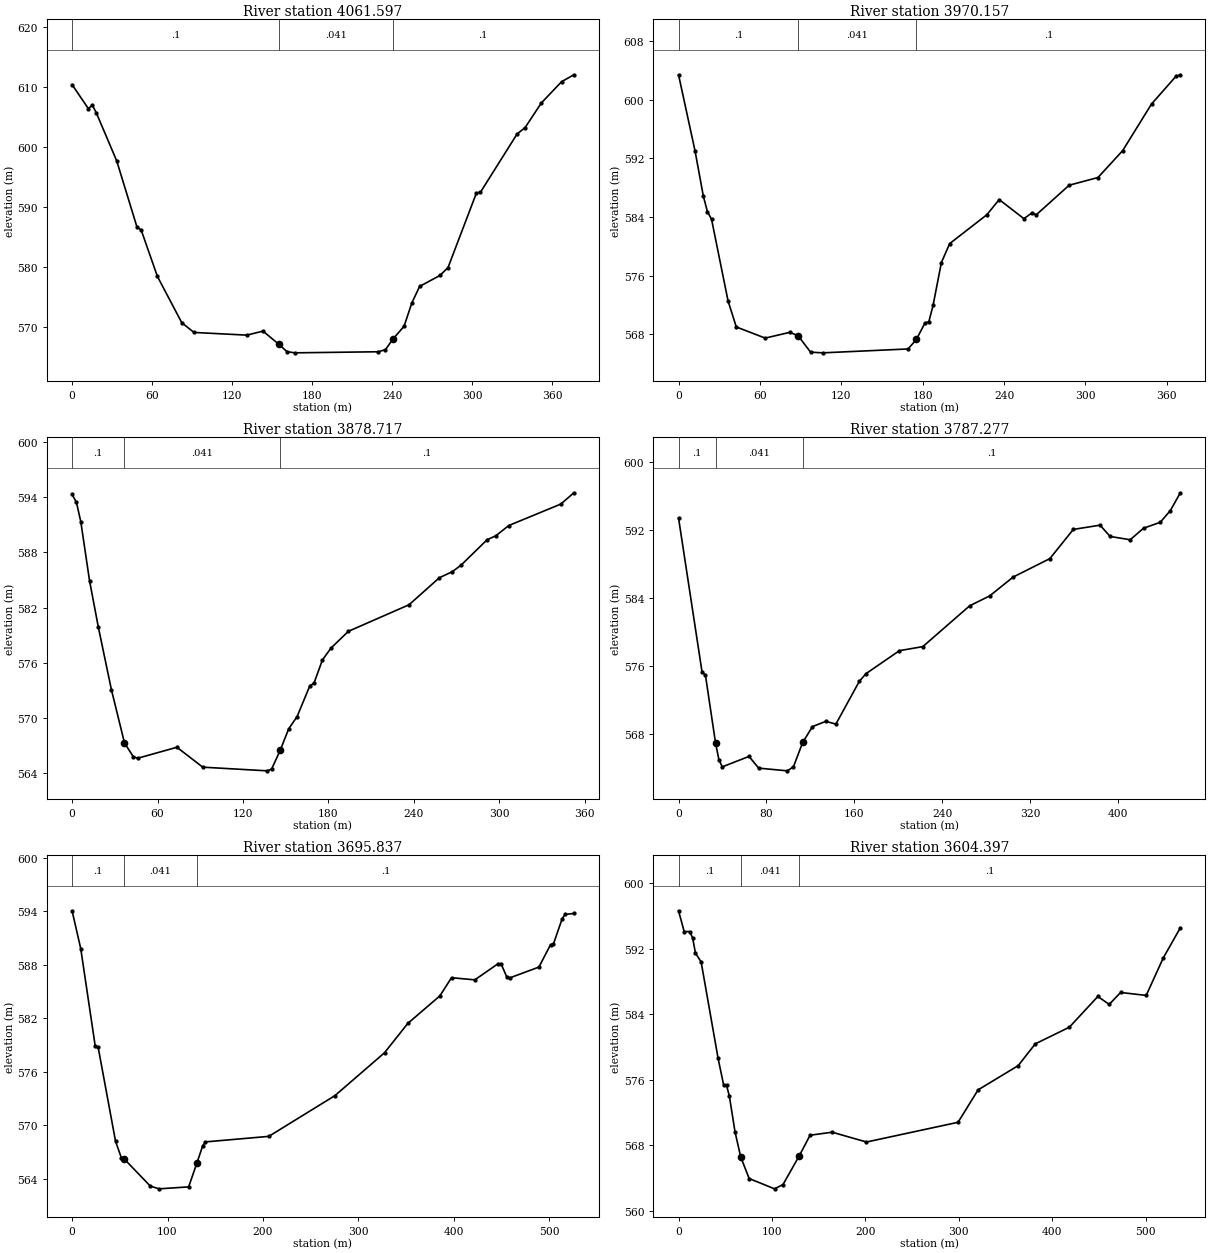
Type RM Length L Ch R = 1 ,4061.597,87.1,91.44,94.92
XS GIS Cut Line= 6
     624079.4784    4319658.7351     624025.6055    4319788.1513
     623975.0368    4319858.6812     623963.3053    4319869.8142
      623959.998    4319887.0121     623929.9885    4319998.7253
#Sta/Elev= 30
       0  610.46   12.19  606.47   15.24  607.04   18.28  605.71   33.52  597.73
   48.76  586.67   51.81  586.25      64   578.5   82.28  570.79   91.42  569.17
  131.04  568.72  143.17  569.39  155.14  567.19  161.13  565.97  167.11  565.77
  229.66  565.95  235.05   566.3  240.44  568.01  248.98   570.2  254.82  574.08
  260.65  576.84  275.87  578.66  281.96  579.98  303.27  592.41  306.31  592.54
  333.71  602.22   339.8  603.31  351.97  607.41  367.19  610.96  376.33   612.1
#Mann= 3 , 0 , 0
       0      .1       0  155.14    .041       0  240.44      .1       0
Bank Sta=155.14,240.44
XS Rating Curve= 0 ,0
Exp/Cntr=0.3,0.1

Type RM Length L Ch R = 1 ,3970.157,87.4,91.44,92.83
XS GIS Cut Line= 5
     623999.8073    4319665.1596     623940.6367    4319757.3264
     623907.0198    4319802.9493     623880.0055    4319832.2984
     623833.4154    4319989.4649
#Sta/Elev= 30
       0   603.4   12.17  593.02   18.25  586.89    21.3  584.73   24.34   583.7
   36.51  572.56   42.59  569.01   63.89  567.49   82.14  568.28   88.23   567.8
   97.36  565.57  106.48  565.48  169.26  566.01   175.4  567.31  181.54  569.49
  184.61  569.75  187.68  571.94  193.81  577.79  199.95  580.38  227.34  584.31
  236.44  586.38  254.66  583.78  260.73  584.58  263.76   584.3  288.05  588.34
   309.3  589.39  327.51  593.06  348.76  599.41  366.98  603.23  370.01  603.37
#Mann= 3 , 0 , 0
       0      .1       0   88.23    .041       0   175.4      .1       0
Bank Sta=88.23,175.4
XS Rating Curve= 0 ,0
Exp/Cntr=0.3,0.1

Type RM Length L Ch R = 1 ,3878.717,103.48,91.44,74.06
XS GIS Cut Line= 5
      623919.647    4319632.8186     623877.6026    4319693.2726
     623830.4726    4319748.4643     623812.8218    4319775.8301
     623784.4674    4319947.1315
#Sta/Elev= 30
       0  594.33    3.07  593.47    6.14  591.35   12.27  584.92   18.41  579.89
   27.61  573.05   36.82  567.23   42.95  565.74   46.02  565.56   73.64  566.76
   91.78  564.59  137.14  564.19  140.17  564.39  146.21  566.44  152.13  568.77
  158.06  570.11  166.94  573.45   169.9  573.75  175.82  576.28  181.82  577.57
  194.01   579.4  236.66   582.3  257.98  585.25  267.12  585.91  273.21  586.62
  291.49  589.39  297.58  589.82  306.72  590.94  343.27  593.28  352.41  594.51
#Mann= 3 , 0 , 0
       0      .1       0   36.82    .041       0  146.21      .1       0
Bank Sta=36.82,146.21
XS Rating Curve= 0 ,0
Exp/Cntr=0.3,0.1

Type RM Length L Ch R = 1 ,3787.277,103.16,91.44,80.64
XS GIS Cut Line= 6
     623805.6619    4319597.6189     623784.9446    4319655.2695
     623773.6636    4319682.2907     623766.3887    4319706.5726
     623760.7663    4319733.3617     623745.3543    4320046.6025
#Sta/Elev= 30
       0  593.43   21.44  575.24    24.5  574.89   33.69   566.9   36.76  564.92
   39.82  564.08   64.19  565.31   72.97  563.93   98.99  563.61  104.62  564.08
  113.07  566.97  121.97  568.83  134.14  569.45  143.26  569.12  164.58  574.16
  170.67  575.07  201.11  577.78  222.43  578.26  265.06  583.07  283.33  584.24
  304.64  586.46  338.13  588.64  359.45  592.08  383.81  592.58  392.94  591.25
  411.21  590.86  423.39  592.22  438.61  592.92  447.75  594.29  456.88   596.4
#Mann= 3 , 0 , 0
       0      .1       0   33.69    .041       0  113.07      .1       0
Bank Sta=33.69,113.07
XS Rating Curve= 0 ,0
Exp/Cntr=0.3,0.1

Type RM Length L Ch R = 1 ,3695.837,99.72,91.44,58.61
XS GIS Cut Line= 5
     623689.0984    4319550.1231     623689.4645    4319659.3838
     623684.6323    4319674.0684     623686.1484    4319824.8227
     623726.0605    4320071.8828
#Sta/Elev= 30
       0  594.06    9.11  589.81   24.28  578.88   27.32  578.77   45.53  568.24
    51.6  566.39   54.63  566.25   81.95  563.21   91.05   562.9  122.14  563.12
  130.75  565.78  136.78   567.7   139.8  568.16  206.13  568.78  275.48  573.35
  327.37  578.15  351.78  581.44  385.35  584.52  397.56  586.56  421.98  586.32
  446.39  588.13  449.45  588.13  455.55  586.62   458.6  586.54  489.12  587.75
  501.33  590.26  504.38  590.35  513.54  593.18  516.59  593.65  525.75  593.76
#Mann= 3 , 0 , 0
       0      .1       0   54.63    .041       0  130.75      .1       0
Bank Sta=54.63,130.75
XS Rating Curve= 0 ,0
Exp/Cntr=0.3,0.1

Type RM Length L Ch R = 1 ,3604.397,110.39,91.44,84.43
XS GIS Cut Line= 6
     623569.8574    4319571.1522     623604.8963    4319680.5744
     623611.3646     4319685.913     623631.8699    4319717.9938
     623657.2687    4319924.7741     623721.8272    4320079.2911
#Sta/Elev= 30
       0  596.65    6.05  594.11   12.09  594.11   15.12  593.31   18.14  591.47
   24.19   590.4   42.33  578.63   48.38  575.32    51.4  575.31   54.42     574
   60.47  569.64   66.52  566.59   75.59  563.94   102.8  562.68  111.87  563.21
  129.14   566.7  140.85  569.23  164.42   569.6  201.19   568.4  299.22  570.81
  320.67  574.77  363.56  577.73  381.87  580.39  418.41  582.43  448.85  586.18
  461.03  585.21  473.21  586.67  500.62  586.31  518.88  590.89  537.15  594.57
#Mann= 3 , 0 , 0
       0      .1       0   66.52    .041       0  129.14      .1       0
Bank Sta=66.52,129.14
XS Rating Curve= 0 ,0
Exp/Cntr=0.3,0.1

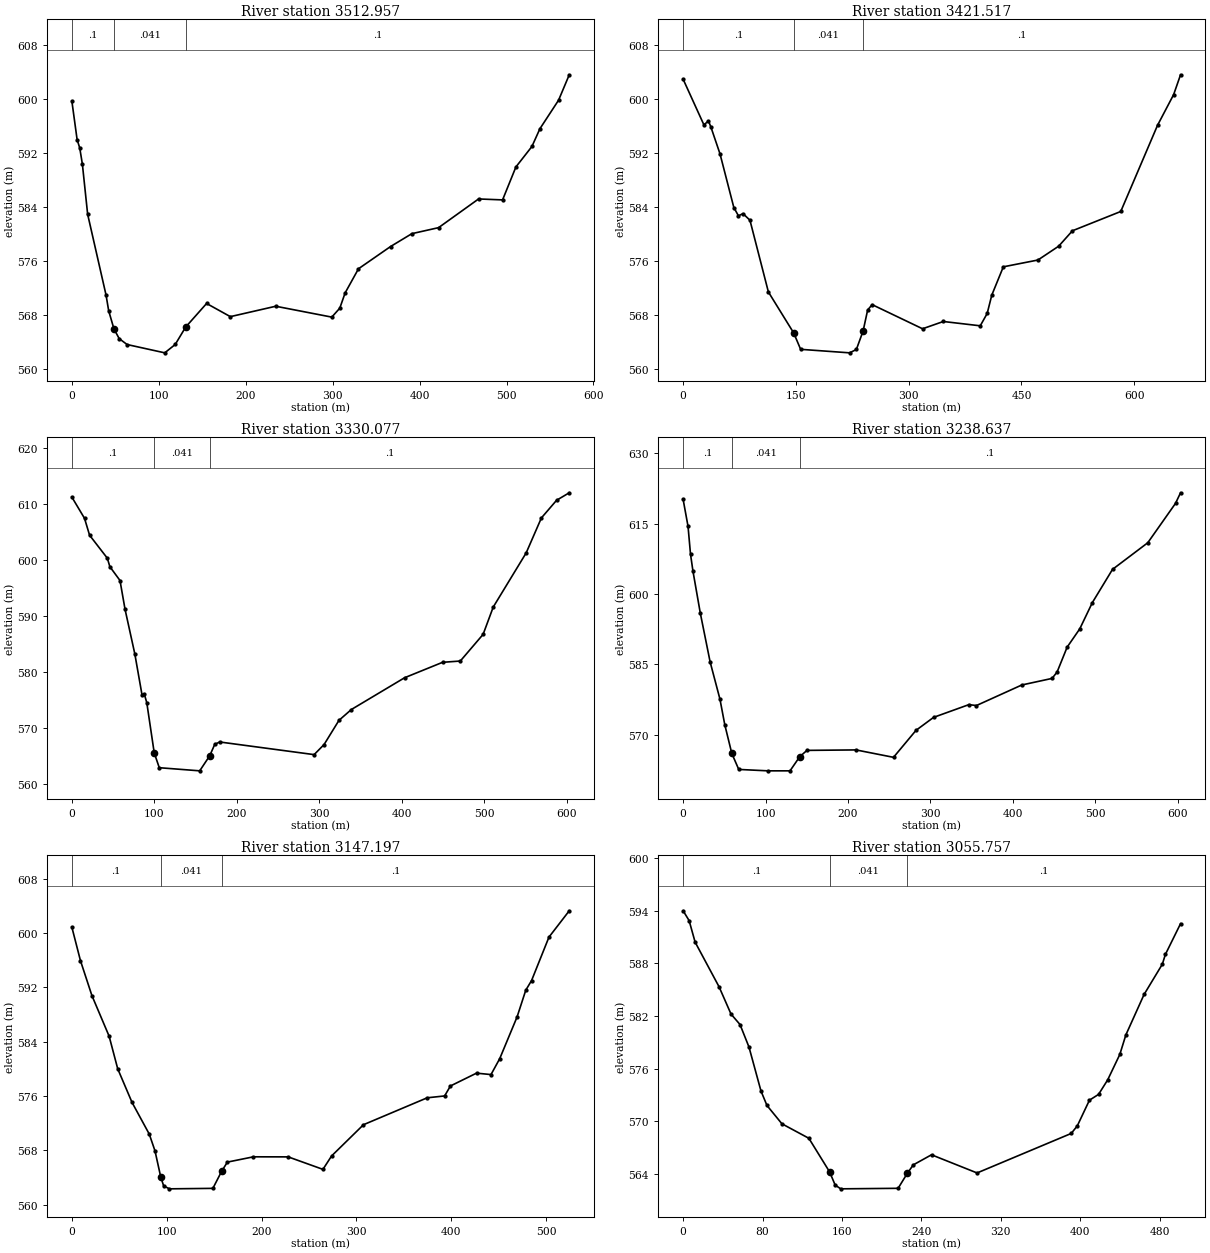
Type RM Length L Ch R = 1 ,3512.957,97.85,91.44,65.03
XS GIS Cut Line= 6
     623450.9195    4319632.3768     623502.8135    4319683.2155
     623521.1939    4319704.5424     623562.7033    4319759.8752
     623661.4265     4319988.164     623736.1147    4320122.1537
#Sta/Elev= 30
       0  599.66    6.05  593.94    9.08   592.7   12.11  590.31   18.16  582.89
   39.35  570.91   42.38  568.58   48.43   565.9   54.49  564.46   63.57  563.59
  106.88  562.36  118.91   563.6  130.94  566.18     155  569.67  182.32  567.72
  234.52  569.26  299.01  567.65  308.22  568.98  314.36  571.24  329.71  574.81
  366.56   578.1  391.12  580.01  421.83   580.9  467.85  585.15  495.46  585.01
   510.8  589.89  529.21  592.92  538.41  595.55  559.89  599.78  572.16  603.54
#Mann= 3 , 0 , 0
       0      .1       0   48.43    .041       0  130.94      .1       0
Bank Sta=48.43,130.94
XS Rating Curve= 0 ,0
Exp/Cntr=0.3,0.1

Type RM Length L Ch R = 1 ,3421.517,89.95,91.44,101.88
XS GIS Cut Line= 6
     623300.0805    4319668.1278     623462.3623    4319766.9264
     623478.0955     4319786.892     623532.7788    4319802.9186
     623626.0478    4319993.0368      623733.998    4320133.7954
#Sta/Elev= 30
       0  602.93   27.58  596.17   33.71  596.73   36.77  595.89   49.03  591.86
   67.42   583.9   73.54  582.67   79.67  582.99   88.87  582.01  113.38  571.37
  147.09  565.28  156.28  562.86  221.41  562.34  230.41  562.84   239.4   565.6
   245.4   568.7   251.4  569.49  318.43  565.91  346.05  566.99  395.16  566.35
  404.36  568.18   410.5   570.9  425.85   575.1  471.88  576.11  499.45  578.16
   517.8  580.45  582.03  583.31  630.96   596.1  652.37  600.65  661.55  603.59
#Mann= 3 , 0 , 0
       0      .1       0  147.09    .041       0   239.4      .1       0
Bank Sta=147.09,239.4
XS Rating Curve= 0 ,0
Exp/Cntr=0.3,0.1

Type RM Length L Ch R = 1 ,3330.077,127.51,91.44,63.4
XS GIS Cut Line= 6
     623326.5639    4319781.1398     623387.8927    4319809.4538
     623397.5713    4319832.4129     623490.0221    4319887.7706
     623593.9072    4319974.6854     623759.3981    4320180.3622
#Sta/Elev= 30
       0  611.27   15.35  607.47   21.49  604.45   42.99  600.34   46.06  598.82
   58.34  596.35   64.48  591.18   76.28  583.24   85.02   575.9   87.91  575.99
   90.81  574.49   99.82  565.52  105.94  562.87  154.93  562.31  167.12  565.02
  173.15  567.05  179.17  567.47  293.57  565.21  305.61  567.01  323.67  571.34
  338.72  573.28  403.18  578.96  449.22  581.72  470.71  581.95  498.34  586.72
  510.62  591.61  550.52  601.29  568.94  607.54  587.36   610.7  602.71  612.04
#Mann= 3 , 0 , 0
       0      .1       0   99.82    .041       0  167.12      .1       0
Bank Sta=99.82,167.12
XS Rating Curve= 0 ,0
Exp/Cntr=0.3,0.1

Type RM Length L Ch R = 1 ,3238.637,92.26,91.44,60.66
XS GIS Cut Line= 6
     623297.8047    4319935.2184     623367.4273    4319925.9417
     623431.7739    4319937.1483     623474.2661    4319947.7121
     623577.6919    4319982.6901     623784.5336    4320220.0497
#Sta/Elev= 30
       0  620.16    5.95  614.41    8.93  608.51    11.9  604.89   20.83  595.92
   32.73  585.53   44.63  577.61   50.58  572.09   59.02  566.03   67.46  562.61
  102.93  562.31  129.65  562.31  141.42  565.32  150.18  566.67   209.7  566.77
  255.19  565.19  282.48  570.94  303.83  573.71  346.63  576.42   355.8  576.23
  410.82  580.61   447.5  582.01  453.61  583.36  465.84  588.68  481.12  592.57
   496.4  598.17  520.86  605.25  563.65  610.93  597.27  619.32  603.39  621.58
#Mann= 3 , 0 , 0
       0      .1       0   59.02    .041       0  141.42      .1       0
Bank Sta=59.02,141.42
XS Rating Curve= 0 ,0
Exp/Cntr=0.3,0.1

Type RM Length L Ch R = 1 ,3147.197,75.39,91.44,132.02
XS GIS Cut Line= 6
     623279.1784    4319995.1535     623362.1254    4320023.4166
     623400.6449    4320014.0908     623462.5759    4319997.2422
      623553.961    4320002.1694     623726.3251    4320171.1017
#Sta/Elev= 30
       0  600.88    9.07  595.94   21.15  590.79   39.28  584.81   48.35     580
   63.46  575.04   81.59  570.38   87.63  567.91   93.73  564.04   96.78  562.74
  102.87  562.31  148.66  562.38  157.83  564.88  163.94  566.25  191.44  567.03
  228.05  567.02  264.66  565.18  273.81  567.16   307.4  571.76  374.61  575.73
  392.94     576  399.05  577.47  426.55  579.36  441.82  579.15  450.99  581.49
  469.32  587.65  478.48  591.59  484.59  593.01  502.92  599.41  524.31  603.29
#Mann= 3 , 0 , 0
       0      .1       0   93.73    .041       0  157.83      .1       0
Bank Sta=93.73,157.83
XS Rating Curve= 0 ,0
Exp/Cntr=0.3,0.1

Type RM Length L Ch R = 1 ,3055.757,90.15,91.44,78.29
XS GIS Cut Line= 5
     623217.0012    4320026.9035     623343.1892    4320097.8288
     623364.1257    4320105.8156     623398.1512    4320108.1505
     623677.3771    4320217.4039
#Sta/Elev= 30
       0  593.99    6.03  592.87   12.06  590.42   36.19  585.33   48.25  582.22
    57.3  581.03   66.35  578.46   78.41  573.46   84.44  571.81   99.52  569.72
  126.66  568.07  147.56  564.24  153.16  562.74  158.76  562.31  216.57  562.37
  225.74  564.06  231.86  565.04  250.22  566.19  296.12  564.12  390.96  568.62
  397.08  569.48  409.32  572.41   418.5  573.07  427.68  574.72  439.92  577.62
  446.03  579.85  464.39  584.46  482.75   587.9  485.81  589.01  501.11  592.52
#Mann= 3 , 0 , 0
       0      .1       0  147.56    .041       0  225.74      .1       0
Bank Sta=147.56,225.74
XS Rating Curve= 0 ,0
Exp/Cntr=0.3,0.1

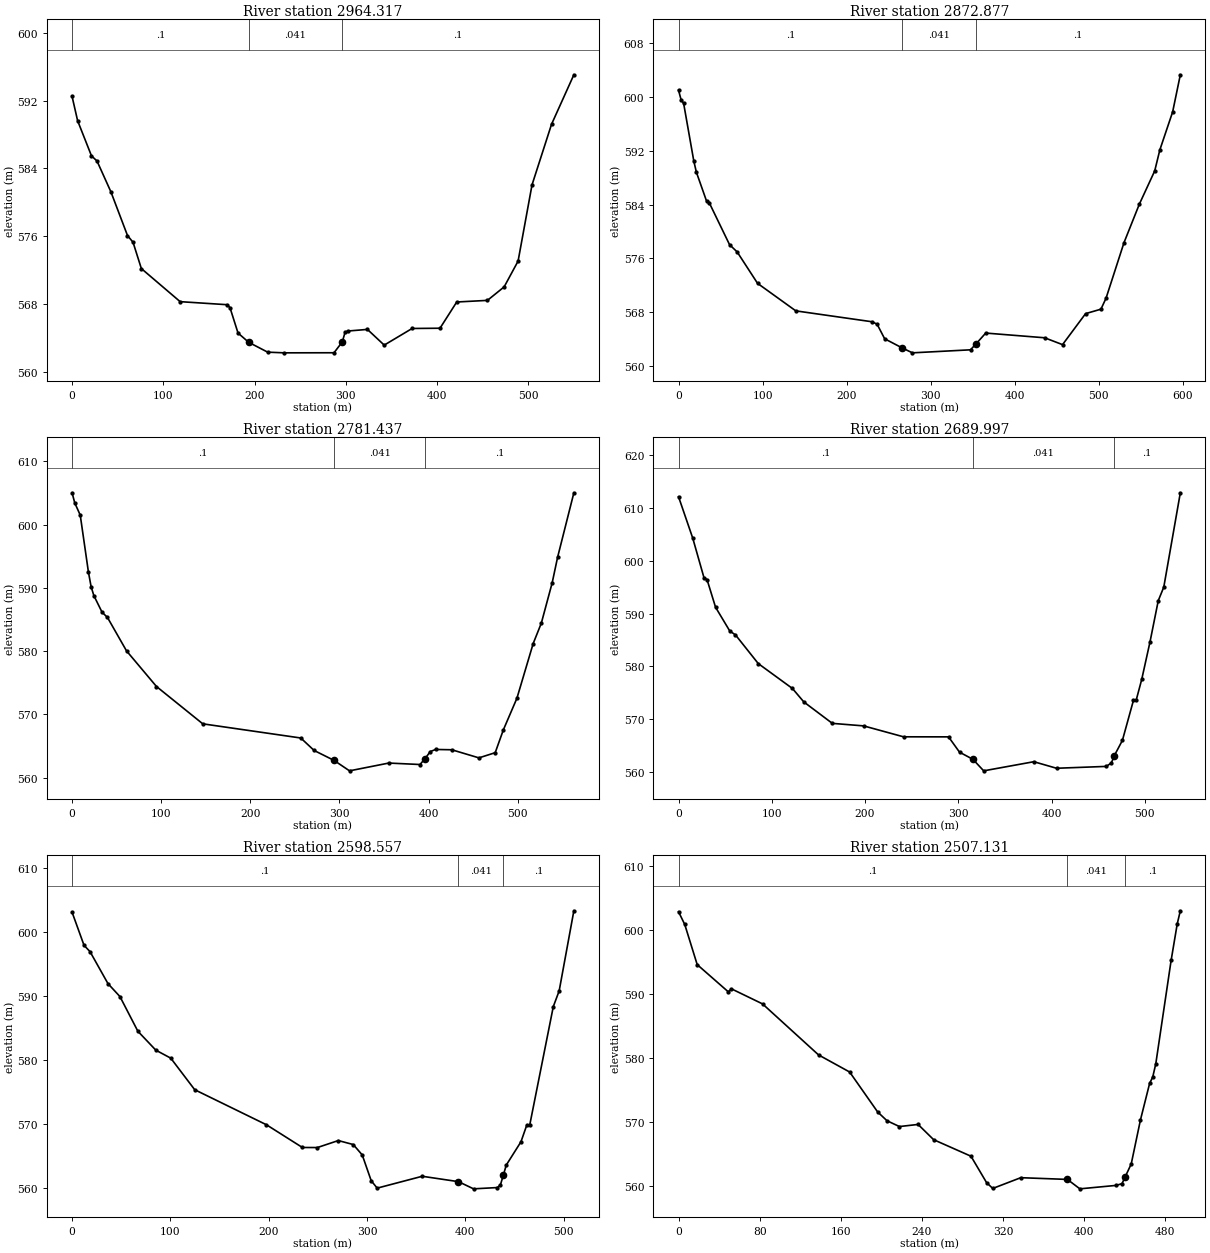
Type RM Length L Ch R = 1 ,2964.317,82.03,91.44,105.55
XS GIS Cut Line= 6
     623153.5011    4320048.0702     623280.0571    4320166.1437
     623308.6322    4320180.9604     623351.0024     4320196.994
     623445.1575    4320202.1271     623641.7433    4320259.2772
#Sta/Elev= 30
       0  592.49    6.07  589.63   21.26  585.49   27.33  584.88   42.51  581.26
   60.73   576.1    66.8  575.31   75.91  572.21  118.43  568.31  170.05  567.95
  173.08  567.59  181.86  564.61  193.57  563.52  214.33  562.36  232.45  562.28
  287.05  562.29  296.15  563.58  299.19  564.72  302.22  564.85  323.63  565.04
  342.05  563.19  372.61  565.15  403.17  565.18   421.5  568.27  455.12  568.46
  473.45  570.05  488.73  573.09     504  582.07  525.39  589.21  549.84  595.04
#Mann= 3 , 0 , 0
       0      .1       0  193.57    .041       0  296.15      .1       0
Bank Sta=193.57,296.15
XS Rating Curve= 0 ,0
Exp/Cntr=0.3,0.1

Type RM Length L Ch R = 1 ,2872.877,58.69,91.44,98.65
XS GIS Cut Line= 6
     623116.7063    4320040.1503     623217.2185    4320220.3834
     623262.4847    4320249.8435     623340.0374    4320282.6542
     623351.7594    4320280.3116     623561.1542    4320399.2171
#Sta/Elev= 30
       0  601.01    3.03   599.6    6.07  599.06   18.21  590.46   21.24  588.83
   33.38  584.52   36.42  584.32    60.7  578.06    69.8  576.97   94.08   572.3
   139.6  568.21  230.37  566.59  236.37  566.23  245.37  564.06  266.39  562.69
  278.42  561.97  347.57  562.42  353.55  563.22  365.68  564.91  435.79  564.21
  457.12  563.19  484.56   567.8  502.84  568.46  508.94   570.1  530.28  578.35
  548.57  584.08  566.85  589.02  572.95  592.14  588.19  597.79  597.34  603.31
#Mann= 3 , 0 , 0
       0      .1       0  266.39    .041       0  353.55      .1       0
Bank Sta=266.39,353.55
XS Rating Curve= 0 ,0
Exp/Cntr=0.3,0.1

Type RM Length L Ch R = 1 ,2781.437,36.61,91.44,137.94
XS GIS Cut Line= 6
     623091.3062    4320041.2087     623208.2579    4320283.2926
     623227.8371     4320316.101     623249.2999    4320340.2317
     623308.0933    4320365.6807      623446.854    4320441.7622
#Sta/Elev= 30
       0  605.02    3.06   603.4    9.17  601.49   18.33  592.51   21.39  590.16
   24.44  588.77   33.61  586.15   39.72  585.31    61.1  580.03   94.71   574.4
  146.65   568.5  256.63  566.26  271.56  564.29  293.94  562.72  311.29  561.07
  355.35   562.3  390.38  562.07  396.13  563.02  401.88  564.11   407.8  564.45
  426.06   564.4  456.49  563.12  474.75  563.94  483.88  567.54   499.1  572.54
  517.36  581.19  526.49  584.41  538.66  590.78  544.74  594.82     563  605.01
#Mann= 3 , 0 , 0
       0      .1       0  293.94    .041       0  396.13      .1       0
Bank Sta=293.94,396.13
XS Rating Curve= 0 ,0
Exp/Cntr=0.3,0.1

Type RM Length L Ch R = 1 ,2689.997,53.99,91.44,89.52
XS GIS Cut Line= 6
     623063.7895     4320023.217     623175.9346    4320274.1204
     623188.5618    4320342.5818     623232.9281    4320439.3807
     623228.8513    4320448.7457     623234.8563    4320525.3966
#Sta/Elev= 30
       0  612.14   15.27  604.27   27.48  596.67   30.54  596.45    39.7  591.19
   54.97  586.68   61.07  585.95    85.5  580.51  122.14  575.79  134.36  573.24
   164.9  569.18  198.49   568.7  241.24  566.63  289.53  566.62   301.3  563.72
  315.69  562.36  327.21  560.18  380.99  561.91  405.33  560.67  458.63  561.02
  464.14  561.68  467.09  562.99  475.97  565.96  487.79  573.53  490.75  573.58
  496.67  577.51  505.54  584.61  514.41  592.44  520.32     595  538.07  612.89
#Mann= 3 , 0 , 0
       0      .1       0  315.69    .041       0  467.09      .1       0
Bank Sta=315.69,467.09
XS Rating Curve= 0 ,0
Exp/Cntr=0.3,0.1

Type RM Length L Ch R = 1 ,2598.557,92.43,91.43,90.6
XS GIS Cut Line= 5
     623046.8561    4320038.0337     623130.6235    4320314.6546
     623135.4233    4320360.0237     623139.0301    4320448.9922
       623150.35    4320534.9181
#Sta/Elev= 30
       0  603.09   12.17  597.92   18.25  596.94   36.51  591.95   48.68  589.93
   66.93  584.52   85.19  581.57   100.4  580.32  124.74   575.4  197.75  569.93
  234.26  566.39  249.48  566.38  270.77  567.47  285.98  566.85  295.11  565.23
  304.23  561.21  310.32  560.05  356.14   561.9  392.99  561.06  408.34  559.94
  432.66  560.14  435.64  560.55  438.63  562.06  441.62  563.65  456.56  567.28
  462.54  569.91  465.53  569.93  489.44  588.36  495.42  590.82  510.36  603.31
#Mann= 3 , 0 , 0
       0      .1       0  392.99    .041       0  438.63      .1       0
Bank Sta=392.99,438.63
XS Rating Curve= 0 ,0
Exp/Cntr=0.3,0.1

Type RM Length L Ch R = 1 ,2507.131,90.91,91.45,94.86
XS GIS Cut Line= 4
     623015.1061     4320035.917     623048.6214    4320458.0823
     623051.3513    4320471.7933      623061.067     4320528.459
#Sta/Elev= 30
       0  602.85    6.14  600.86   18.41   594.6    49.1  590.35   52.17  590.82
   82.86  588.47   138.1  580.51  168.78  577.84   196.4  571.61  205.61  570.24
  217.88  569.33   236.3  569.66  251.64  567.28  288.47   564.7  303.81  560.59
  309.95  559.67  337.57  561.35   383.6  561.08  395.87  559.61  431.88  560.15
  437.47  560.43   440.5  561.45  446.55   563.5  455.63  570.36  464.71  576.08
  467.73  577.04  470.76  579.12  485.89  595.26  491.94  600.97  494.97     603
#Mann= 3 , 0 , 0
       0      .1       0   383.6    .041       0   440.5      .1       0
Bank Sta=383.6,440.5
XS Rating Curve= 0 ,0
Exp/Cntr=0.3,0.1