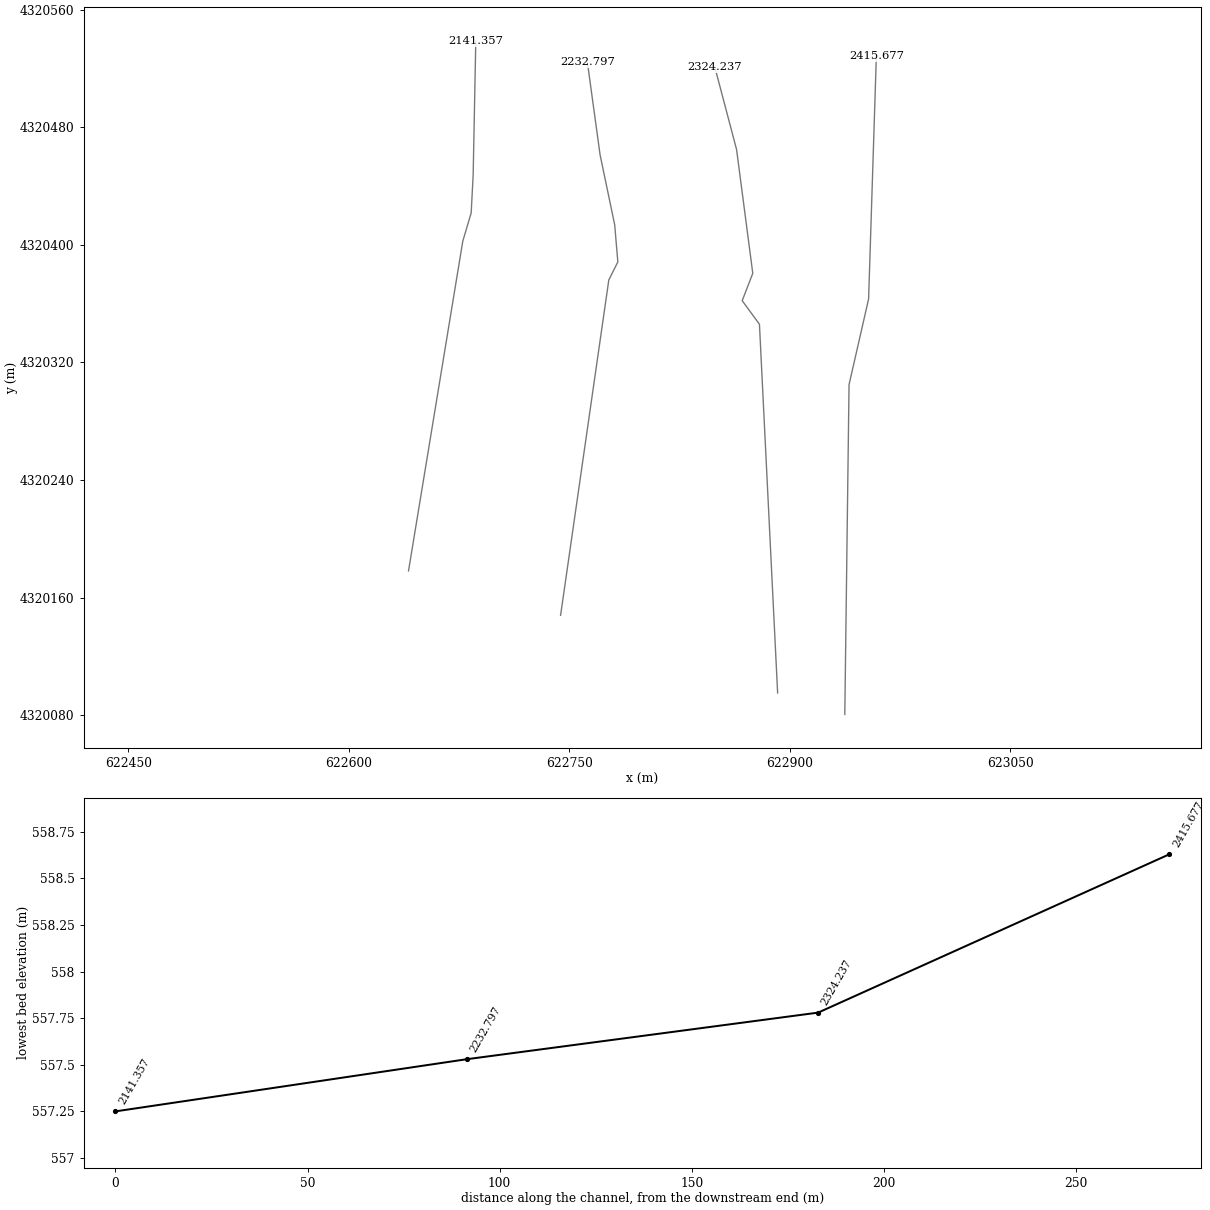
HEC-RAS study RedCreek.prj: RedCreek

--- RedCreek.g01 (geometry) --- (continued)

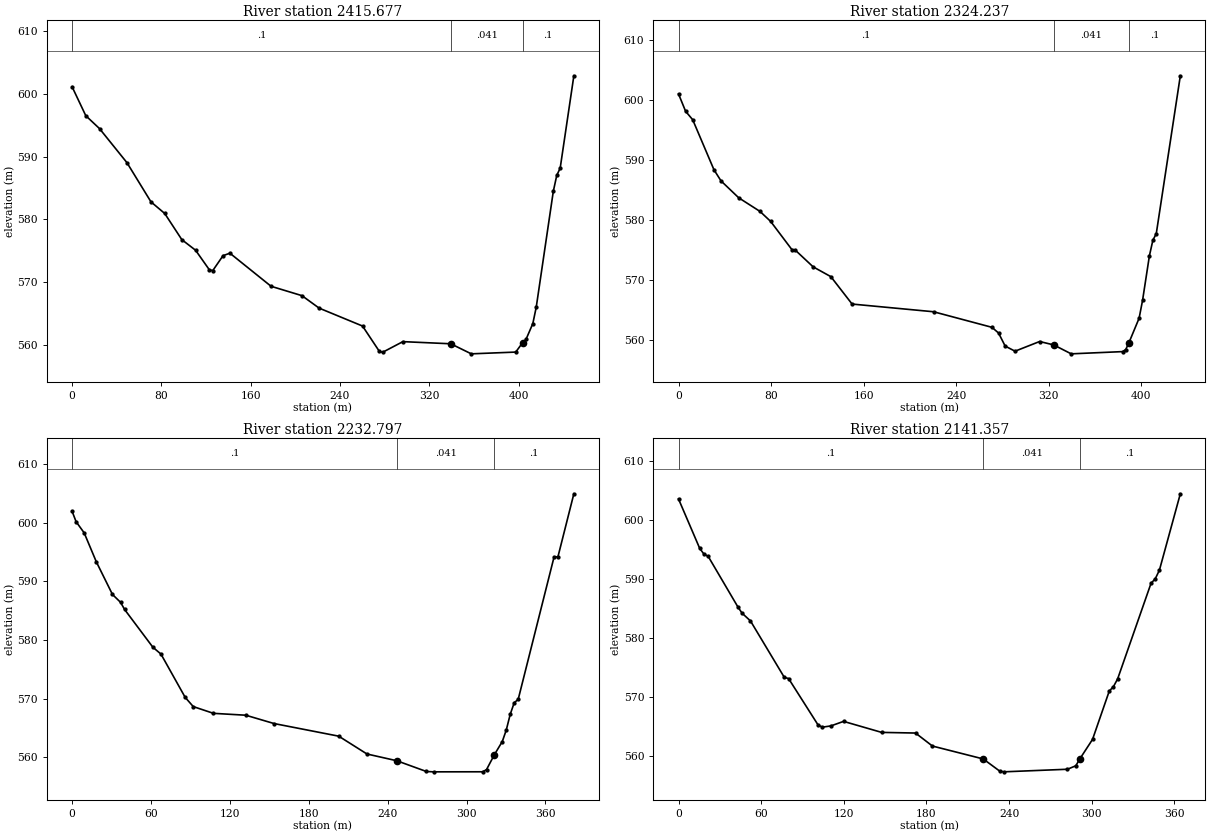
Type RM Length L Ch R = 1 ,2415.677,77.84,91.44,98.82
XS GIS Cut Line= 4
      622937.452    4320080.5405     622940.3392    4320304.9113
      622953.642    4320363.1343      622958.919    4320528.4795
#Sta/Elev= 30
       0   601.1    12.3  596.49   24.59  594.44   49.18  589.02    70.7  582.79
   82.99  580.95   98.36  576.78  110.66   575.1  122.95     572  126.03  571.86
  135.25  574.24   141.4  574.63  178.28  569.37  205.95  567.88  221.32   565.9
  260.22  563.05  275.15  559.06  278.14  558.87  296.37  560.57  339.26  560.23
  357.64  558.63  397.46  558.91  403.59  560.39  406.65  560.92  412.78  563.44
  415.84  566.05  431.16   584.5  434.22     587  437.29  588.16  449.54  602.84
#Mann= 3 , 0 , 0
       0      .1       0  339.26    .041       0  403.59      .1       0
Bank Sta=339.26,403.59
XS Rating Curve= 0 ,0
Exp/Cntr=0.3,0.1

Type RM Length L Ch R = 1 ,2324.237,117.74,91.44,89.96
XS GIS Cut Line= 6
     622891.7571    4320095.1573     622879.3867    4320345.9544
      622867.658    4320362.0085     622874.8504    4320380.6161
     622863.8304    4320464.8198       622849.05    4320520.8391
#Sta/Elev= 30
       0     601    6.12  598.12   12.25  596.72   30.62   588.4   36.75  586.54
   52.06  583.73   70.43  581.47   79.62  579.81   97.99  575.12  101.05  575.01
  116.36  572.25  131.68  570.62  150.05  566.06  220.48  564.78  270.98  562.19
  276.68  561.24  282.38  559.07  290.93  558.22  312.16  559.83   324.3  559.27
  339.46  557.78  383.91  558.15   386.6  558.49  389.28  559.58  398.19  563.71
  401.16  566.66   407.1   574.1  410.07  576.66  413.03  577.78  433.82  604.03
#Mann= 3 , 0 , 0
       0      .1       0   324.3    .041       0  389.28      .1       0
Bank Sta=324.3,389.28
XS Rating Curve= 0 ,0
Exp/Cntr=0.3,0.1

Type RM Length L Ch R = 1 ,2232.797,112.18,91.44,85.32
XS GIS Cut Line= 6
     622744.1193     4320148.008     622776.9156      4320376.07
      622783.054    4320388.3467     622780.9373    4320413.5351
     622770.9944    4320461.1331     622762.3641    4320524.0422
#Sta/Elev= 30
       0  601.95    3.07  600.16    9.22  598.25   18.43  593.33   30.72  587.76
   36.87  586.42   39.94   585.2   61.44  578.77   67.59   577.6   86.02  570.22
   92.16  568.65  107.52   567.5   132.1  567.18  153.61  565.76  202.76  563.61
  224.26  560.57  246.94  559.42  269.41  557.59  274.92  557.53  312.29  557.54
  315.19  557.92  321.11  560.44  327.16   562.7  330.18  564.65  333.21  567.35
  336.23  569.31  339.25  569.88  366.47   594.1  369.49  594.19  381.58  604.92
#Mann= 3 , 0 , 0
       0      .1       0  246.94    .041       0  321.11      .1       0
Bank Sta=246.94,321.11
XS Rating Curve= 0 ,0
Exp/Cntr=0.3,0.1

Type RM Length L Ch R = 1 ,2141.357,202.93,2141.36,205.97
XS GIS Cut Line= 5
      622640.667    4320178.1705     622677.5909     4320402.485
     622683.2995    4320421.7145     622684.6431    4320447.5104
     622686.4314    4320538.5391
#Sta/Elev= 30
       0  603.59   15.36  595.21   18.43  594.24    21.5  593.86   43.01  585.29
   46.08  584.21   52.23  582.88    76.8  573.29   79.87   573.1  101.38  565.18
  104.45  564.84  110.59  565.05  119.81  565.82  147.46  563.95  172.04  563.84
  184.32  561.63  221.19  559.44  233.06  557.39  235.93  557.25  282.33  557.69
   288.4  558.28  291.43  559.49  300.54  562.76  312.68  570.97  315.71  571.72
  318.75  573.03  343.03  589.29  346.06  590.03  349.09  591.51  364.27  604.48
#Mann= 3 , 0 , 0
       0      .1       0  221.19    .041       0  291.43      .1       0
Bank Sta=221.19,291.43
XS Rating Curve= 0 ,0
Exp/Cntr=0.3,0.1
LCMann Table=0

Chan Stop Cuts=-1
Use User Specified Reach Order=0
Composite Channel Slope=5